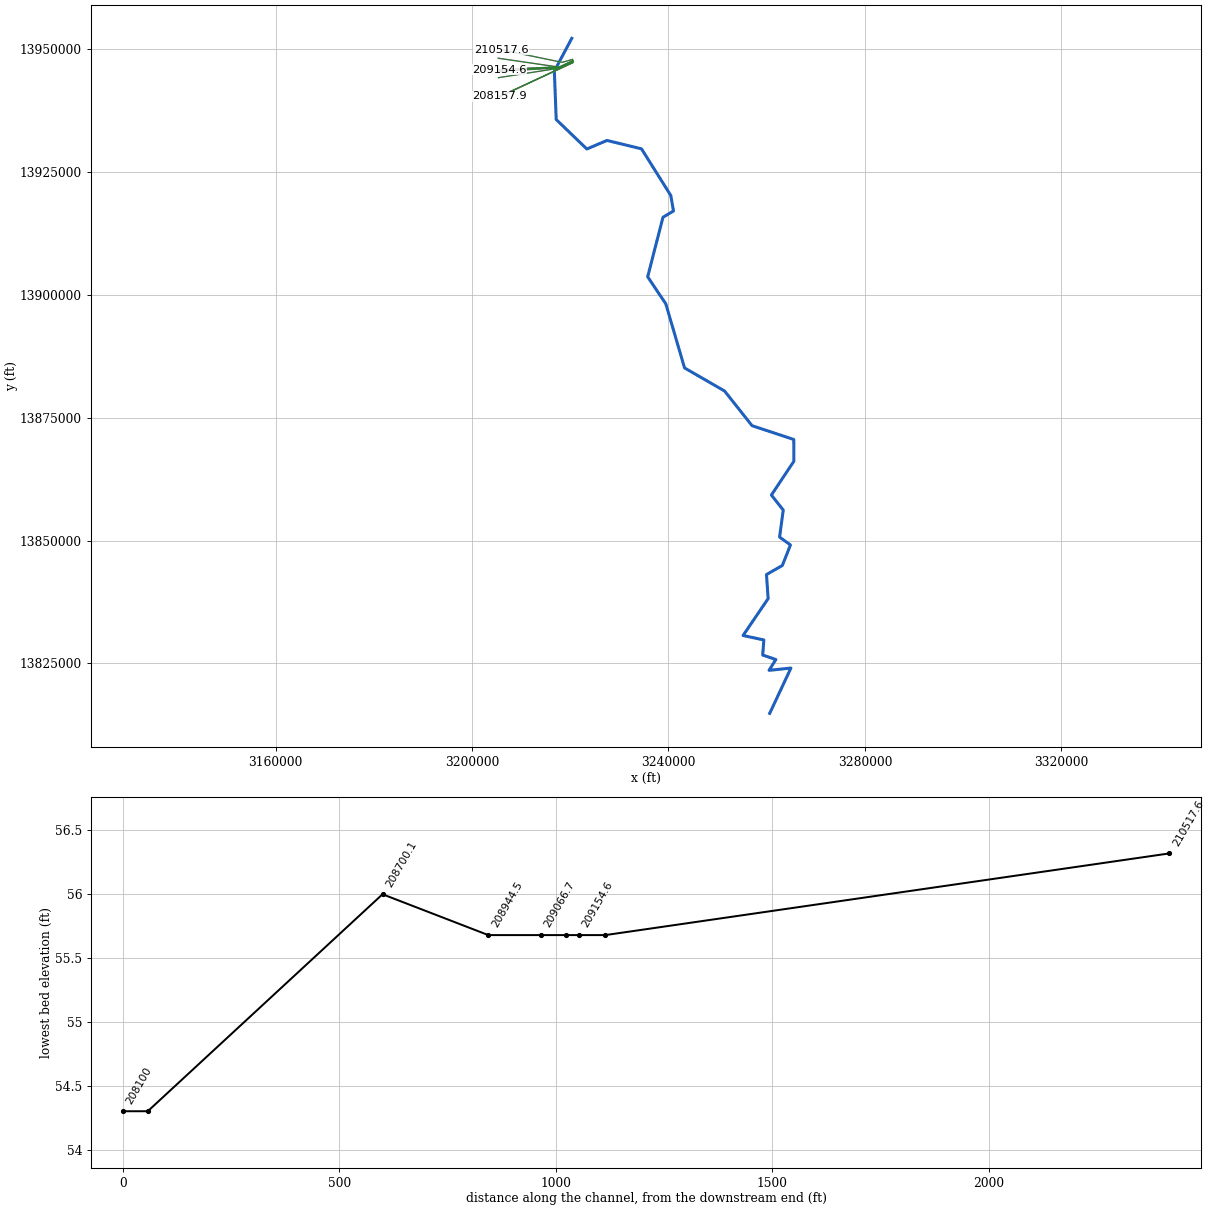
--- Q100-00-00.prj (project) ---

Proj Title=Q100-00-00
Current Plan=p02
Default Exp/Contr=.3,.1
English Units
Geom File=g01
Flow File=f02
Flow File=f01
Plan File=p01
Plan File=p02
Y Axis Title=Elevation
X Axis Title(PF)=Main Channel Distance
X Axis Title(XS)=Station
BEGIN DESCRIPTION:
Cedar Bayou
Cedar Bayou
HCFCD Unit Q100-00-00
10, 2, 1, 0.2% Event
Filename Q100_00_00.prj
Prepared by: Guillermo Simon DATE: 04/30/04
Reviewed by:                           DATE:
STATUS: Final
END DESCRIPTION:
DSS Export Filename=C:\C2001_041\HECRAS\output.RASexport_DSS.sdf
DSS Export Rating Curves= 0
DSS Export Rating Curve Sorted= 0
DSS Export Volume Flow Curves= 0
DXF OffsetX= 0
DXF OffsetY= 0
DXF ScaleX= 1
DXF ScaleY= 10

--- Q100-00-00.p02 (plan) ---

Plan Title=Floodway
Version=Version 3.0.1  Mar 2001
Short Identifier=Floodway0607
Geom File=g01
Flow File=f02
Subcritical Flow
K Sum by GR= 0
Std Step Tol= 0.01
Critical Tol= 0.01
Num of Std Step Trials= 20
Max Error Tol= 0.3
Flow Tol Ratio= 0.001
Split Flow NTrial= 30
Split Flow Tol= 0.02
Split Flow Ratio= 0.02
Log Output Level= 0
Friction Slope Method= 0
Unsteady Friction Slope Method= 2
Secant Critical Depth
Global Vel Dist= 0 , 0 , 0
Global Log Level= 0
CheckData=True
Encroach Param=-1 ,0,0, 2
Encroach River=Q100-00-00
Encroach Reach=Cedar Bayou Main
Encroach Node=210517.6
       1    4380    6314
Encroach Node=209214.7
       1    4860    6695
Encroach Node=209154.6
       1    4860    6985
Encroach Node=209123.7
       1    4860    7000
Encroach Node=209093.5
       1    4850    7045
Encroach Node=209066.7
       1    4850    7045
Encroach Node=208944.5
       1    4850    7111
Encroach Node=208700.1
       1    4850    7350
Encroach Node=208157.9
       1    4700    7300
Encroach Node=208100
       1    4540    6850
Encroach Node=207984
       1 4582.33    6800
Encroach Node=207930
       1 4582.33    6800
Encroach Node=207900.3
       1 4557.46    6850
Encroach Node=207859.5
       1 4557.46    6850
Encroach Node=207759.7
       1 4557.46    6850
Encroach Node=207543.4
       1    4954    7300
Encroach Node=207214
       1    4961    7100
Encroach Node=206824.1
       1    4938    7000
Encroach Node=206341.5
       1  4953.5    6900
Encroach Node=205402.9
       1 4810.05    6808
Encroach Node=205176.3
       1    4933    6787
Encroach Node=204084.9
       1  4930.5    7010
Encroach Node=202961.3
       1  4940.5    8080
Encroach Node=201917.9
       1  4975.5    8132
Encroach Node=200850.6
       1    4965    8100
Encroach Node=199889.3
       1    4900    8050
Encroach Node=198721.4
       1    4600    7250
Encroach Node=197117.3
       1 4184.08    7000
Encroach Node=197086.9
       1 4184.08    6995
Encroach Node=196820
       1    4900    6270
Encroach Node=196518.3
       1 4529.75    6973
Encroach Node=196388.4
       1 4529.75    6950
Encroach Node=195687.9
       1  4828.2    6641
Encroach Node=194579.1
       1  4963.5    6493
Encroach Node=193535.9
       1    4959    6250
Encroach Node=192480.6
       1  4958.5    6905
Encroach Node=191332.1
       1  4961.5    7067
Encroach Node=190279.7
       1    4973 6760.08
Encroach Node=189304.5
       1 4905.51 6810.06
Encroach Node=188944.3
       1 4670.93    6460
Encroach Node=188171.8
       1 4129.79    5990
Encroach Node=187151.1
       1 4370.78    6634
Encroach Node=186078.1
       1 4281.41    7345
Encroach Node=184917.5
       1    4783    7696
Encroach Node=184885.9
       1  4770.3    7723
Encroach Node=184731.7
       1  4770.3    7600
Encroach Node=184514.9
       1  4770.3    7607
Encroach Node=184373.2
       1    4736    7580
Encroach Node=183807.7
       1 4494.85    7400
Encroach Node=182706
       1 4206.64    7265
Encroach Node=181673.3
       1 3750.35    6915
Encroach Node=180577.6
       1 4325.68    6505
Encroach Node=179512.7
       1 4608.92    6215
Encroach Node=178351.2
       1    4912    5730
Encroach Node=177321.2
       1  4908.5    5524
Encroach Node=176298.9
       1  4930.5    5706
Encroach Node=174939.2
       1 4295.26    5646
Encroach Node=173985.6
       1    4933    5451
Encroach Node=172755.4
       1    4914    5412
Encroach Node=171624.7
       1  4950.5  5600.2
Encroach Node=170369.2
       1 4678.96 5210.83
Encroach Node=169266.8
       1  4477.7    5250
Encroach Node=168356.2
       1 4526.96 5480.06
Encroach Node=167282.3
       1 4840.05    5250
Encroach Node=167164.1
       1    4861    5160
Encroach Node=167120.7
       1 4921.28 5134.72
Encroach Node=167085.7
       1 4855.78  5144.8
Encroach Node=167059
       1 4829.42 5119.42
Encroach Node=166968
       1 4829.42 5119.42
Encroach Node=166824.6
       1 4766.74    5050
Encroach Node=166398.4
       1  4914.5 5236.61
Encroach Node=165591.4
       1  4920.5  5090.5
Encroach Node=164595.1
       1 4213.37 5378.44
Encroach Node=163197
       1 4529.92  5064.5
Encroach Node=162357.4
       1 4643.97 5082.96
Encroach Node=161176.4
       1 4758.33    5555
Encroach Node=160313.5
       1  4958.5    5777
Encroach Node=159117.4
       1 4574.84 5782.73
Encroach Node=157631.3
       1    4934    5380
Encroach Node=155854
       1    4660    5760
Encroach Node=154794.9
       1    4900    5850
Encroach Node=153552.5
       1    4120    5800
Encroach Node=152574.5
       1    3200    5580
Encroach Node=151504.8
       1    2100    5610
Encroach Node=150456.5
       1    2000    5600
Encroach Node=149206.6
       1    2050    5180
Encroach Node=148487.4
       1    2400    5460
Encroach Node=147196.6
       1    3500    6000
Encroach Node=145816.8
       1    2800    5200
Encroach Node=144891.9
       1    2400    5200
Encroach Node=143894.1
       1    2100 5105.74
Encroach Node=142357
       1 2964.22    5095
Encroach Node=141273.9
       1 2962.45 5118.19
Encroach Node=140841.6
       1    3200    5073
Encroach Node=139838.1
       1    3500    5600
Encroach Node=138603.7
       1 3577.16    6400
Encroach Node=137536.6
       1 3875.78    7023
Encroach Node=136370.3
       1 4456.06    7023
Encroach Node=135331.6
       1 4467.12    6580
Encroach Node=133922.9
       1 4274.37    5770
Encroach Node=132651.6
       1 3804.51    5140
Encroach Node=131329.3
       1 3137.91    5118
Encroach Node=130408.4
       1 2998.29    5440
Encroach Node=129366.7
       1 3030.41    5466
Encroach Node=128345.9
       1 3687.03 5600.12
Encroach Node=127122.8
       1 3577.78 6119.88
Encroach Node=126201.7
       1    3903 6935.47
Encroach Node=125220.7
       1    4500    7160
Encroach Node=123942
       1  4937.5 7461.61
Encroach Node=122942.4
       1 4901.85 7641.05
Encroach Node=121853.9
       1    4883    7000
Encroach Node=120696.2
       1    4400    6972
Encroach Node=119831.8
       1    4000    6800
Encroach Node=119222.3
       1 3961.25 5757.14
Encroach Node=118522.2
       1 4538.72 5392.78
Encroach Node=117911.4
       1 4521.85 4797.47
Encroach Node=117495.2
       1 3865.63    5500
Encroach Node=116574.6
       1    3200    5800
Encroach Node=115684.3
       1    3700 5959.72
Encroach Node=114660.7
       1 3354.33 6364.19
Encroach Node=113599.8
       1 4087.93  6129.6
Encroach Node=112571.4
       1 4658.07    6100
Encroach Node=111566.4
       1  4827.9 5767.15
Encroach Node=110747.4
       1    4902 5341.42
Encroach Node=110296
       1 4367.73 5122.61
Encroach Node=110185.2
       1 4150.04  5103.2
Encroach Node=110135.1
       1    4100  5134.5
Encroach Node=110052
       1    4100  5134.5
Encroach Node=109970.9
       1    4000  5134.5
Encroach Node=109770.1
       1 3730.37 5294.48
Encroach Node=108969.3
       1 3774.78    6066
Encroach Node=107906.6
       1  4656.6    6220
Encroach Node=106890.1
       1 4518.07    6450
Encroach Node=105902.8
       1 4638.12    6100
Encroach Node=105320.2
       1 4432.23    5840
Encroach Node=104392.8
       1 4094.78    5400
Encroach Node=103452.2
       1 3293.31    5175
Encroach Node=102491.3
       1 3671.48    5124
Encroach Node=101376.5
       1 3784.21    5465
Encroach Node=100334.7
       1 4054.28    5175
Encroach Node=99259.29
       1    4894 5332.64
Encroach Node=98356.65
       1  4926.5    5450
Encroach Node=97381.72
       1 4728.49    5585
Encroach Node=96104.63
       1 4149.96    5260
Encroach Node=95283.76
       1    4955    5135
Encroach Node=95210.55
       14930.715    5165
Encroach Node=95179.92
       1  4932.5    5155
Encroach Node=95115.8
       1 4799.09    5150
Encroach Node=95042.8
       1    4909    5105
Encroach Node=94922.61
       1 4896.09    5105
Encroach Node=94046.74
       1 4514.23    5108
Encroach Node=93326.72
       1 4727.42 5221.05
Encroach Node=92670.8
       1 4592.73 5242.69
Encroach Node=92470.05
       1 4671.75    5150
Encroach Node=92418.29
       1  4784.5  5136.8
Encroach Node=92216.8
       1  4784.5  5136.8
Encroach Node=92026.57
       1  4784.5    5200
Encroach Node=91824.63
       1  4849.2    5380
Encroach Node=91609.41
       1 4411.75    5437
Encroach Node=90762.7
       1    4700    5500
Encroach Node=90125.32
       1 4350.51    5775
Encroach Node=89326.48
       1 4513.05    5600
Encroach Node=88667.88
       1 4796.79    5800
Encroach Node=88135.45
       1 4910.97    5800
Encroach Node=87008.24
       1  4910.5    5920
Encroach Node=85467.86
       1 4272.67 5222.64
Encroach Node=84443.81
       1    4887 5408.65
Encroach Node=83547.66
       1    4759    5206
Encroach Node=82895.54
       1    4873    5335
Encroach Node=82307.9
       1    4700    5177
Encroach Node=82220.89
       1    4700  5134.5
Encroach Node=82190.89
       1 4703.06 5131.42
Encroach Node=82163.1
       1 4688.57 5131.42
Encroach Node=82136.12
       1 4688.57 5113.01
Encroach Node=82016.09
       1    4700 5246.78
Encroach Node=81180.05
       1 4876.63 5443.71
Encroach Node=80360.35
       1 4875.25    5540
Encroach Node=79254.91
       1  4899.5    5385
Encroach Node=78275.05
       1    4800    5110
Encroach Node=77250.26
       1  4815.5 5292.54
Encroach Node=76035.24
       1 4638.57    5523
Encroach Node=74962.84
       1 4665.43    5425
Encroach Node=73498.96
       1 4703.67    5350
Encroach Node=72487.93
       1    4814    5680
Encroach Node=71225.56
       1 4646.46    5237
Encroach Node=70126.59
       1 4646.79    5170
Encroach Node=69033.28
       1 4485.89 5110.75
Encroach Node=68105.34
       1 4727.52    5500
Encroach Node=66946.82
       1    4924    5468
Encroach Node=65958.72
       1    4750    5435
Encroach Node=64961.1
       1 4913.25    5670
Encroach Node=63892.65
       1 4918.49    5512
Encroach Node=62629.87
       1 4759.01    5315
Encroach Node=61783.4
       1 4921.28    5365
Encroach Node=59436.15
       1 4622.24 5261.27
Encroach Node=58341.37
       1 4927.11 5246.81
Encroach Node=58271.63
       1    4819    5210
Encroach Node=58182.5
       1    4836    5192
Encroach Node=58089.67
       1 4896.15    5065
Encroach Node=57802.5
       1    4876 5126.85
Encroach Node=57445.25
       1 4908.31    5555
Encroach Node=56558.41
       1 4886.93    5900
Encroach Node=54943.36
       1 4832.67    5600
Encroach Node=54001.98
       1 4673.57 5244.47
Encroach Node=53006.21
       1 4838.81 5184.99
Encroach Node=51768.84
       1 4847.76 5128.25
Encroach Node=50893.4
       1 4897.42  5181.5
Encroach Node=49907.02
       1 4851.39 5274.33
Encroach Node=48722.71
       1 4892.56    5146
Encroach Node=47745.99
       1  4665.6 5406.48
Encroach Node=46386.08
       1 4576.03 5279.15
Encroach Node=45364.25
       1  4810.5    5650
Encroach Node=44198.85
       1 4830.61    5550
Encroach Node=43345.11
       1    4600    5420
Encroach Node=42270.17
       1    4200 5231.89
Encroach Node=40959.15
       1    4200    5700
Encroach Node=39965.81
       1    4400    6000
Encroach Node=38870.92
       1    4700    6000
Encroach Node=37939.04
       1 4408.02    5400
Encroach Node=36777.61
       1 4614.11    5485
Encroach Node=35491.18
       1 4792.97 5405.27
Encroach Node=34326.29
       1 4770.73    5300
Encroach Node=33267.79
       1    4798    5355
Encroach Node=33211.74
       1 3284.87 3722.58
Encroach Node=32942.1
       1 3284.87 3934.58
Encroach Node=32806.91
       1 3496.87 3934.58
Encroach Node=32526.8
       1  4705.5  5294.5
Encroach Node=31801.25
       1 4836.28    5179
Encroach Node=31750.97
       1 4836.28    5179
Encroach Node=31645.17
       1 4834.03    5177
Encroach Node=31582.5
       1 4834.03    5177
Encroach Node=31379.93
       1 4834.03    5265
Encroach Node=30585.5
       1 4766.55 5233.45
Encroach Node=29469.51
       1 4776.56 5223.44
Encroach Node=28381.91
       1 4767.72 5232.28
Encroach Node=27388.16
       1 4753.86 5246.14
Encroach Node=26325.42
       1 4809.28    5260
Encroach Node=25299.47
       1 4790.09    5300
Encroach Node=24186.67
       1 4757.73    5300
Encroach Node=23242.39
       1 4760.99 5239.01
Encroach Node=22040.03
       1 4825.39    5215
Encroach Node=20925.69
       1 4797.85    5850
Encroach Node=20092.01
       1 4857.41    6200
Encroach Node=18888.3
       1 4874.69    5810
Encroach Node=9775.511
       1 4574.06  5057.1
Encroach Node=5807.924
       1 3022.52 5277.89
Encroach Node=1797.325
       1 1630.67 4627.04
Encroach Reach=Q100-00-00_0018
Encroach Node=210517.6
       1    4380    6314
Encroach Node=209214.7
       1    4860    6695
Encroach Node=209154.6
       1    4860    6985
Encroach Node=209123.7
       1    4860    7000
Encroach Node=209093.5
       1    4850    7045
Encroach Node=209066.7
       1    4850    7045
Encroach Node=208944.5
       1    4850    7111
Encroach Node=208700.1
       1    4850    7350
Encroach Node=208157.9
       1    4700    7300
Encroach Node=208100
       1    4540    6850
Encroach Node=207984
       1 4582.33    6800
Encroach Node=207930
       1 4582.33    6800
Encroach Node=207900.3
       1 4557.46    6850
Encroach Node=207859.5
       1 4557.46    6850
Encroach Node=207759.7
       1 4557.46    6850
Encroach Node=207543.4
       1    4954    7300
Encroach Node=207214
       1    4961    7100
Encroach Node=206824.1
       1    4938    7000
Encroach Node=206341.5
       1  4953.5    6900
Encroach Node=205402.9
       1 4810.05    6808
Encroach Node=205176.3
       1    4933    6787
Encroach Node=204084.9
       1  4930.5    7010
Encroach Node=202961.3
       1  4940.5    8080
Encroach Node=201917.9
       1  4975.5    8132
Encroach Node=200850.6
       1    4965    8100
Encroach Node=199889.3
       1    4900    8050
Encroach Node=198721.4
       1    4600    7250
Encroach Node=197117.3
       1 4184.08    7000
Encroach Node=197086.9
       1 4184.08    6995
Encroach Node=196820
       1    4900    6270
Encroach Node=196518.3
       1 4529.75    6973
Encroach Node=196388.4
       1 4529.75    6950
Encroach Node=195687.9
       1  4828.2    6641
Encroach Node=194579.1
       1  4963.5    6493
Encroach Node=193535.9
       1    4959    6250
Encroach Node=192480.6
       1  4958.5    6905
Encroach Node=191332.1
       1  4961.5    7067
Encroach Node=190279.7
       1    4973 6760.08
Encroach Node=189304.5
       1 4905.51 6810.06
Encroach Node=188944.3
       1 4670.93    6460
Encroach Node=188171.8
       1 4129.79    5990
Encroach Node=187151.1
       1 4370.78    6634
Encroach Node=186078.1
       1 4281.41    7345
Encroach Node=184917.5
       1    4783    7696
Encroach Node=184885.9
       1  4770.3    7723
Encroach Node=184731.7
       1  4770.3    7600
Encroach Node=184514.9
       1  4770.3    7607
Encroach Node=184373.2
       1    4736    7580
Encroach Node=183807.7
       1 4494.85    7400
Encroach Node=182706
       1 4206.64    7265
Encroach Node=181673.3
       1 3750.35    6915
Encroach Node=180577.6
       1 4325.68    6505
Encroach Node=179512.7
       1 4608.92    6215
Encroach Node=178351.2
       1    4912    5730
Encroach Node=177321.2
       1  4908.5    5524
Encroach Node=176298.9
       1  4930.5    5706
Encroach Node=174939.2
       1 4295.26    5646
Encroach Node=173985.6
       1    4933    5451
Encroach Node=172755.4
       1    4914    5412
Encroach Node=171624.7
       1  4950.5  5600.2
Encroach Node=170369.2
       1 4678.96 5210.83
Encroach Node=169266.8
       1  4477.7    5250
Encroach Node=168356.2
       1 4526.96 5480.06
Encroach Node=167282.3
       1 4840.05    5250
Encroach Node=167164.1
       1    4861    5160
Encroach Node=167120.7
       1 4921.28 5134.72
Encroach Node=167085.7
       1 4855.78  5144.8
Encroach Node=167059
       1 4829.42 5119.42
Encroach Node=166968
       1 4829.42 5119.42
Encroach Node=166824.6
       1 4766.74    5050
Encroach Node=166398.4
       1  4914.5 5236.61
Encroach Node=165591.4
       1  4920.5  5090.5
Encroach Node=164595.1
       1 4213.37 5378.44
Encroach Node=163197
       1 4529.92  5064.5
Encroach Node=162357.4
       1 4643.97 5082.96
Encroach Node=161176.4
       1 4758.33    5555
Encroach Node=160313.5
       1  4958.5    5777
Encroach Node=159117.4
       1 4574.84 5782.73
Encroach Node=157631.3
       1    4934    5380
Encroach Node=155854
       1    4660    5760
Encroach Node=154794.9
       1    4900    5850
Encroach Node=153552.5
       1    4120    5800
Encroach Node=152574.5
       1    3200    5580
Encroach Node=151504.8
       1    2100    5610
Encroach Node=150456.5
       1    2000    5600
Encroach Node=149206.6
       1    2050    5180
Encroach Node=148487.4
       1    2400    5460
Encroach Node=147196.6
       1    3500    6000
Encroach Node=145816.8
       1    2800    5200
Encroach Node=144891.9
       1    2400    5200
Encroach Node=143894.1
       1    2100 5105.74
Encroach Node=142357
       1 2964.22    5095
Encroach Node=141273.9
       1 2962.45 5118.19
Encroach Node=140841.6
       1    3200    5073
Encroach Node=139838.1
       1    3500    5600
Encroach Node=138603.7
       1 3577.16    6400
Encroach Node=137536.6
       1 3875.78    7023
Encroach Node=136370.3
       1 4456.06    7023
Encroach Node=135331.6
       1 4467.12    6580
Encroach Node=133922.9
       1 4274.37    5770
Encroach Node=132651.6
       1 3804.51    5140
Encroach Node=131329.3
       1 3137.91    5118
Encroach Node=130408.4
       1 2998.29    5440
Encroach Node=129366.7
       1 3030.41    5466
Encroach Node=128345.9
       1 3687.03 5600.12
Encroach Node=127122.8
       1 3577.78 6119.88
Encroach Node=126201.7
       1    3903 6935.47
Encroach Node=125220.7
       1    4500    7160
Encroach Node=123942
       1  4937.5 7461.61
Encroach Node=122942.4
       1 4901.85 7641.05
Encroach Node=121853.9
       1    4883    7000
Encroach Node=120696.2
       1    4400    6972
Encroach Node=119831.8
       1    4000    6800
Encroach Node=119222.3
       1 3961.25 5757.14
Encroach Node=118522.2
       1 4538.72 5392.78
Encroach Node=117911.4
       1 4521.85 4797.47
Encroach Node=117495.2
       1 3865.63    5500
Encroach Node=116574.6
       1    3200    5800
Encroach Node=115684.3
       1    3700 5959.72
Encroach Node=114660.7
       1 3354.33 6364.19
Encroach Node=113599.8
       1 4087.93  6129.6
Encroach Node=112571.4
       1 4658.07    6100
Encroach Node=111566.4
       1  4827.9 5767.15
Encroach Node=110747.4
       1    4902 5341.42
Encroach Node=110296
       1 4367.73 5122.61
Encroach Node=110185.2
       1 4150.04  5103.2
Encroach Node=110135.1
       1    4100  5134.5
Encroach Node=110052
       1    4100  5134.5
Encroach Node=109970.9
       1    4000  5134.5
Encroach Node=109770.1
       1 3730.37 5294.48
Encroach Node=108969.3
       1 3774.78    6066
Encroach Node=107906.6
       1  4656.6    6220
Encroach Node=106890.1
       1 4518.07    6450
Encroach Node=105902.8
       1 4638.12    6100
Encroach Node=105320.2
       1 4432.23    5840
Encroach Node=104392.8
       1 4094.78    5400
Encroach Node=103452.2
       1 3293.31    5175
Encroach Node=102491.3
       1 3671.48    5124
Encroach Node=101376.5
       1 3784.21    5465
Encroach Node=100334.7
       1 4054.28    5175
Encroach Node=99259.29
       1    4894 5332.64
Encroach Node=98356.65
       1  4926.5    5450
Encroach Node=97381.72
       1 4728.49    5585
Encroach Node=96104.63
       1 4149.96    5260
Encroach Node=95283.76
       1    4955    5135
Encroach Node=95210.55
       14930.715    5165
Encroach Node=95179.92
       1  4932.5    5155
Encroach Node=95115.8
       1 4799.09    5150
Encroach Node=95042.8
       1    4909    5105
Encroach Node=94922.61
       1 4896.09    5105
Encroach Node=94046.74
       1 4514.23    5108
Encroach Node=93326.72
       1 4727.42 5221.05
Encroach Node=92670.8
       1 4592.73 5242.69
Encroach Node=92470.05
       1 4671.75    5150
Encroach Node=92418.29
       1  4784.5  5136.8
Encroach Node=92216.8
       1  4784.5  5136.8
Encroach Node=92026.57
       1  4784.5    5200
Encroach Node=91824.63
       1  4849.2    5380
Encroach Node=91609.41
       1 4411.75    5437
Encroach Node=90762.7
       1    4700    5500
Encroach Node=90125.32
       1 4350.51    5775
Encroach Node=89326.48
       1 4513.05    5600
Encroach Node=88667.88
       1 4796.79    5800
Encroach Node=88135.45
       1 4910.97    5800
Encroach Node=87008.24
       1  4910.5    5920
Encroach Node=85467.86
       1 4272.67 5222.64
Encroach Node=84443.81
       1    4887 5408.65
Encroach Node=83547.66
       1    4759    5206
Encroach Node=82895.54
       1    4873    5335
Encroach Node=82307.9
       1    4700    5177
Encroach Node=82220.89
       1    4700  5134.5
Encroach Node=82190.89
       1 4703.06 5131.42
Encroach Node=82163.1
       1 4688.57 5131.42
Encroach Node=82136.12
       1 4688.57 5113.01
Encroach Node=82016.09
       1    4700 5246.78
Encroach Node=81180.05
       1 4876.63 5443.71
Encroach Node=80360.35
       1 4875.25    5540
Encroach Node=79254.91
       1  4899.5    5385
Encroach Node=78275.05
       1    4800    5110
Encroach Node=77250.26
       1  4815.5 5292.54
Encroach Node=76035.24
       1 4638.57    5523
Encroach Node=74962.84
       1 4665.43    5425
Encroach Node=73498.96
       1 4703.67    5350
Encroach Node=72487.93
       1    4814    5680
Encroach Node=71225.56
       1 4646.46    5237
Encroach Node=70126.59
       1 4646.79    5170
Encroach Node=69033.28
       1 4485.89 5110.75
Encroach Node=68105.34
       1 4727.52    5500
Encroach Node=66946.82
       1    4924    5468
Encroach Node=65958.72
       1    4750    5435
Encroach Node=64961.1
       1 4913.25    5670
Encroach Node=63892.65
       1 4918.49    5512
Encroach Node=62629.87
       1 4759.01    5315
Encroach Node=61783.4
       1 4921.28    5365
Encroach Node=59436.15
       1 4622.24 5261.27
Encroach Node=58341.37
       1 4927.11 5246.81
Encroach Node=58271.63
       1    4819    5210
Encroach Node=58182.5
       1    4836    5192
Encroach Node=58089.67
       1 4896.15    5065
Encroach Node=57802.5
       1    4876 5126.85
Encroach Node=57445.25
       1 4908.31    5555
Encroach Node=56558.41
       1 4886.93    5900
Encroach Node=54943.36
       1 4832.67    5600
Encroach Node=54001.98
       1 4673.57 5244.47
Encroach Node=53006.21
       1 4838.81 5184.99
Encroach Node=51768.84
       1 4847.76 5128.25
Encroach Node=50893.4
       1 4897.42  5181.5
Encroach Node=49907.02
       1 4851.39 5274.33
Encroach Node=48722.71
       1 4892.56    5146
Encroach Node=47745.99
       1  4665.6 5406.48
Encroach Node=46386.08
       1 4576.03 5279.15
Encroach Node=45364.25
       1  4810.5    5650
Encroach Node=44198.85
       1 4830.61    5550
Encroach Node=43345.11
       1    4600    5420
Encroach Node=42270.17
       1    4200 5231.89
Encroach Node=40959.15
       1    4200    5700
Encroach Node=39965.81
       1    4400    6000
Encroach Node=38870.92
       1    4700    6000
Encroach Node=37939.04
       1 4408.02    5400
Encroach Node=36777.61
       1 4614.11    5485
Encroach Node=35491.18
       1 4792.97 5405.27
Encroach Node=34326.29
       1 4770.73    5300
Encroach Node=33267.79
       1    4798    5355
Encroach Node=33211.74
       1 3284.87 3722.58
Encroach Node=32942.1
       1 3284.87 3934.58
Encroach Node=32806.91
       1 3496.87 3934.58
Encroach Node=32526.8
       1  4705.5  5294.5
Encroach Node=31801.25
       1 4836.28    5179
Encroach Node=31750.97
       1 4836.28    5179
Encroach Node=31645.17
       1 4834.03    5177
Encroach Node=31582.5
       1 4834.03    5177
Encroach Node=31379.93
       1 4834.03    5265
Encroach Node=30585.5
       1 4766.55 5233.45
Encroach Node=29469.51
       1 4776.56 5223.44
Encroach Node=28381.91
       1 4767.72 5232.28
Encroach Node=27388.16
       1 4753.86 5246.14
Encroach Node=26325.42
       1 4809.28    5260
Encroach Node=25299.47
       1 4790.09    5300
Encroach Node=24186.67
       1 4757.73    5300
Encroach Node=23242.39
       1 4760.99 5239.01
Encroach Node=22040.03
       1 4825.39    5215
Encroach Node=20925.69
       1 4797.85    5850
Encroach Node=20092.01
       1 4857.41    6200
Encroach Node=18888.3
       1 4874.69    5810
Encroach Node=9775.511
       1 4574.06  5057.1
Encroach Node=5807.924
       1 3022.52 5277.89
Encroach Node=1797.325
       1 1630.67 4627.04
Computation Interval=1HOUR
Output Interval=1HOUR
Run HTab= 0
Run UNet= 0
Run PostProcess= 0
UNET Theta= 1
UNET ZTol= 0.02
UNET ZSATol= 0.1
UNET MxIter= 20
UNET MaxInSteps= 20
UNET DtIC= 0
UNET DtMin= 0
UNET MaxCRTS= 20
UNET WFStab= 2
UNET SFStab= 1
UNET WFX= 1
UNET SFX= 1
UNET Convert EG Bridges=-1
UNET Use Existing IB Tables=-1
Instantaneous Interval=1HOUR
DSS File=dss
Write IC File= 0
IC Time=0
Write Velocity= 0
Write Detailed= 0

--- Q100-00-00.p01 (plan) ---

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Plan Title=FEMA Effective June 2007
Short Identifier=FEMAeff0607
Geom File=g01
Flow File=f01

--- Q100-00-00.f02 (steady flow) ---

Flow Title=Floodway
Version=Version 3.0.1  Mar 2001
Number of Profiles= 2
Profile Names=1PCT_100yr,1PCTFloodway_100yrFW
River Rch & RM=Q100-00-00,Q100-00-00_0018 ,210517.6
    4012    4012
River Rch & RM=Q100-00-00,Q100-00-00_0018 ,207930
    3686    3686
River Rch & RM=Q100-00-00,Q100-00-00_0018 ,204084.9
    3277    3277
River Rch & RM=Q100-00-00,Q100-00-00_0018 ,198721.4
    3163    3163
River Rch & RM=Q100-00-00,Q100-00-00_0018 ,197117.3
    2991    2991
River Rch & RM=Q100-00-00,Q100-00-00_0018 ,194579.1
    4227    4227
River Rch & RM=Q100-00-00,Q100-00-00_0018 ,184514.9
    4227    4227
River Rch & RM=Q100-00-00,Q100-00-00_0018 ,183807.7
    4549    4549
River Rch & RM=Q100-00-00,Q100-00-00_0018 ,182706
    4873    4873
River Rch & RM=Q100-00-00,Q100-00-00_0018 ,181673.3
    5242    5242
River Rch & RM=Q100-00-00,Q100-00-00_0018 ,180577.6
    5628    5628
River Rch & RM=Q100-00-00,Q100-00-00_0018 ,179512.7
    5887    5887
River Rch & RM=Q100-00-00,Q100-00-00_0018 ,176298.9
    6001    6001
River Rch & RM=Q100-00-00,Q100-00-00_0018 ,174939.2
    6286    6286
River Rch & RM=Q100-00-00,Q100-00-00_0018 ,171624.7
    6398    6398
River Rch & RM=Q100-00-00,Q100-00-00_0018 ,170369.2
    6700    6700
River Rch & RM=Q100-00-00,Q100-00-00_0018 ,167085.7
    6874    6874
River Rch & RM=Q100-00-00,Q100-00-00_0018 ,161176.4
    7887    7887
River Rch & RM=Q100-00-00,Q100-00-00_0018 ,150456.5
    8162    8162
River Rch & RM=Q100-00-00,Q100-00-00_0018 ,142357
   10834   10834
River Rch & RM=Q100-00-00,Q100-00-00_0018 ,139838.1
   10903   10903
River Rch & RM=Q100-00-00,Q100-00-00_0018 ,138603.7
   11029   11029
River Rch & RM=Q100-00-00,Q100-00-00_0018 ,136370.3
   11170   11170
River Rch & RM=Q100-00-00,Q100-00-00_0018 ,133922.9
   11243   11243
River Rch & RM=Q100-00-00,Q100-00-00_0018 ,132651.6
   11374   11374
River Rch & RM=Q100-00-00,Q100-00-00_0018 ,130408.4
   11496   11496
River Rch & RM=Q100-00-00,Q100-00-00_0018 ,128345.9
   11624   11624
River Rch & RM=Q100-00-00,Q100-00-00_0018 ,126201.7
   11760   11760
River Rch & RM=Q100-00-00,Q100-00-00_0018 ,123942
   18112   18112
River Rch & RM=Q100-00-00,Q100-00-00_0018 ,117495.2
   18978   18978
River Rch & RM=Q100-00-00,Q100-00-00_0018 ,107906.6
   19072   19072
River Rch & RM=Q100-00-00,Q100-00-00_0018 ,106890.1
   19306   19306
River Rch & RM=Q100-00-00,Q100-00-00_0018 ,104392.8
   19507   19507
River Rch & RM=Q100-00-00,Q100-00-00_0018 ,96104.63
   19844   19844
River Rch & RM=Q100-00-00,Q100-00-00_0018 ,92026.57
   20271   20271
River Rch & RM=Q100-00-00,Q100-00-00_0018 ,76035.24
   20517   20517
River Rch & RM=Q100-00-00,Q100-00-00_0018 ,68105.34
   20875   20875
River Rch & RM=Q100-00-00,Q100-00-00_0018 ,57445.25
   22282   22282
River Rch & RM=Q100-00-00,Q100-00-00_0018 ,42270.17
   23219   23219
River Rch & RM=Q100-00-00,Q100-00-00_0018 ,31379.93
   24193   24193
River Rch & RM=Q100-00-00,Q100-00-00_0018 ,24186.67
   13302   13302
River Rch & RM=Q100-00-00,Q100-00-00_0018 ,23242.39
   11226   11226
River Rch & RM=Q100-00-00,Q100-00-00_0018 ,18888.3
   11962   11962
River Rch & RM=Q100-00-00,Q100-00-00_0018 ,9775.511
   12646   12646
Boundary for River Rch & Prof#=Q100-00-00,Q100-00-00_0018 , 1
Up Type= 0
Dn Type= 1
Dn Known WS=1.5
Boundary for River Rch & Prof#=Q100-00-00,Q100-00-00_0018 , 2
Up Type= 0
Dn Type= 1
Dn Known WS=2.5
DSS Import GetInterval= 0
DSS Import GetPeak= 0
DSS Import FillOption= 0

--- Q100-00-00.f01 (steady flow) ---

Flow Title=FEMA Effective June 2007
Version=Version 3.0.1  Mar 2001
Number of Profiles= 4
Profile Names=10PCT_10yr,2PCT_50yr,1PCT_100yr,0.2PCT_500yr
River Rch & RM=Q100-00-00,Q100-00-00_0018 ,210517.6
    1622    3125    4012    6948
River Rch & RM=Q100-00-00,Q100-00-00_0018 ,207930
    1614    2911    3686    6377
River Rch & RM=Q100-00-00,Q100-00-00_0018 ,204084.9
    1601    2636    3277    5659
River Rch & RM=Q100-00-00,Q100-00-00_0018 ,198721.4
    1598    2559    3163    5461
River Rch & RM=Q100-00-00,Q100-00-00_0018 ,197117.3
    1592    2442    2991    5160
River Rch & RM=Q100-00-00,Q100-00-00_0018 ,194579.1
    2272    3493    4227    6767
River Rch & RM=Q100-00-00,Q100-00-00_0018 ,184514.9
    2272    3493    4227    6767
River Rch & RM=Q100-00-00,Q100-00-00_0018 ,183807.7
    2431    3760    4549    7305
River Rch & RM=Q100-00-00,Q100-00-00_0018 ,182706
    2589    4029    4873    7848
River Rch & RM=Q100-00-00,Q100-00-00_0018 ,181673.3
    2768    4336    5242    8468
River Rch & RM=Q100-00-00,Q100-00-00_0018 ,180577.6
    2954    4656    5628    9118
River Rch & RM=Q100-00-00,Q100-00-00_0018 ,179512.7
    3073    4869    5887    9551
River Rch & RM=Q100-00-00,Q100-00-00_0018 ,176298.9
    3124    4962    6001    9740
River Rch & RM=Q100-00-00,Q100-00-00_0018 ,174939.2
    3253    5196    6286   10217
River Rch & RM=Q100-00-00,Q100-00-00_0018 ,171624.7
    3304    5287    6398   10404
River Rch & RM=Q100-00-00,Q100-00-00_0018 ,170369.2
    3439    5535    6700   10909
River Rch & RM=Q100-00-00,Q100-00-00_0018 ,167085.7
    3537    5680    6874   11111
River Rch & RM=Q100-00-00,Q100-00-00_0018 ,161176.4
    4044    6549    7887   12154
River Rch & RM=Q100-00-00,Q100-00-00_0018 ,150456.5
    4154    6806    8162   12482
River Rch & RM=Q100-00-00,Q100-00-00_0018 ,142357
    6212    9005   10834   16733
River Rch & RM=Q100-00-00,Q100-00-00_0018 ,139838.1
    6311    9077   10903   16890
River Rch & RM=Q100-00-00,Q100-00-00_0018 ,138603.7
    6493    9207   11029   17178
River Rch & RM=Q100-00-00,Q100-00-00_0018 ,136370.3
    6699    9353   11170   17499
River Rch & RM=Q100-00-00,Q100-00-00_0018 ,133922.9
    6809    9429   11243   17669
River Rch & RM=Q100-00-00,Q100-00-00_0018 ,132651.6
    7007    9565   11374   17971
River Rch & RM=Q100-00-00,Q100-00-00_0018 ,130408.4
    7193    9692   11496   18254
River Rch & RM=Q100-00-00,Q100-00-00_0018 ,128345.9
    7393    9826   11624   18553
River Rch & RM=Q100-00-00,Q100-00-00_0018 ,126201.7
    7609    9969   11760   18874
River Rch & RM=Q100-00-00,Q100-00-00_0018 ,123942
   11142   15677   18112   26144
River Rch & RM=Q100-00-00,Q100-00-00_0018 ,117495.2
   11560   16431   18978   27668
River Rch & RM=Q100-00-00,Q100-00-00_0018 ,107906.6
   11605   16513   19072   27835
River Rch & RM=Q100-00-00,Q100-00-00_0018 ,106890.1
   11717   16716   19306   28249
River Rch & RM=Q100-00-00,Q100-00-00_0018 ,104392.8
   11887   16938   19507   28255
River Rch & RM=Q100-00-00,Q100-00-00_0018 ,96104.63
   12189   17302   19844   28427
River Rch & RM=Q100-00-00,Q100-00-00_0018 ,92026.57
   12407   17680   20271   28968
River Rch & RM=Q100-00-00,Q100-00-00_0018 ,76035.24
   12626   17953   20517   29223
River Rch & RM=Q100-00-00,Q100-00-00_0018 ,68105.34
   12863   18307   20875   29584
River Rch & RM=Q100-00-00,Q100-00-00_0018 ,57445.25
   13793   19685   22282   31170
River Rch & RM=Q100-00-00,Q100-00-00_0018 ,42270.17
   14220   20344   23219   34183
River Rch & RM=Q100-00-00,Q100-00-00_0018 ,31379.93
   14328   20658   24193   36237
River Rch & RM=Q100-00-00,Q100-00-00_0018 ,24186.67
    8640   11710   13302   18633
River Rch & RM=Q100-00-00,Q100-00-00_0018 ,23242.39
    5805    9207   11226   18146
River Rch & RM=Q100-00-00,Q100-00-00_0018 ,18888.3
    6056    9775   11962   19336
River Rch & RM=Q100-00-00,Q100-00-00_0018 ,9775.511
    6286   10301   12646   20442
Boundary for River Rch & Prof#=Q100-00-00,Q100-00-00_0018 , 1
Up Type= 0
Dn Type= 1
Dn Known WS=1.5
Boundary for River Rch & Prof#=Q100-00-00,Q100-00-00_0018 , 2
Up Type= 0
Dn Type= 1
Dn Known WS=1.5
Boundary for River Rch & Prof#=Q100-00-00,Q100-00-00_0018 , 3
Up Type= 0
Dn Type= 1
Dn Known WS=1.5
Boundary for River Rch & Prof#=Q100-00-00,Q100-00-00_0018 , 4
Up Type= 0
Dn Type= 1
Dn Known WS=1.5
DSS Import GetInterval= 0
DSS Import GetPeak= 0
DSS Import FillOption= 0

--- Q100-00-00.g01 (geometry) ---

Geom Title=Q100-00-00 June 2007
Version=Version 3.0.1  Mar 2001

River Reach=Q100-00-00      ,Q100-00-00_0018
Reach XY= 30
     3220309.753    13952250.322        3216761.       13945573.
      3217140.02       13935719.      3223374.25       13929718.
      3227483.75       13931461.        3234512.       13929748.
        3240473.       13920248.      3241016.75       13917095.
       3238880.5       13915820.       3235763.5       13903705.
      3239453.25       13898194.        3243271.       13885144.
      3251421.25       13880443.       3257012.5       13873387.
      3265514.25       13870571.      3265525.75       13866130.
        3260949.       13859260.      3263363.25       13856206.
      3262623.75       13850708.       3264833.5       13849094.
      3263183.75       13844919.        3259951.       13843075.
       3260289.5       13838178.      3255184.75       13830663.
      3259417.75       13829758.      3259181.75       13826688.
        3261862.       13825772.      3260474.25       13823571.
      3264929.75       13824035.      3260608.75       13814808.

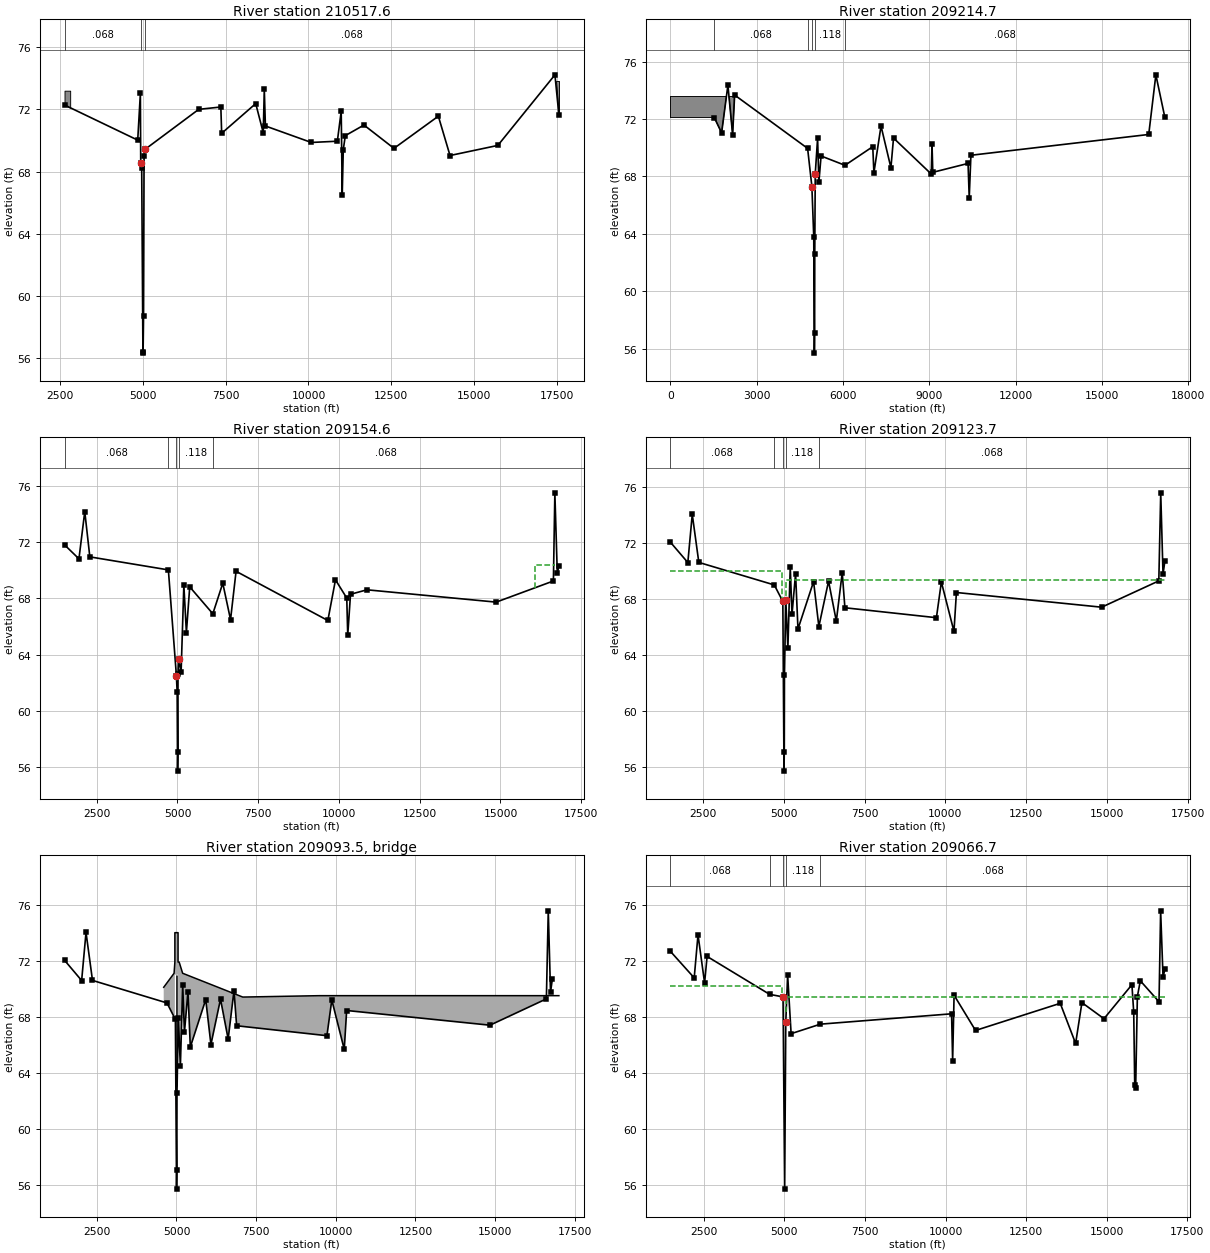
Type RM Length L Ch R = 1 ,210517.6,1373.48,1302.85,1285.61
XS GIS Cut Line= 6
     3220467.929    13947962.674     3218375.555    13947367.283
       3218219.9      13947386.4       3218148.6     13947396.42
     3217967.286    13947435.328 3205887.763789513949941.9475695
#Sta/Elev= 30
 2634.62   72.28    4845   70.02    4925   73.02    4936   68.52    4965   68.22
    5002   56.42    5007   56.32 5021.01   58.72    5037   69.02    5062   69.42
  6687.4      72 7354.48   72.15  7379.6   70.46 8407.96   72.37  8635.8   70.49
 8666.44    73.3  8700.3   70.93 10085.8   69.8710872.34   69.9510988.98   71.88
11019.62    66.511051.46   69.4111113.28   70.3111676.24   70.9912582.22   69.49
13921.62   71.56 14274.3   69.0315718.56   69.6817442.18   74.2217561.18   71.65
#Mann= 3 ,-1 , 0
 2634.62    .068       0    4936     .04       0    5062    .068       0
#XS Ineff= 1 ,-1
 8396.2717216.78   72.24
Permanent Ineff=
       F
#Block Obstruct= 2 ,-1
 2634.62 2805.62    73.217421.9117561.18   73.83
Bank Sta=4936,5062
XS Rating Curve= 0
Exp/Cntr=.3,.1

Type RM Length L Ch R = 1 ,209214.7,144.09,60.16,89.53
XS GIS Cut Line= 6
     3220541.712    13947705.213      3217573.66    13946336.111
      3217418.97     13946409.68     3217273.134    13946486.374
     3217042.043    13946486.374 3205339.364258513948200.8213388
#Sta/Elev= 30
 1523.48   72.11 1778.04   71.04 1997.08   74.37  2160.5   70.92 2231.18   73.68
  4767.9   69.96  4916.5    67.3 4981.49   63.78  5002.5   55.68  5011.5   57.08
  5016.5   62.58  5033.5   68.18 5115.18   70.66 5159.42   67.59 5235.74   69.43
  6068.1   68.78 7032.74   70.08  7072.4   68.26  7319.9   71.52 7663.66   68.61
 7754.62   70.68 9067.58   68.17  9092.5   70.28 9120.04   68.2910346.04   68.91
10386.52   66.51 10445.2   69.4816626.84   70.9316874.84   75.0917186.84   72.13
#Mann= 5 ,-1 , 0
 1523.48    .068       0  4767.9    .118       0  4916.5     .04       0
  5033.5    .118       0  6068.1    .068       0
#XS Ineff= 1 ,-1
 7321.6816783.22   71.28
Permanent Ineff=
       F
#Block Obstruct= 2 , 0
       0  2218.3   73.5816909.09       0   74.28
Bank Sta=4916.5,5033.5
XS Rating Curve= 0
Exp/Cntr=.3,.1

Type RM Length L Ch R = 1 ,209154.6,34.03,30.88,38.27
XS GIS Cut Line= 6
     3220533.656    13947643.955     3217606.023     13946281.18
     3217304.631    13946396.655     3217224.027    13946421.138
     3217033.024    13946414.064      3205568.32    13945872.809
#Sta/Elev= 30
 1502.84   71.83 1949.52   70.83 2129.94    74.2 2286.64   70.97  4718.1   70.04
  4966.5    62.5    4990    61.3  5002.5   55.68  5011.5   57.08  5016.5   62.58
  5033.5    63.7 5112.04   62.72 5197.22   68.96 5276.24   65.57    5379   68.83
  6094.3   66.91 6402.48   69.09 6642.74   66.49 6813.94   69.94  9655.2   66.43
 9891.58   69.3310240.86   68.03 10270.9   65.3810356.98    68.310866.04   68.62
   14866   67.7416637.98   69.2516683.02   75.5416758.12   69.8116807.72   70.32
#Mann= 5 ,-1 , 0
 1502.84    .068       0  4718.1    .118       0  4966.5     .04       0
  5033.5    .118       0  6094.3    .068       0
#XS Ineff= 2 ,-1
16056.6316674.27   70.3816674.2716807.72   69.74
Permanent Ineff=
       F       F
#Block Obstruct= 2 , 0
            2375   72.8816692.04           74.57
Bank Sta=4966.5,5033.5
XS Rating Curve= 0
Exp/Cntr=.5,.3

Type RM Length L Ch R = 1 ,209123.7,63.94,57.01,70.73
XS GIS Cut Line= 6
     3220529.021    13947608.706     3217607.199    13946248.637
       3217294.8    13946368.288     3217220.115    13946390.973
     3217034.728    13946384.107     3205561.722    13945838.061
#Sta/Elev= 30
 1487.06   72.03 2024.82   70.58 2161.88   74.02 2364.98   70.59 4701.52   68.98
  4966.5    67.8  5002.5   55.68  5011.5   57.08  5016.5   62.58  5058.5    67.9
  5122.5   64.44 5195.68   70.27  5249.9   66.87 5360.82   69.79 5434.92   65.83
 5918.46   69.22 6081.56   66.01 6381.98   69.25 6622.26    66.4 6805.24   69.86
 6887.94   67.35  9721.4   66.64  9874.7   69.19   10265   65.6610340.56   68.44
14837.78   67.3916607.62   69.2716666.68   75.56 16737.8   69.74   16794   70.67
#Mann= 5 ,-1 , 0
 1487.06    .068       0 4701.52    .118       0  4966.5     .04       0
  5058.5    .118       0 6081.56    .068       0
#XS Ineff= 2 , 0
       0    4946      70 5056.35       0    69.3
Permanent Ineff=
       F       F
#Block Obstruct= 2 , 0
         2428.97   72.7616672.15           74.02
Bank Sta=4966.5,5058.5
XS Rating Curve= 0
Exp/Cntr=.5,.3

Type RM Length L Ch R = 3 ,209093.5,,,
Node Photo=G:\C2001-041_Harris_County_FEMA\3-Cedar_Bayou\Cedar_Bayou\Survey _info\1301s01_Huffman_Eastgate\131S01P8.JPG
BEGIN DESCRIPTION:
Huffman Eastgate Road
END DESCRIPTION:
Bridge Culvert--1,0,-1,-1, 0
Deck Dist Width WeirC Skew NumUp NumDn MinLoCord MaxHiCord MaxSubmerge Is_Ogee
14.7,31,2.6,0, 12, 12, , , .95, 0, 0,0,,
    4600    4925  4949.9    4950    5000    5050  5050.1    5085    5194    7080
    9480   17000
    70.1    71.1    71.9      74      74      74    71.9    71.9    71.1    69.4
    69.5    69.5
       0       0       0      71      71      71       0       0       0       0
       0       0
    4400    4925  4949.9    4950    5000    5050  5050.1    5085    5194    7080
    9480   17000
    70.1    71.1    71.9      74      74      74    71.9    71.9    71.1    69.4
    69.5    69.5
       0       0       0      71      71      71       0       0       0       0
       0       0
Pier Skew, UpSta & Num, DnSta & Num=  ,4980, 2 ,4980, 2 , 0 , 0 , 0 ,,
     1.4     1.4
       0      72
     1.4     1.4
       0      72
Pier Skew, UpSta & Num, DnSta & Num=  ,5020, 2 ,5020, 2 , 0 , 0 , 0 ,,
     1.4     1.4
       0      72
     1.4     1.4
       0      72
BR Coef=-1 , 1 , 1 ,1.25, 0 ,,,.8,0,2,0,
WSPro=,,,, 1 ,,,, 0 ,,,, 0 ,,,,-1 ,-1 ,-1 , 0 , 0 , 0 , 0 , 0
BC Design=,, 0 ,, 0 ,,,,,,
BC HTab HWMax=75.56

Type RM Length L Ch R = 1 ,209066.7,117.34,122.18,154.43
XS GIS Cut Line= 6
       3220519.8    13947538.585      3217613.73    13946185.848
      3217264.64     13946319.42     3217209.689    13946336.111
     3217040.309    13946329.838     3205523.961    13945639.183
#Sta/Elev= 30
 1463.38   72.67 2200.26   70.78 2318.16   73.86 2522.26   70.42 2600.44   72.31
 4540.92    69.6  4957.5   69.42  5007.5   55.68  5042.5   67.62 5100.08   70.98
 5207.86   66.79  6114.9   67.47   10188   68.21 10220.9   64.8610265.52   69.54
10931.26   67.0213559.96   68.9614037.74   66.0914233.08   69.0114917.98   67.86
15784.92   70.2915841.24   68.3115871.78   63.1515901.08   62.8915953.92   69.44
16045.66   70.5716626.16   69.0716676.24   75.5716750.88   70.8216806.62   71.38
#Mann= 5 ,-1 , 0
 1463.38    .068       0 4540.92    .118       0  4957.5     .04       0
  5042.5    .118       0  6114.9    .068       0
#XS Ineff= 2 , 0
       0 4939.59    70.2 5054.77       0    69.4
Permanent Ineff=
       F       F
#Block Obstruct= 2 , 0
         2324.66   73.35 16678.9           73.96
Bank Sta=4957.5,5042.5
XS Rating Curve= 0
Exp/Cntr=.5,.3

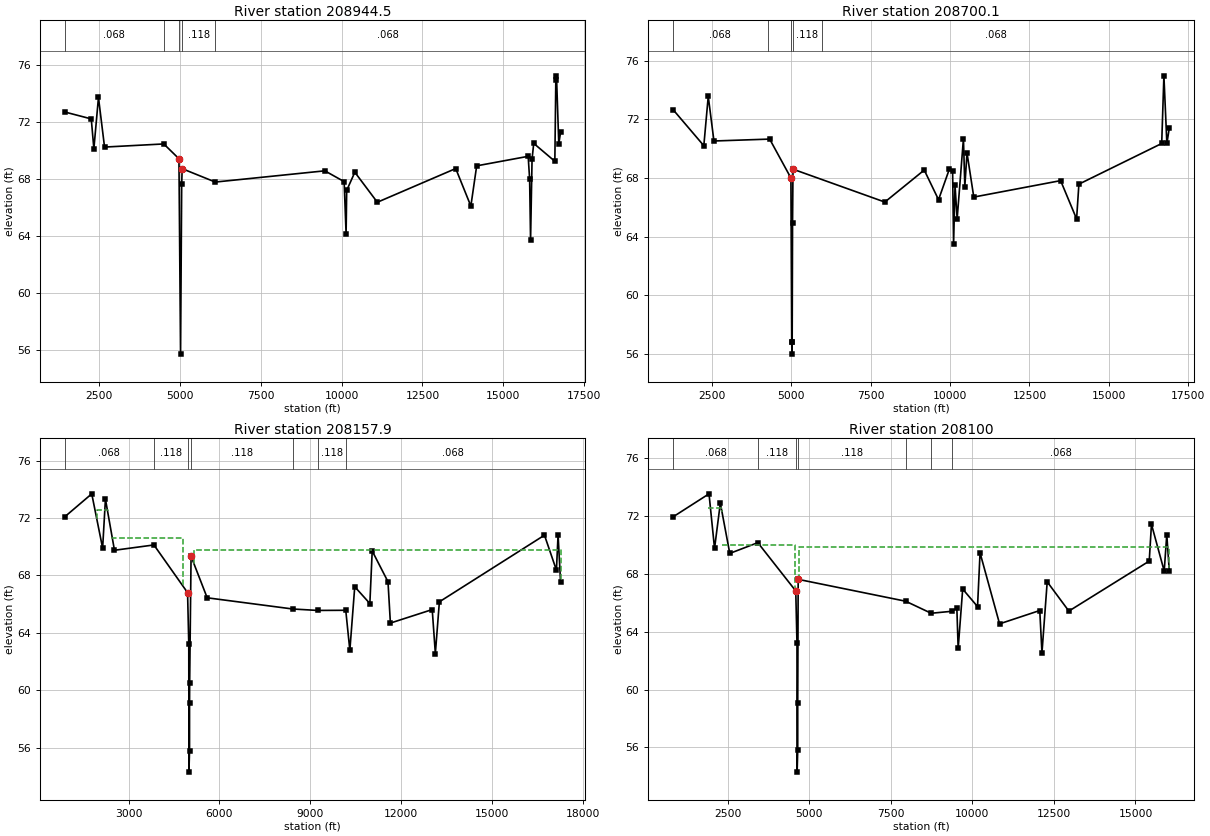
Type RM Length L Ch R = 1 ,208944.5,273.72,244.38,217.27
XS GIS Cut Line= 6
     3220510.715    13947469.506     3217610.391    13946102.369
     3217300.654    13946176.528     3217194.045     13946215.45
     3217042.043     13946209.82     3205500.823    13945517.324
#Sta/Elev= 30
 1422.86   72.71 2248.65   72.22 2329.04   70.12  2471.5   73.73 2659.51   70.24
 4493.36   70.46  4962.5   69.42  5012.5   55.68  5047.5   67.62  5062.5   68.72
 6087.57   67.78 9478.83   68.5710076.31   67.8110136.42   64.1310154.74   67.19
10406.91   68.4711103.34   66.3613529.95   68.7313998.35   66.0914178.67   68.92
 15772.5   69.5915817.68   67.9815846.67   63.6915892.79   69.3915944.12    70.5
16598.02   69.2416628.07   74.9416649.14   75.2516719.89   70.4616775.38   71.28
#Mann= 5 ,-1 , 0
 1422.86    .068       0 4493.36    .118       0  4962.5     .04       0
  5062.5    .118       0 6087.57    .068       0
#Block Obstruct= 2 , 0
          2496.5   73.2516637.62           73.72
Bank Sta=4962.5,5062.5
XS Rating Curve= 0
Exp/Cntr=.3,.1

Type RM Length L Ch R = 1 ,208700.1,281.49,542.22,555.44
XS GIS Cut Line= 6
     3220508.539    13947452.961     3217286.839    13945921.333
      3217173.27     13945970.41      3217112.63     13945994.91
     3216963.627    13946057.423     3205402.286     13944245.05
#Sta/Elev= 30
 1282.32   72.64 2244.16    70.2 2383.52   73.56 2562.94   70.52 4317.94   70.65
  4987.3      68  5012.5    56.8 5019.81      56  5026.6    56.8 5038.51    64.9
  5052.7    68.6 7945.04   66.36 9186.22   68.54 9636.86   66.52 9973.24   68.58
 10079.9   68.4610110.28   63.4710155.82    67.510222.76   65.2110420.76   70.68
 10464.4   67.4110532.84   69.71 10746.6    66.713481.28   67.82 13984.4   65.21
14056.94   67.5816664.94   70.3516734.08   74.96 16827.7   70.35 16902.8   71.39
#Mann= 5 ,-1 , 0
 1282.32    .068       0 4250.22    .118       0  4987.3     .04       0
  5052.7    .118       0 5968.48    .068       0
#Block Obstruct= 2 , 0
         2349.65   72.8916740.83            73.2
Bank Sta=4987.3,5052.7
XS Rating Curve= 0
Exp/Cntr=.3,.1

Type RM Length L Ch R = 1 ,208157.9,54.74,57.9,61.07
XS GIS Cut Line= 6
     3220492.046    13947327.543     3218284.804    13946301.179
     3216809.319    13945615.082     3216691.488    13945560.136
     3208220.655    13941616.398     3205636.721    13940413.404
#Sta/Elev= 30
  887.23   72.07 1784.38   73.68 2143.87    69.9 2236.63   73.31 2535.07   69.75
  3838.5   70.12    4950    66.8    4990    63.2    4995    54.3    5015    55.8
  5015.1    59.1    5019    60.5 5065.54   69.33 5597.99   66.44 8424.58   65.66
 9243.86   65.5610176.02   65.5710311.16   62.7810472.83   67.2110972.29   66.04
11049.75    69.711571.13   67.56 11650.8   64.6813032.51   65.6213135.93   62.56
13268.98   66.16 16740.9    70.817136.04   68.3617190.36   70.8417272.78   67.52
#Mann= 7 ,-1 , 0
  887.23    .068       0  3838.5    .118       0    4950     .04       0
 5065.54    .118       0 8424.58    .068       0 9243.86    .118       0
10176.02    .068       0
#XS Ineff= 3 ,-1
 1951.05 2307.69   72.53 2412.59 4783.22    70.6    516017271.94   69.78
Permanent Ineff=
       F       F       F
#Block Obstruct= 2 , 0
         1786.88   73.4817262.29           73.46
Bank Sta=4950,5065.54
XS Rating Curve= 0
Exp/Cntr=.5,.3

Type RM Length L Ch R = 1 ,208100  ,178.15,170.05,195.35
XS GIS Cut Line= 6
     3220484.322     13947268.81     3218305.886    13946255.841
     3216830.425    13945569.755     3216712.606    13945514.815
     3208241.758     13941571.07     3205623.179    13940351.946
#Sta/Elev= 30
 836.329   71.921931.584    73.52100.637   69.73 2278.22   72.862567.576   69.39
3427.447   70.13 4589.56    66.84626.647    63.24631.283    54.34649.827    55.8
 4649.92    59.14663.735    67.67958.732   66.098739.375   65.269387.069    65.4
  9525.6   65.649566.154   62.839704.685   66.9310159.93   65.7210236.74   69.43
10834.85   64.5312066.56   65.4512133.86   62.5312294.44   67.4312958.45   65.41
15421.01   68.8615489.21    71.415879.93   68.1715958.77   70.69 16034.7   68.21
#Mann= 7 ,-1 , 0
 836.329    .068       03427.447    .118       0 4589.56     .04       0
4663.735    .118       07958.732    .068       08739.375    .118       0
9387.069    .068       0
#XS Ineff= 4 ,-1
 1909.09 2328.67   72.53 836.329 1909.09   69.97 2328.67 4580.18   69.97
 4697.43 16028.8    69.8
Permanent Ineff=
       F       F       F       F
#Block Obstruct= 2 , 0
         1928.51   73.4115533.96           73.26
Bank Sta=4589.56,4663.735
XS Rating Curve= 0
Skew Angle= 22
Exp/Cntr=.5,.3