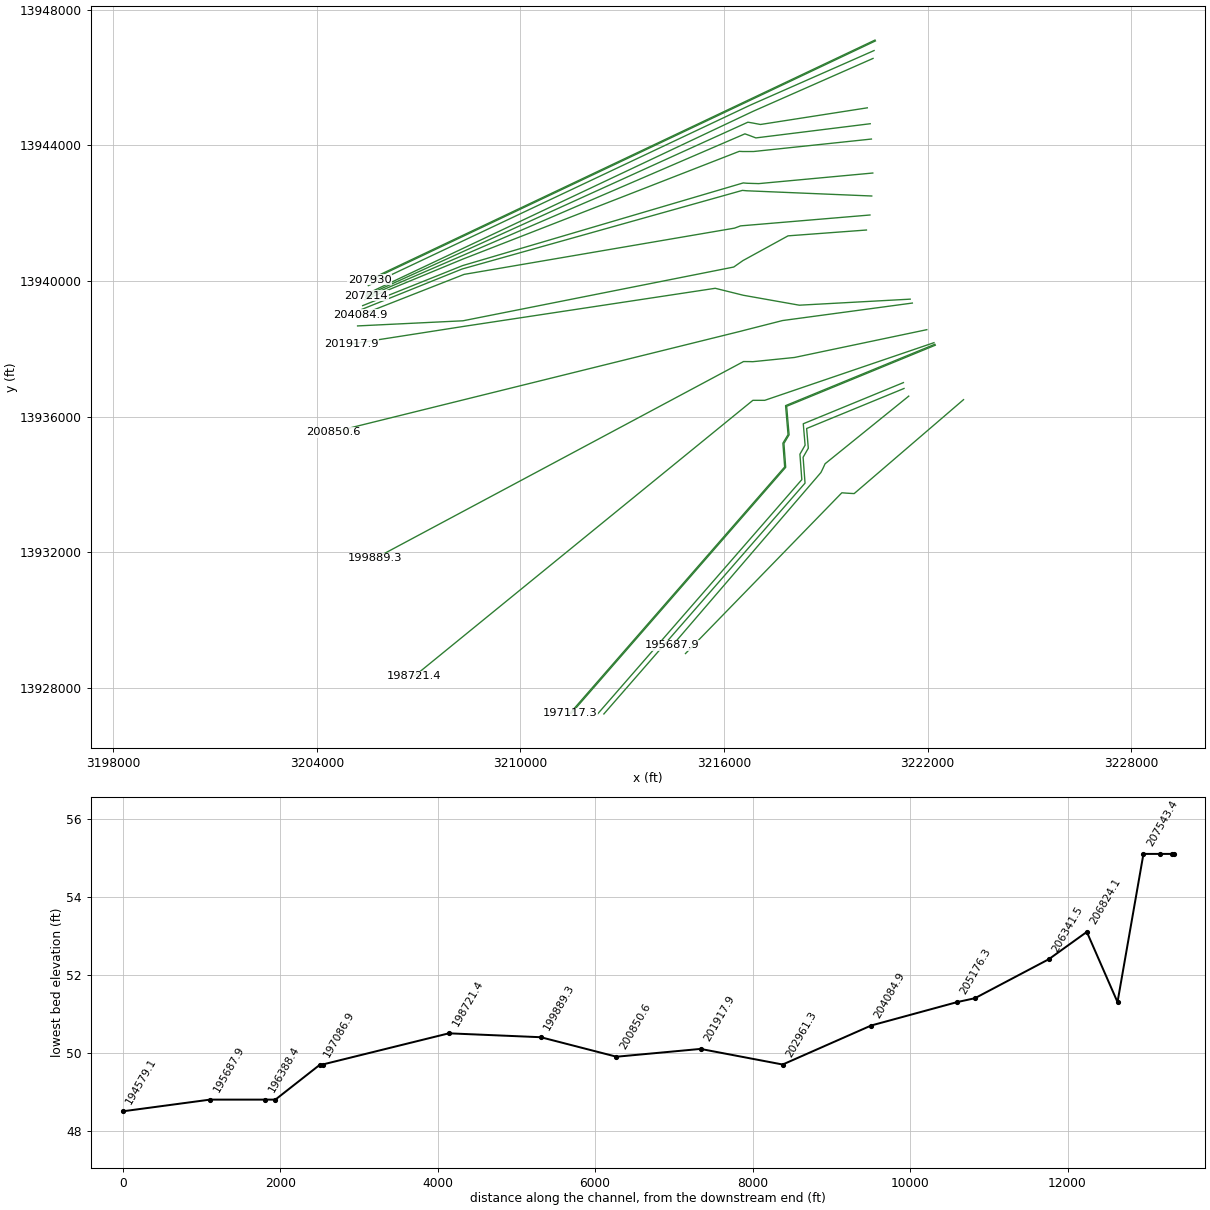
HEC-RAS study Q100-00-00.prj: Q100-00-00

--- Q100-00-00.g01 (geometry) --- (continued)

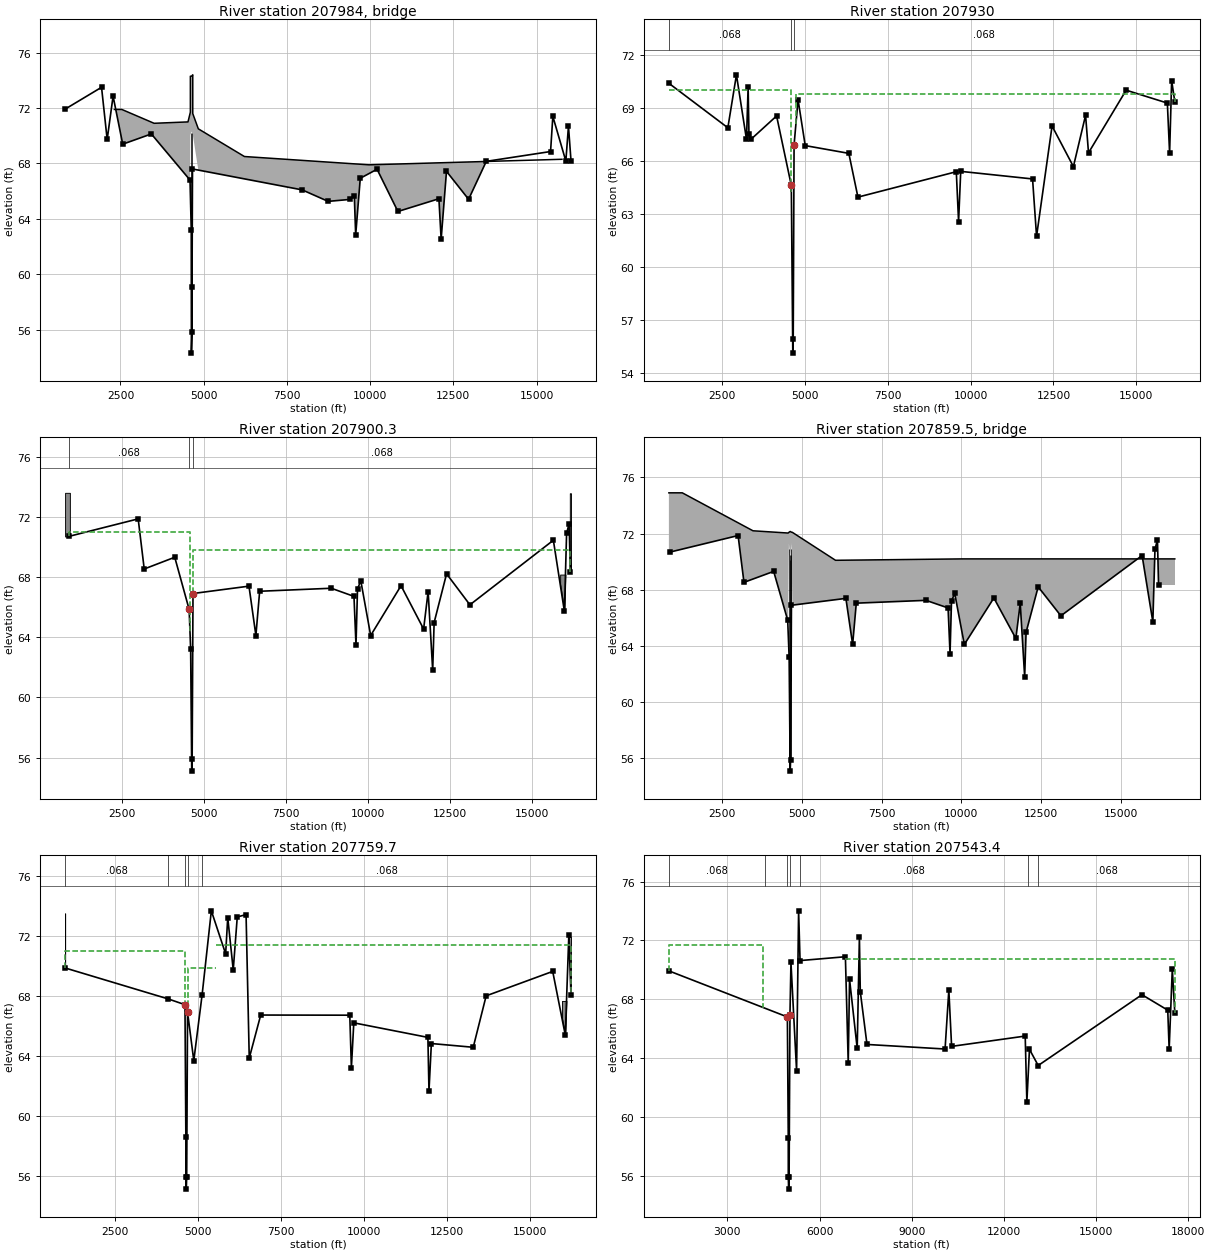
Type RM Length L Ch R = 3 ,207984  ,,,
Node Photo=G:\C2001-041_Harris_County_FEMA\3-Cedar_Bayou\Cedar_Bayou\Survey _info\121s50_fm1960_hwy\121S50P1.jpg
BEGIN DESCRIPTION:
FM 1960 Highway
END DESCRIPTION:
Bridge Culvert--1,0,-1,-1, 0
Deck Dist Width WeirC Skew NumUp NumDn MinLoCord MaxHiCord MaxSubmerge Is_Ogee
94.3,43.7,2.6,22, 13, 13, , , .95, 0, 0,0,,
 2317.962540.4843510.3184528.3664599.6674599.7594635.919 4672.084672.1724838.973
6223.2589967.22715762.13
    71.9    71.9    70.9      71    71.7    74.3    74.3    74.4    71.6    70.5
    68.5    67.9    68.3
       0       0       0       0   70.05   70.05    70.3    70.1    70.1       0
       0       0       0
 834.4652540.4843510.3184528.3664599.6674599.7594635.919 4672.084672.1724838.973
6223.2589967.22715762.13
      73    71.9    70.9      71    71.7    74.3    74.3    74.4    71.6    70.5
    68.5    67.9    68.3
       0       0       0       0   70.05   70.05    70.3    70.1    70.1       0
       0       0       0
Pier Skew, UpSta & Num, DnSta & Num=  ,4622.012, 2 ,4622.012, 2 , 0 , 0 , 0 ,,
     1.3     1.3
       0      72
     1.3     1.3
       0      72
Pier Skew, UpSta & Num, DnSta & Num=  ,4649.827, 2 ,4649.827, 2 , 0 , 0 , 0 ,,
     1.3     1.3
       0      72
     1.3     1.3
       0      72
BR Coef=-1 , 1 , 1 ,.9, 0 ,,,.8,0,2,0,
WSPro=,,,, 1 ,,,, 0 ,,,, 0 ,,,,-1 ,-1 ,-1 , 0 , 0 , 0 , 0 , 0
BR U #Sta/Elev= 30
  836.33   71.92 1931.58    73.5 2100.64   69.73 2278.22   72.86 2567.58   69.39
 3427.45   70.13 4589.56    66.8 4626.65    63.2 4631.28    54.3 4649.83    55.8
 4649.92    59.1 4663.74    67.6 7958.73   66.09 8739.38   65.26 9387.07    65.4
  9525.6   65.64 9566.15   62.83 9704.69   66.9310208.76   67.5810834.85   64.53
12066.56   65.4512133.86   62.5312294.44   67.4312958.45   65.4113489.88   68.15
15421.01   68.8615489.21    71.415879.93   68.1715958.77   70.69 16034.7   68.21
BR U #Mann= 7
  836.33    .072 3427.45    .122 4589.56    .015 4663.74    .122 7958.73    .072
 8739.38    .122 9387.07    .072
BR U Banks=,4663.74
BR D #Sta/Elev= 30
  884.49   70.39  2665.3   67.87 2924.76   70.87 3228.68   67.21 3277.68   70.19
 3302.99    67.5 3365.71   67.22 4137.64   68.54 4582.33    64.6 4626.65    55.1
 4639.63    55.9 4665.59    66.9 4786.01   69.46 5002.31   66.86 6319.44   66.42
 6594.38   63.94 9565.65   65.38 9634.63   62.55 9699.23    65.411869.22   64.97
 11989.9   61.7212458.12   67.9713102.67   65.6713470.53   68.5813558.79   66.45
14696.41      7015940.46   69.2716008.46   66.4416070.45   70.5416165.27   69.35
BR D #Mann= 3
  884.49    .072 4582.33    .015 4665.59    .072
BR D Banks=4582.33,4665.59
BC Design=,, 0 ,, 0 ,,,,,,
BC HTab HWMax=73.5

Type RM Length L Ch R = 1 ,207930  ,31.13,29.68,31.6
XS GIS Cut Line= 4
     3220449.174    13947103.003     3218352.283    13946109.402
     3208176.874    13941287.834     3205555.727    13940045.816
#Sta/Elev= 30
 884.487   70.392665.302   67.872924.755   70.873228.677   67.213277.678   70.19
 3302.99    67.53365.705   67.224137.641   68.544582.328    64.64626.647    55.1
4639.628    55.94665.589    66.94786.012   69.465002.306   66.866319.444   66.42
6594.382   63.949565.653   65.389634.627   62.559699.225    65.411869.22   64.97
 11989.9   61.7212458.12   67.9713102.67   65.6713470.53   68.5813558.79   66.45
14696.41      7015940.46   69.2716008.46   66.4416070.45   70.5416165.27   69.35
#Mann= 3 , 0 , 0
 884.487    .068       04582.328     .04       04665.589    .068       0
#XS Ineff= 2 , 0
       0    4584      70 4720.23       0   69.81
Permanent Ineff=
       F       F
#Block Obstruct= 2 , 0
           890.6   74.8816163.34           74.92
Bank Sta=4582.328,4665.589
XS Rating Curve= 0
Skew Angle= 22
Exp/Cntr=.5,.3

Type RM Length L Ch R = 1 ,207900.3,153,140.62,145.55
XS GIS Cut Line= 4
     3220461.851     13947077.65      3218364.96    13946084.049
      3208189.55    13941262.481     3205548.011      13940010.8
#Sta/Elev= 30
  879.35   70.693003.056   71.86 3187.26   68.534118.347   69.314557.461   65.84
4603.097    63.24635.919    55.1  4648.9    55.94674.861    66.9 6381.64   67.39
6592.991   64.116707.424   67.058891.425   67.259583.976   66.719645.531   63.46
9691.704    67.29791.859   67.7510093.05   64.1111018.98   67.42 11707.8   64.54
11845.21   67.0311984.71    61.812028.31   64.97 12407.8   68.2113119.66   66.15
15664.75   70.4416001.65   65.7116067.97   70.8916145.92   71.5516181.06   68.31
#Mann= 3 , 0 , 0
  879.35    .068       04557.461     .04       04674.861    .068       0
#XS Ineff= 2 , 0
       04584.924      71 4681.23       0    69.8
Permanent Ineff=
       F       F
#Block Obstruct= 3 ,-1
  773.96  920.02   73.5915871.1916060.89   68.1616166.0716202.11   73.56
Bank Sta=4557.461,4674.861
XS Rating Curve= 0
Skew Angle= 22
Exp/Cntr=.5,.3

Type RM Length L Ch R = 3 ,207859.5,,,
Node Photo=G:\C2001-041_Harris_County_FEMA\3-Cedar_Bayou\Cedar_Bayou\Survey _info\121s51_fm1960_railroad\121S51P8.jpg
BEGIN DESCRIPTION:
Union Pacific Railroad
END DESCRIPTION:
Bridge Culvert--1,0,-1,-1, 0
Deck Dist Width WeirC Skew NumUp NumDn MinLoCord MaxHiCord MaxSubmerge Is_Ogee
33,15.6,2.6,22, 11, 11, , , .95, 0, 0,0,,
 834.465 1254.483469.5224569.0694596.6074635.9194675.232 4702.776057.29210034.91
16689.31
    74.9    74.9    72.2   72.04   72.09   72.15    72.1   72.09    70.1    70.2
    70.2
       0       0       0       0   71.31   70.11   71.31       0       0       0
       0
 927.184 1254.483469.5224569.0694596.6074635.9194675.232 4702.776057.29210034.91
16689.31
    74.9    74.9    72.2   72.04   72.09   72.15    72.1   72.09    70.1    70.2
    70.2
       0       0       0       0   71.31   70.11   71.31       0       0       0
       0
Pier Skew, UpSta & Num, DnSta & Num=  ,4609.402, 2 ,4609.402, 2 , 0 , 0 , 0 ,,
    1.15    1.15
       0    71.5
    1.15    1.15
       0    71.5
Pier Skew, UpSta & Num, DnSta & Num=  ,4622.846, 2 ,4622.846, 2 , 0 , 0 , 0 ,,
    1.15    1.15
       0    71.5
    1.15    1.15
       0    71.5
Pier Skew, UpSta & Num, DnSta & Num=  ,4635.919, 2 ,4635.919, 2 , 0 , 0 , 0 ,,
    1.15    1.15
       0    71.5
    1.15    1.15
       0    71.5
Pier Skew, UpSta & Num, DnSta & Num=  ,4648.993, 2 ,4648.993, 2 , 0 , 0 , 0 ,,
    1.15    1.15
       0    71.5
    1.15    1.15
       0    71.5
Pier Skew, UpSta & Num, DnSta & Num=  ,4662.159, 2 ,4662.159, 2 , 0 , 0 , 0 ,,
    1.15    1.15
       0    71.5
    1.15    1.15
       0    71.5
BR Coef=-1 , 1 , 1 ,.9, 0 ,,,.8,0,1.2,0,
WSPro=,,,, 1 ,,,, 0 ,,,, 0 ,,,,-1 ,-1 ,-1 , 0 , 0 , 0 , 0 , 0
BR D #Sta/Elev= 30
 985.634   69.853302.388   70.424098.913   67.784596.978    67.44623.866    58.6
4624.793    55.94635.919    55.1  4648.9    55.94674.861    66.94862.783   63.67
5113.567   68.066514.505   66.126533.753   63.846606.797   66.317970.091   67.02
9562.493    66.79610.725   63.199629.397   65.999683.174   66.1911915.61   65.22
11948.23   61.6412020.44   64.8113281.95   64.56 13670.9   67.9915262.17   67.04
15675.84   69.6215996.22   67.9616055.67   65.3716162.15   72.0516226.92   68.02
BR D #Mann= 5
 985.634    .0684098.913    .1184596.978    .0444674.861    .1185113.567    .068
BC Design=,, 0 ,, 0 ,,,,,,
BC HTab HWMax=71.91

Type RM Length L Ch R = 1 ,207759.7,217.08,216.22,222.91
XS GIS Cut Line= 6
     3220421.829    13946793.603     3218412.556    13945907.895
     3216865.005    13945225.719     3216765.428    13945181.384
     3208241.758    13941153.549     3205515.996    13939865.498
#Sta/Elev= 30
 985.634   69.854098.913   67.784596.978    67.44623.866    58.64624.793    55.9
4635.919    55.1  4648.9    55.94674.861    66.94862.783   63.675113.567   68.06
5391.593   73.665822.288   70.795885.726   73.21 6051.08   69.726172.486   73.25
6437.586   73.416533.753   63.846878.796   66.719562.493    66.79610.725   63.19
9683.174   66.1911915.61   65.2211948.23   61.6412020.44   64.8113281.95   64.56
 13670.9   67.9915675.84   69.6216055.67   65.3716162.15   72.0516226.92   68.02
#Mann= 5 ,-1 , 0
 985.634    .068       04098.913    .118       04596.978     .04       0
4674.861    .118       05113.567    .068       0
#XS Ineff= 3 ,-1
 5543.3316226.92    71.4 985.634 4589.56      71 4683.11 5543.33   69.88
Permanent Ineff=
       F       F       F
#Block Obstruct= 3 ,-1
  985.28  986.14    73.5 15955.516103.04   67.6516159.9416226.92   71.91
Bank Sta=4596.978,4674.861
XS Rating Curve= 0
Skew Angle= 22
Exp/Cntr=.5,.3

Type RM Length L Ch R = 1 ,207543.4,479.37,329.4,247.31
XS GIS Cut Line= 6
     3220391.317    13946561.584     3218493.228    13945724.887
     3216946.015    13945042.859     3216848.837    13944999.593
     3208327.208    13940972.722     3205461.591    13939618.584
#Sta/Elev= 30
 1097.51   69.93    4954    66.8    4983    58.6    4984    55.9    4996    55.1
    5010    55.9    5038    66.9  5070.5    70.5  5253.8   63.13 5319.53   74.01
 5366.68   70.63 6842.56   70.89 6935.24   63.64 6977.78   69.36 7226.55   64.66
 7298.34   72.21 7327.05   68.52 7545.39   64.9310086.75   64.6210209.22   68.63
10299.35    64.812694.91    65.512748.72   61.0312833.37    64.613117.83    63.5
16494.49   68.3117334.62   67.2617380.15    64.617482.45   70.05 17563.7    67.1
#Mann= 7 ,-1 , 0
 1097.51    .068       0 4226.09    .118       0    4954     .04       0
    5038    .118       0 5378.72    .068       012788.51    .118       0
13117.83    .068       0
#XS Ineff= 2 ,-1
 1097.51  4173.3   71.66 6829.04 17563.7   70.73
Permanent Ineff=
       F       F
#Block Obstruct= 2 , 0
         1097.75   72.4517494.14           72.38
Bank Sta=4954,5038
XS Rating Curve= 0
Exp/Cntr=.3,.1

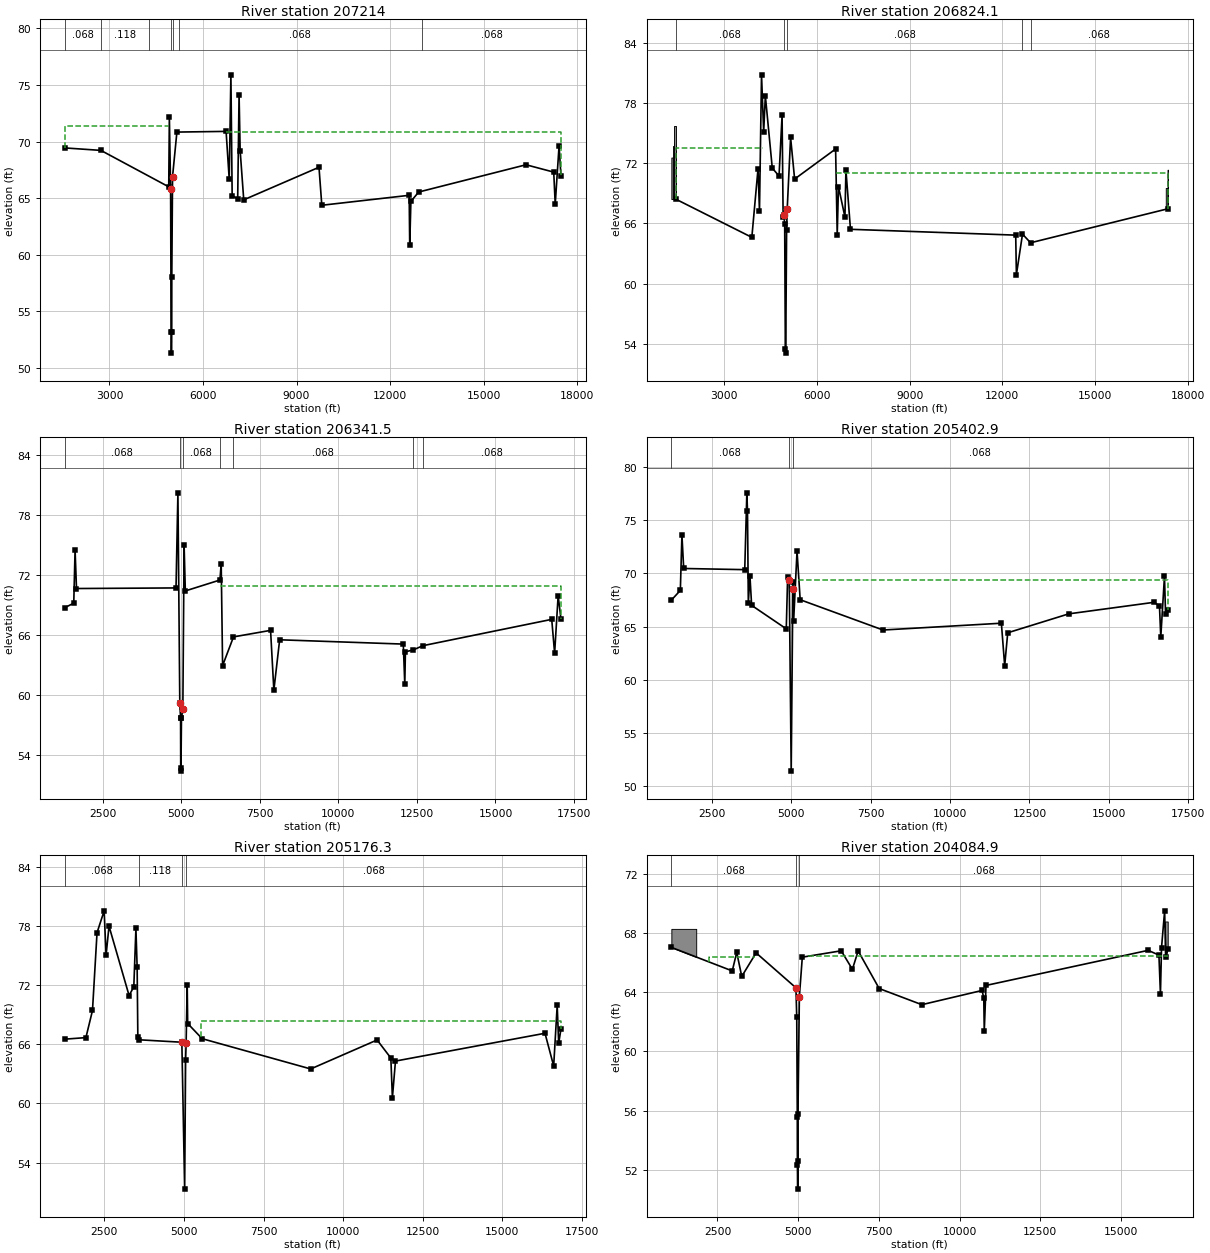
Type RM Length L Ch R = 1 ,207214  ,377.45,389.98,342.37
XS GIS Cut Line= 6
     3220221.615    13945105.512     3217073.316     13944614.67
     3216860.406    13944655.076     3216799.348    13944665.842
     3216703.524    13944682.378     3205451.186    13939571.364
#Sta/Elev= 30
 1561.06   69.44 2725.28   69.22    4901      66    4921    72.2    4961    65.8
    4978    53.2    4986    51.3    4997    53.2    4999      58    5023    66.9
  5162.5   70.84 6740.98    70.9 6841.12   66.67 6894.82    75.9  6935.1   65.23
 7112.56   64.92 7156.94   74.16 7191.48   69.21 7306.76   64.85 9720.26   67.73
 9810.62   64.3712613.16   65.2512630.46   60.8312668.34   64.7112917.08   65.54
16361.36   67.9517249.56    67.317297.36   64.4617421.08   69.6417482.06   66.92
#Mann= 7 ,-1 , 0
 1561.06    .068       0 2725.28    .118       0 4267.64    .118       0
    4961     .04       0    5023    .118       0  5222.9    .068       0
13024.18    .068       0
#XS Ineff= 2 , 0
         4920.34   71.38 6739.28           70.81
Permanent Ineff=
       F       F
#Block Obstruct= 2 , 0
         1561.55   71.8217421.74           71.22
Bank Sta=4961,5023
XS Rating Curve= 0
Exp/Cntr=.3,.1

Type RM Length L Ch R = 1 ,206824.1,399.69,482.59,506.21
XS GIS Cut Line= 6
      3220308.42    13944636.762     3216937.899    13944218.836
     3216812.832    13944266.301      3216754.95     13944288.52
     3216614.983    13944338.628     3205440.542    13939523.053
#Sta/Elev= 30
 1436.46   68.43 3900.88   64.62 4101.52   71.46    4148   67.22    4214   80.79
 4283.84   75.11 4337.62   78.71 4561.64   71.51 4780.08   70.72 4878.66   76.76
    4913    66.6    4938    66.8    4963    65.9    4984    53.5    4996    53.1
    5025    65.4    5044    67.4 5153.86   74.56 5283.94   70.42 6608.78   73.41
 6661.14   64.88 6701.36   69.67 6910.46   66.65 6942.32   71.31 7089.66   65.42
12430.96   64.8412453.46   60.91 12650.6   64.9412912.04   64.0817345.12   67.46
#Mann= 5 ,-1 , 0
 1436.46    .068       0    4938     .04       0    5044    .068       0
 12650.6    .118       012912.04    .068       0
#XS Ineff= 2 , 0
         4257.61   73.48 6606.72           71.07
Permanent Ineff=
       F       F
#Block Obstruct= 7 ,-1
 1299.39 1446.93   72.56 1348.95 1433.26   73.66 1370.02  1391.1   74.02
 1370.02 1433.26   75.7317281.8717345.12   69.5317345.0817345.23   71.36
17345.1417345.38   71.03
Bank Sta=4938,5044
XS Rating Curve= 0
Exp/Cntr=.3,.1

Type RM Length L Ch R = 1 ,206341.5,968.06,938.56,977.57
XS GIS Cut Line= 6
     3220343.143    13944185.374     3216870.191    13943817.795
      3216554.26     13943817.36     3216448.316    13943823.003
     3208295.457    13940644.723     3205401.009    13939447.055
#Sta/Elev= 30
 1287.64   68.72  1578.9   69.18 1620.66   74.51  1665.9   70.64  4833.5    70.7
  4893.5    80.2  4953.5    59.2  4978.5    57.7  4982.5    52.7  4990.5    52.4
  5006.5    57.7  5050.5    58.6  5090.5      75  5129.5    70.4 6230.58   71.49
 6271.38   73.13 6315.78   62.94 6662.48   65.81 7842.54   66.46 7946.98   60.48
 8131.64   65.5212066.92   65.09 12113.8   61.0612134.02   64.3212386.08   64.51
12689.56   64.9316790.42   67.56 16882.7   64.1716994.68   69.9317084.92   67.58
#Mann= 7 ,-1 , 0
 1287.64    .068       0  4953.5     .04       0  5050.5    .068       0
 6230.58    .118       0 6662.48    .068       012386.08    .118       0
12689.56    .068       0
#XS Ineff= 2 , 0
                         6238.88           70.87
Permanent Ineff=
       F       F
#Block Obstruct= 2 , 0
         1628.05   71.5116990.15           69.53
Bank Sta=4953.5,5050.5
XS Rating Curve= 0
Exp/Cntr=.3,.1

Type RM Length L Ch R = 1 ,205402.9,229.81,226.6,211.99
XS GIS Cut Line= 6
     3220383.655    13943183.925     3217021.025    13942871.667
     3216678.949    13942882.318     3216565.358    13942892.256
     3208294.667    13940455.339     3205348.725    13939275.263
#Sta/Elev= 30
 1225.57   67.49 1508.46   68.41 1558.32   73.63 1613.91   70.47 3536.14   70.36
 3602.43   77.59  3622.7    75.9 3649.01   67.23 3699.39   69.78 3753.08      67
 4843.66   64.79 4887.01    69.7 4936.99    69.4    4999    51.4 5051.01    68.5
 5069.02    69.2 5075.02    65.5 5182.72   72.11 5281.56   67.53 7891.13   64.68
11616.87   65.3211720.77   61.3211816.91   64.4213737.47    66.216432.27   67.29
   16595   66.9316635.88   64.0116751.95   69.72 16786.4    66.216854.67   66.53
#Mann= 3 , 0 , 0
 1225.57    .068       0 4936.99     .04       0 5051.01    .068       0
#XS Ineff= 2 , 0
                         5206.09           69.43
Permanent Ineff=
       F       F
#Block Obstruct= 2 , 0
         1554.88   71.8816752.65           69.59
Bank Sta=4936.99,5051.01
XS Rating Curve= 0
Exp/Cntr=.3,.1

Type RM Length L Ch R = 1 ,205176.3,1000.59,1091.44,1075.61
XS GIS Cut Line= 5
     3220352.749    13942506.702     3216674.084    13942660.438
     3216540.594    13942672.117     3208282.594    13940356.242
     3205318.848    13939163.226
#Sta/Elev= 30
 1251.25   66.51 1920.15   66.67 2126.62   69.42 2269.35   77.31 2493.11   79.53
 2553.16   75.01 2645.42   77.98 3275.67   70.94 3424.26   71.82  3490.6   77.74
 3529.01   73.79 3550.91   66.72 3582.12   66.45    4933    66.2    5021    51.3
    5051    64.4    5067    66.1    5101      72    5116    68.1 5570.43   66.56
 8979.22   63.4911063.95   66.4311495.92    64.611544.59   60.5711641.13   64.29
16336.79   67.1116609.22   63.7916719.72   69.9316766.53   66.0816838.57   67.55
#Mann= 4 ,-1 , 0
 1251.25    .068       0 3589.35    .118       0    4933     .04       0
    5067    .068       0
#XS Ineff= 2 , 0
                         5534.29           68.31
Permanent Ineff=
       F       F
#Block Obstruct= 2 , 0
         2304.88   69.9516723.26           69.04
Bank Sta=4933,5067
XS Rating Curve= 0
Exp/Cntr=.3,.1

Type RM Length L Ch R = 1 ,204084.9,892.1,1123.6,1153.04
XS GIS Cut Line= 6
     3220300.665    13941946.806     3216484.398    13941626.189
     3216431.178    13941605.248     3216308.173    13941559.743
     3208337.303    13940196.152     3205288.971    13938998.904
#Sta/Elev= 30
 1070.48   67.03 2957.18   65.44 3095.74   66.69 3251.74   65.07 3695.96   66.66
  4930.5    64.3  4955.5    62.3  4972.5    55.6  4975.5    52.3  4985.5    50.7
  4992.5    52.6  4993.5    55.8  5036.5    63.7 5127.91   66.37 6333.56    66.8
 6679.85   65.55 6857.61   66.79 7509.91   64.25 8831.93   63.1610697.62   64.12
10750.93   63.6110765.47   61.3610819.77   64.4615843.75   66.8316177.44   66.51
16224.44   63.8816258.01   67.0116354.71    69.5   16385   66.3516450.22   66.95
#Mann= 3 , 0 , 0
 1070.48    .068       0  4930.5     .03       0  5036.5    .068       0
#XS Ineff= 2 ,-1
  5290.416450.22   66.45 2222.49 3652.81    66.4
Permanent Ineff=
       F       F
#Block Obstruct= 2 ,-1
 1070.48 1840.48   68.2816350.1916450.22   68.78
Bank Sta=4930.5,5036.5
XS Rating Curve= 0
Exp/Cntr=.3,.1

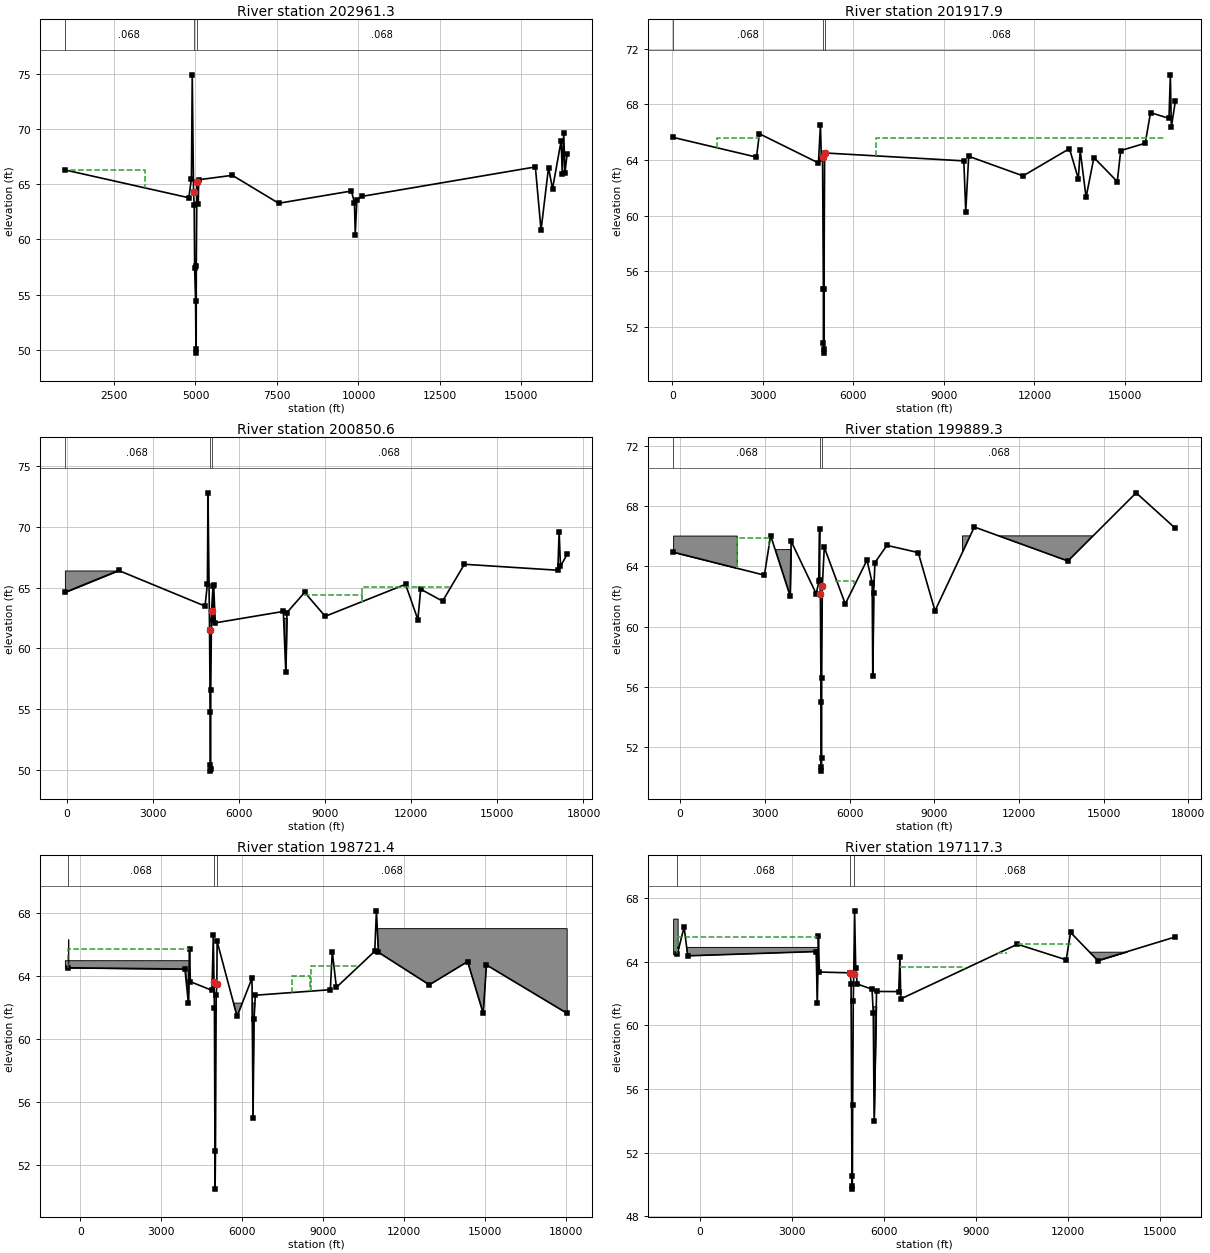
Type RM Length L Ch R = 1 ,202961.3,1378.94,1043.36,701.23
XS GIS Cut Line= 6
     3220196.499    13941504.098     3217886.816    13941332.344
     3216558.041    13940603.939      3216286.06    13940413.553
       3208304.7    13938828.812     3205199.341    13938677.729
#Sta/Elev= 30
   993.5   66.29 4795.34   63.77  4875.5    65.5  4900.5    74.9  4940.5    64.3
  4959.5    63.1  4974.5    57.4  5002.5    54.4  5014.5    49.7  5021.5    50.1
  5024.5    57.6  5044.5    65.2  5084.5    63.2  5096.5    65.4 6132.05    65.8
 7552.35   63.27 9783.51   64.38 9876.04   63.33 9901.55   60.41 9950.68   63.59
10100.31   63.8915427.07   66.5615601.41   60.8315830.54    66.515954.06   64.58
16219.22   68.9516252.89    65.9 16297.5   69.6416333.79   66.0116403.12   67.76
#Mann= 3 , 0 , 0
   993.5    .068       0  4940.5     .03       0  5044.5    .068       0
#XS Ineff= 2 ,-1
 1191.71 3450.09    66.3  6132.516403.12   65.77
Permanent Ineff=
       F       F
#Block Obstruct= 2 , 0
                        16216.95           68.87
Bank Sta=4940.5,5044.5
XS Rating Curve= 0
Exp/Cntr=.3,.1

Type RM Length L Ch R = 1 ,201917.9,841.96,1067.3,1236.93
XS GIS Cut Line= 6
     3221486.435    13939466.663     3218218.951    13939288.436
     3216568.881    13939580.946     3215740.713    13939786.639
     3208364.148    13938669.362     3205020.081    13938147.417
#Sta/Elev= 30
   22.51   65.62 2784.86    64.2 2882.84   65.88 4839.18   63.78 4905.36   66.52
  4935.5    64.1  4975.5    64.2  5002.5    54.7  5002.6    50.8  5012.5    50.1
  5022.5    50.4  5022.6    54.7  5044.5    64.5  9657.5   63.93 9721.18   60.28
 9818.66   64.26 11620.4   62.8513158.08   64.8113453.38   62.6413514.86   64.68
 13709.4   61.3113969.56   64.1714742.86   62.4414857.62   64.67 15669.9    65.2
15845.58    67.416457.42   66.9916502.74   70.1216535.44   66.3616669.64   68.24
#Mann= 3 ,-1 , 0
   22.51    .068       0  4975.5     .03       0  5044.5    .068       0
#XS Ineff= 2 ,-1
 1477.99 2885.65   65.59  6754.316281.24   65.57
Permanent Ineff=
       F       F
#Block Obstruct= 2 , 0
          737.21   66.19
Bank Sta=4975.5,5044.5
XS Rating Curve= 0
Exp/Cntr=.3,.1

Type RM Length L Ch R = 1 ,200850.6,1020.85,961.3,942.38
XS GIS Cut Line= 6
     3221549.265    13939351.475     3220596.953    13939223.149
     3217724.749    13938836.114     3216572.014     13938542.64
       3216504.4    13938524.522      3204476.38     13935548.41
#Sta/Elev= 30
  -77.71   64.61 1797.26   66.41 4807.43   63.48    4890    65.3    4910    72.8
    4965    61.5    4985    54.8  4987.6    50.4    4995    49.9    5004    50.1
    5007    56.6    5035    63.1    5086    65.1    5096    62.3    5108    65.2
    5164    62.1 7536.62   63.04 7623.33   58.02 7662.14   62.94 8279.28   64.61
 8996.92   62.6411797.45   65.2712227.51   62.3712324.82   64.8713087.98   63.89
13848.29   66.9217105.59   66.4317151.95   69.61 17198.3   66.7517431.62   67.75
#Mann= 3 ,-1 , 0
  -77.71    .068       0    4965     .03       0    5035    .068       0
#XS Ineff= 2 ,-1
 10278.313399.73   65.02 8264.7710269.44   64.37
Permanent Ineff=
       F       F
#Block Obstruct= 2 ,-1
  -77.71 1788.91   66.41 7412.18 7851.29   62.51
Bank Sta=4965,5035
XS Rating Curve= 0
Exp/Cntr=.3,.1

Type RM Length L Ch R = 1 ,199889.3,1118.32,1167.95,1249.05
XS GIS Cut Line= 6
     3221977.055    13938567.194     3218075.599    13937747.889
     3216847.129    13937623.335     3216778.171    13937625.743
     3216574.343    13937627.747     3205723.648    13931829.135
#Sta/Elev= 30
 -250.14   64.95 2983.98   63.42 3205.06   66.05    3896   62.03 3931.84   65.67
 4818.08   62.19  4915.5      63  4940.5    66.5  4943.5    63.1  4967.5    62.2
  4991.5      55  4993.5    50.7  5002.5    50.4  5012.5    51.3  5014.5    56.6
  5036.5    62.7 5106.38   65.27 5850.16   61.51  6619.9   64.42 6802.44   62.91
  6823.9   56.73 6854.46   62.25  6902.2   64.26 7325.34    65.4 8434.76   64.92
 9028.76   61.0510423.18   66.6213738.54   64.36 16157.4   68.8917546.92   66.53
#Mann= 3 , 0 , 0
 -250.14    .068       0  4967.5     .03       0  5036.5    .068       0
#XS Ineff= 4 ,-1
 2005.99 3149.27   65.86 5489.51 6159.67   63.02 6607.23 6945.88   64.18
 7311.8410098.77   65.25
Permanent Ineff=
       F       F       F       F
#Block Obstruct= 4 ,-1
 -250.14 2003.72   66.05 3212.55 3938.63   65.15 6624.33 6975.63      62
10004.9217546.92   66.03
Bank Sta=4967.5,5036.5
XS Rating Curve= 0
Exp/Cntr=.3,.1

Type RM Length L Ch R = 1 ,198721.4,858.08,1604.04,2060.96
XS GIS Cut Line= 6
     3222186.355    13938183.477     3217198.316    13936484.461
      3217090.44     13936484.55      3216949.44     13936484.55
     3216849.358    13936484.461     3206860.853     13928345.33
#Sta/Elev= 30
 -449.17   64.53 3876.07   64.45 4002.98   62.32 4047.66   65.74 4077.47   63.65
  4879.5    63.1  4929.5    66.6  4954.5    63.6  4970.5      62  4995.5    50.5
  5009.5    52.9  5035.5    62.8  5060.5    63.5  5070.5    66.2 5810.84   61.45
 6364.33   63.87 6402.27   55.02  6441.7   61.31 6487.23   62.79 9270.21   63.14
 9341.45   65.56 9494.33   63.2910918.12   65.5810979.39   68.1411054.09   65.51
12941.93   63.4514361.41   64.9214940.55   61.64 15059.9   64.7118053.95   61.64
#Mann= 3 , 0 , 0
 -449.17    .068       0  4954.5     .03       0  5060.5    .068       0
#XS Ineff= 3 ,-1
 -449.17 4047.56   65.72    7853 8501.61      64 8543.4510250.76   64.63
Permanent Ineff=
       F       F       F
#Block Obstruct= 4 ,-1
 -575.12 4047.36   65.01 -455.81 -448.82   66.34 5426.42 6714.47   62.29
10941.9618053.95   67.01
Bank Sta=4954.5,5060.5
XS Rating Curve= 0
Exp/Cntr=.3,.1

Type RM Length L Ch R = 1 ,197117.3,36.67,30.48,39.05
XS GIS Cut Line= 6
     3222212.207    13938136.081     3217813.366    13936328.143
     3217886.239    13935474.441     3217734.233    13935220.954
     3217786.372    13934520.877     3211459.413    13927260.662
#Sta/Elev= 30
  -724.8   64.47 -503.86   66.19 -385.49   64.37 3803.27   64.64 3839.87   61.41
 3875.82   65.64 3906.46   63.35  4915.5    63.3  4940.5    62.6  4970.5    49.9
  4977.5    49.7  4984.5    50.5  4992.5      55  5012.5    61.5  5027.5    63.2
  5055.5    67.2  5091.5    63.6  5141.5    62.6 5624.06   62.27 5665.24   60.75
 5692.14   54.01  5771.2   62.13  6494.1   62.12 6533.89   64.28 6560.94   61.66
10364.07    65.111954.38   64.1212098.48   65.8412986.49   64.0715515.76   65.56
#Mann= 3 ,-1 , 0
  -724.8    .068       0  4915.5     .03       0  5027.5    .068       0
#XS Ineff= 5 ,-1
  -724.8 3875.45   65.58 6528.86  8613.3   63.68 9718.2410014.61   64.56
10364.2512152.64    65.112213.8715510.81   65.31
Permanent Ineff=
       F       F       F       F       F
#Block Obstruct= 4 ,-1
 -861.83 -714.29   66.71 -726.65 3874.31    64.9 5524.68 5861.83    61.2
12241.6315515.76   64.63
Bank Sta=4915.5,5027.5
XS Rating Curve= 0
Exp/Cntr=.5,.3

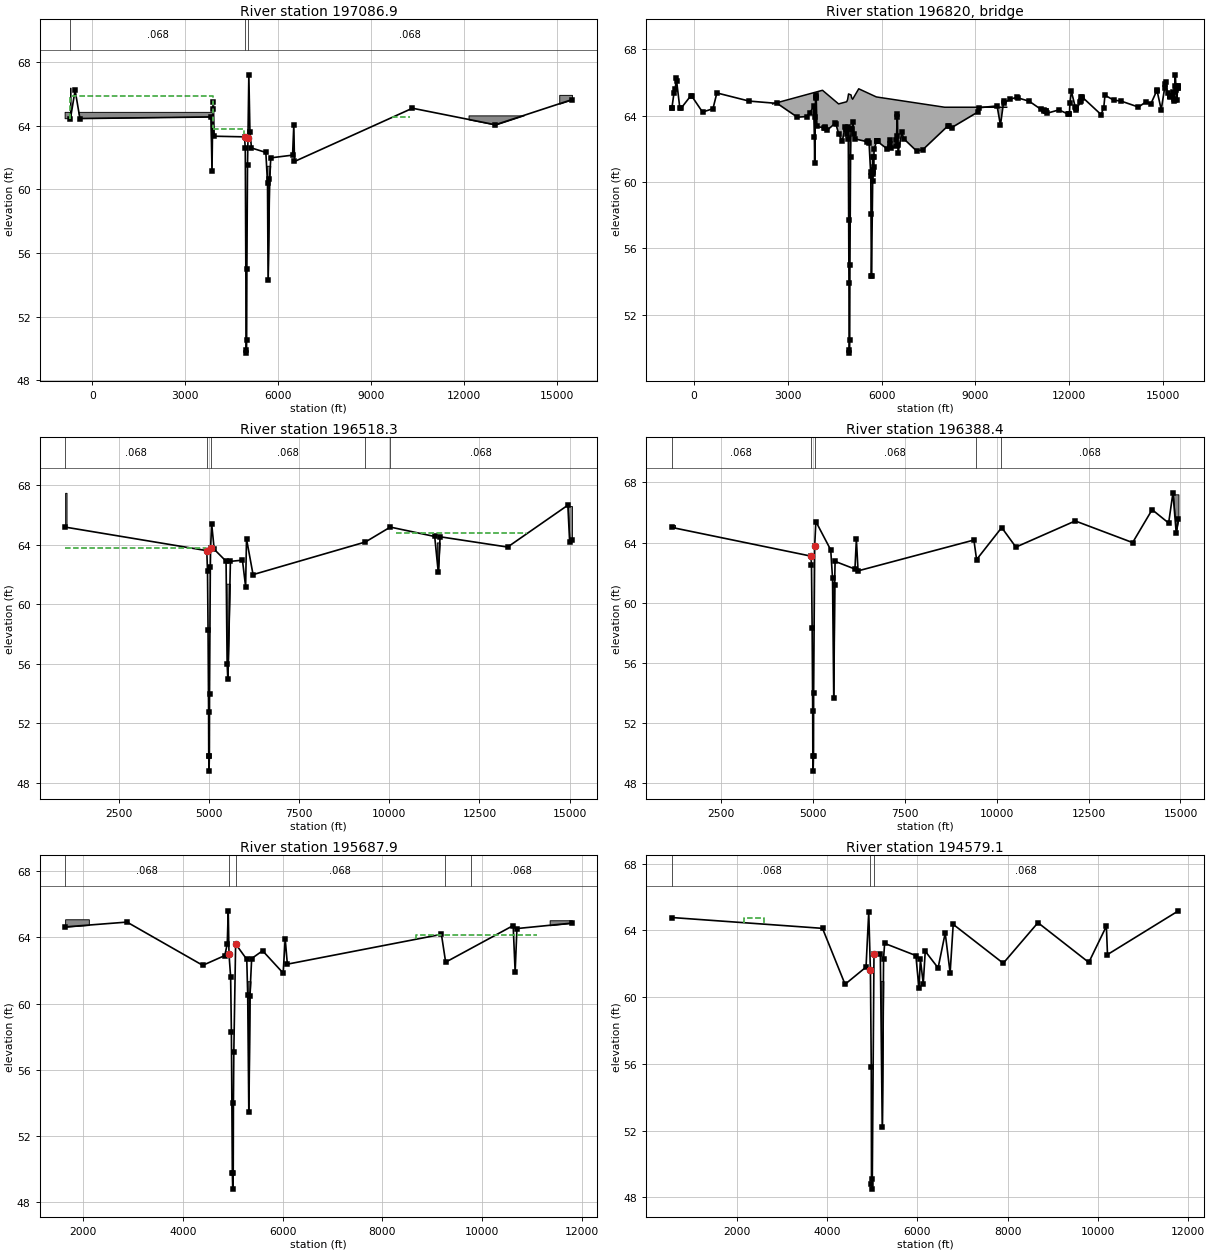
Type RM Length L Ch R = 1 ,197086.9,543.09,568.52,580.95
XS GIS Cut Line= 6
     3222226.659    13938109.586      3217845.13    13936308.763
     3217916.927    13935467.659     3217764.888    13935213.268
      3217817.22    13934510.612     3211497.021    13927258.155
#Sta/Elev= 30
 -711.31   64.44 -560.07   66.23 -404.48   64.45 3829.77   64.55  3862.5   61.17
 3888.71   65.063904.929   65.513933.439   63.34  4912.5    63.3  4937.5    62.6
  4967.5    49.9  4974.5    49.7  4981.5    50.5  4989.5      55  5009.5    61.5
  5024.5    63.2  5052.5    67.25088.499    63.6  5138.5    62.65602.029   62.32
5656.119   60.39 5674.03   54.32 5719.15   60.63 5763.05   61.98 6465.98   62.15
6505.778   64.07 6527.62   61.7510337.96    65.113016.39   64.0615490.98   65.64
#Mann= 3 ,-1 , 0
 -711.31    .068       0  4912.5     .03       0  5024.5    .068       0
#XS Ineff= 5 ,-1
 -711.31 3880.56   65.89 3880.56  4910.2    63.85059.199 9687.62   63.78
 9687.6210245.43   64.5710339.3815080.75   65.09
Permanent Ineff=
       F       F       F       F       F
#Block Obstruct= 5 ,-1
 -882.44 3902.31   64.84  -716.8 -710.56    66.4 5503.53 5882.98   61.48
12150.5715033.35   64.6515081.1215490.98   65.94
Bank Sta=4912.5,5024.5
XS Rating Curve= 0
Exp/Cntr=.5,.3

Type RM Length L Ch R = 3 ,196820  ,,,
Node Photo=G:\C2001-041_Harris_County_FEMA\3-Cedar_Bayou\Cedar_Bayou\Survey _info\121s56_ramsey_old_atascocita\121S56P8.jpg
BEGIN DESCRIPTION:
Ramsey Road (Old Atascocita)
END DESCRIPTION:
Bridge Culvert--1,0,-1,-1, 0
Deck Dist Width WeirC Skew NumUp NumDn MinLoCord MaxHiCord MaxSubmerge Is_Ogee
243.75,37.2,2.6,0, 13, 13, , , .95, 0, 0,0,,
    2516    4112    4626    4886    4916 4944.28 5024.72    5045    5075  5270.5
  5833.1  8017.1   10000
    64.7   65.52    64.7   64.83   64.97    65.3   65.24   65.07   64.98   65.61
   65.12    64.5    64.5
       0       0       0       0       0    62.9    62.9       0       0       0
       0       0       0
    2526    4122    4636    4896    4926 4954.28 5034.72    5055    5085  5280.5
  5843.1  8027.1   10000
    64.7   65.52    64.7   64.83   64.97    65.3   65.24   65.07   64.98   65.61
   65.12    64.5    64.5
       0       0       0       0       0    62.9    62.9       0       0       0
       0       0       0
Pier Skew, UpSta & Num, DnSta & Num=  ,4966.998, 2 ,4977.001, 2 , 0 , 0 , 0 ,,
    1.71    1.71
       0      64
    1.71    1.71
       0      64
Pier Skew, UpSta & Num, DnSta & Num=  ,5001.998, 2 ,5012, 2 , 0 , 0 , 0 ,,
    1.71    1.71
       0      64
    1.71    1.71
       0      64
BR Coef=-1 , 1 , 1 ,.9, 0 ,,,.8,0,2,0,
WSPro=,,,, 1 ,,,, 0 ,,,, 0 ,,,,-1 ,-1 ,-1 , 0 , 0 , 0 , 0 , 0
BR U #Sta/Elev= 153
 -711.31   64.44 -703.51   64.44 -635.57   65.36 -595.49   65.62-560.071   66.23
 -551.29   66.07 -450.48   64.47 -404.48   64.45  -97.71   65.19 -75.409   65.19
  276.19   64.21   610.6   64.41 735.359   65.36 1765.18   64.87 2663.87   64.73
 3307.59    63.9 3605.54   63.943715.311   64.18 3829.77   64.55 3852.79   62.68
  3862.5   61.173880.142   63.92 3888.71   65.06 3896.33   65.22  3910.6    65.1
 3933.44   63.34 4161.97   63.26 4179.53   63.334190.992   63.24 4267.32   63.13
 4523.07   63.54 4535.34   63.52 4634.79   62.86 4745.14   62.44  4833.6   63.33
4864.081   63.174870.021   63.19  4887.5    62.9  4912.5    63.3  4937.5    62.6
  4949.5    57.74960.499    53.9  4967.5    49.9  4974.5    49.7  4981.5    50.5
  4989.5      55  5009.5    61.5  5024.5    63.25052.499    63.2  5088.5    63.6
  5113.5    62.9  5138.5    62.6  5524.8   62.43 5562.11   62.46 5602.03   62.32
5650.809    60.6 5656.12   60.39 5664.12   58.09 5674.03   54.32 5679.55   54.35
5715.128   60.03 5718.03   60.47 5719.15   60.63 5720.96   60.73 5734.12   61.51
 5743.95    60.9 5753.37   61.525763.048   61.98  5845.1   62.47 5854.25   62.47
5863.188   62.445871.048   62.44 6178.67   61.99 6255.61   62.526272.649   62.27
 6318.17   62.04 6465.98   62.156470.088   62.53 6479.62   62.78 6503.08   63.93
 6505.77   64.07 6522.32   62.23 6527.62   61.75 6649.78   62.986706.332   62.61
 7123.19   61.867316.809   61.948123.608   63.38  8159.5    63.4 8239.62   63.27
 9087.26   64.229128.689   64.479693.161   64.589801.359   63.429904.839   64.86
9922.371   64.7710115.45   64.9910337.96    65.110347.52   65.0710721.01   64.86
11097.97   64.3711187.38   64.3211200.37   64.2811248.83   64.2911250.48   64.28
11295.79   64.1411670.54   64.3411972.61   64.0811981.24   64.1212007.14   64.11
12021.64   64.7512070.37   65.4512194.53   64.4912206.82   64.4412209.64   64.45
12213.75   64.3212357.43   64.8112384.61   64.8712391.66   65.1412413.71   65.04
12422.77    65.113016.39   64.0613103.03   64.4613143.11   65.2213429.55   64.92
13642.13   64.8814213.22   64.5114467.55   64.8414604.41   64.6814794.96   65.49
14804.73   65.5214941.73   64.3515047.81   65.6315075.94   65.9215080.33      66
15142.45   65.3615232.94   65.1815234.96   65.1315236.54    65.215237.67   65.18
15318.47   65.41 15335.7   64.8915352.69   64.9915366.95   64.9415374.26   65.76
15393.08   66.4515414.71   65.5615441.65   64.9515466.84   65.63 15470.9   65.75
15471.71    65.815480.21   65.7415490.98   65.64
BR U #Mann= 3
 -711.31    .068  4937.5     .03  5138.5    .068
BR U Banks=4937.5,
BR D #Sta/Elev= 144
1017.991   65.18 1046.83   65.17 1051.34   65.18 1988.98   65.04 3260.44   64.16
 3423.04   63.99 4208.94   63.65 4608.74   62.92 4638.41   62.55 4686.98   62.74
 4719.37   62.81 4800.04   63.13 4842.36   64.06  4844.9      64    4871    64.6
4895.999    64.7    4916    64.6    4931    64.1    4944    63.6    4964    62.2
    4979    58.3    4994    52.8    4998    49.8    5006    48.8    5016    49.9
    5016    49.8    5020      545027.999    57.1  5042.3    62.5    5050    63.8
    5060    64.8 5133.71   63.855149.359   63.69 5270.83   63.275428.281   63.04
5449.758   62.83  5478.2   62.89 5485.08    62.15494.459   58.475507.622   56.02
 5510.71   55.57  5519.8   55.76 5526.96   54.965534.839   56.485546.679   56.75
5555.628   58.09 5564.92   59.595575.721   61.03 5579.97   61.145591.971   62.38
5598.721   62.885618.651    63.15630.168   62.94 5659.83   62.94 5715.24   62.72
 5732.91   62.685751.912   62.795900.279   62.97 5932.11   62.965976.182    62.7
5983.859   62.75 5993.89   61.99 6007.56   61.626020.049   61.18 6026.84   61.83
6044.681   64.39 6055.18   64.376067.508   63.99  6070.7   63.48 6081.74   63.74
6113.271   62.85 6123.85   62.85 6129.16   62.96 6226.31   61.99 6589.05   62.33
 7399.68   62.47 7987.97   63.03 8366.79   63.71 8601.39   63.84 9125.15   62.98
9135.371   62.99 9138.17   63.01 9139.51   62.98 9144.84   63.05 9340.12   64.18
 9369.27   63.55 9455.16   63.56 9582.19   64.4110030.15   65.1810194.51   65.17
10546.69   63.8710610.83   63.9310631.14   63.9210937.26   64.4511026.55   64.25
11125.82   64.1911230.85   64.3211260.34   64.5511274.48   64.1411314.55   64.11
11319.72   64.1911355.42   62.3211357.61   62.2611359.51   62.1411367.49   62.35
11392.23   63.68 11399.3   64.1111399.69   64.1311409.68   64.5311409.86   64.53
11454.65   64.1411471.97   64.0811494.85   64.34 11512.6   64.19 11584.9   64.52
 12030.8    64.312038.85   64.3612363.94   63.9712447.06   64.1412649.36   64.33
12898.14   64.0112959.53   64.2713246.93   64.5213281.58   63.8413606.55   64.87
13614.25   64.8413635.78   64.91 13735.1   65.1114193.13   64.7814282.84   65.49
14414.35   64.9214538.59   64.9914701.52   65.6514828.49   65.3914863.07   65.88
14885.16    66.414902.37   66.5714933.66   66.3314950.61   66.6514968.32    65.9
15000.57   64.1915009.25   64.4415015.13    64.215063.86   64.29
BR D #Mann= 5
1017.991    .068    4944     .03 5133.71    .068 9340.12    .11810030.15    .068
BR D Banks=4944,
BC Design=,, 0 ,, 0 ,,,,,,
BC HTab HWMax=67.2

Type RM Length L Ch R = 1 ,196518.3,105.86,129.93,113.56
XS GIS Cut Line= 6
     3221286.411    13937006.926     3218335.018    13935793.893
     3218388.892    13935162.769     3218236.073    13934896.507
     3218291.844    13934147.661     3212271.449     13927239.23
#Sta/Elev= 30
 1017.99   65.18    4944    63.6    4964    62.2    4979    58.3    4994    52.8
    4998    49.8    5006    48.85015.999    49.8    5020      545042.299    62.5
    5050    63.8  5079.1    65.45149.359   63.69  5478.2   62.895507.619   56.02
 5526.96   54.96 5598.72   62.88 5932.11   62.96 6020.05   61.186044.681   64.39
 6226.31   61.99 9340.12   64.1810030.16   65.1811260.34   64.5511359.51   62.14
11409.68   64.5313281.58   63.8414950.63   66.6515000.57   64.1915063.87   64.29
#Mann= 5 ,-1 , 0
 1017.99    .068       0    4944     .04       0    5050    .068       0
 9340.12    .118       010030.16    .068       0
#XS Ineff= 3 ,-1
 1017.99    4930    63.8  5125.3 10180.8   63.55 10180.813804.21   64.79
Permanent Ineff=
       F       F       F
#Block Obstruct= 4 ,-1
 1017.99 1056.91   67.48 5319.87 5657.11   61.3811320.2811402.33   64.15
14949.7615063.87   66.59
Bank Sta=4944,5050
XS Rating Curve= 0
Exp/Cntr=.5,.3

Type RM Length L Ch R = 1 ,196388.4,1124.43,700.48,321.62
XS GIS Cut Line= 6
     3221303.925    13936833.906     3218433.856    13935654.298
     3218483.428    13935073.569     3218330.273    13934806.462
     3218387.019    13934044.527      3212458.29    13927241.283
#Sta/Elev= 30
 1161.74   65.01  4950.8    63.1  4965.2    62.5    4983    58.3    4998    52.8
    5002    49.8    5010    48.8  5020.1    49.8    5024      54  5052.7    63.8
  5084.3    65.4 5488.86   63.51 5537.62   61.62 5570.12   53.69 5594.02   61.21
 5607.36   62.75 6146.76   62.24 6185.98   64.23 6231.66   62.12 9381.94   64.17
    9455   62.8710138.16      6510523.62    63.712137.34   65.4413698.02      64
14228.74   66.1914677.66    65.314794.62   67.3114883.06   64.6714943.64   65.57
#Mann= 5 ,-1 , 0
 1161.74    .068       0  4950.8     .04       0  5052.7    .068       0
 9430.88    .118       010119.98    .068       0
#XS Ineff= 1 ,-1
10138.0814333.68   64.74
Permanent Ineff=
       F
#Block Obstruct= 3 ,-1
 1161.74 1253.62   65.17    5396  5733.3    61.414794.7614943.64   67.21
Bank Sta=4950.8,5052.7
XS Rating Curve= 0
Exp/Cntr=.3,.1

Type RM Length L Ch R = 1 ,195687.9,1248.38,1108.8,840.89
XS GIS Cut Line= 6
     3221443.502    13936608.498     3218977.555    13934614.727
     3218915.697    13934479.997      3218871.86    13934390.117
     3218853.331    13934354.722     3214481.697    13929264.748
#Sta/Elev= 30
 1634.08   64.63 2875.63   64.92 4395.34   62.31    4837    62.9    4887    63.6
    4907    65.6    4922      63    4955    61.6    4970    58.3    4989    49.8
    4997    48.8    5007    49.8    5011      54    5019    57.1    5055    63.6
 5278.57   62.67 5297.29   60.53 5319.61   53.45 5340.89   60.48 5376.94   62.72
 5596.48   63.19 6009.05   61.84 6049.44   63.92 6092.83   62.38  9184.4   64.18
  9269.2    62.510624.05   64.71 10663.6    61.910699.42   64.5311803.03   64.86
#Mann= 5 ,-1 , 0
 1634.08    .068       0    4922     .04       0    5055    .068       0
 9260.79    .118       0 9769.24    .068       0
#XS Ineff= 3 ,-1
 5592.49 6045.71   63.06 6049.96 8682.17   63.86 8682.1711099.36   64.13
Permanent Ineff=
       F       F       F
#Block Obstruct= 3 ,-1
 1634.08 2109.76   65.09  5156.9 5452.03   61.3511356.3811803.03   65.03
Bank Sta=4922,5055
XS Rating Curve= 0
Exp/Cntr=.3,.1

Type RM Length L Ch R = 1 ,194579.1,766.68,1043.18,1073.04
XS GIS Cut Line= 6
     3223058.085    13936504.332     3219835.571    13933736.489
     3219683.336    13933744.234     3219604.529    13933749.745
     3219471.564      13933759.6     3214863.641    13929021.693
#Sta/Elev= 30
  561.74   64.77  3902.7   64.12 4402.07   60.77  4866.5    61.8  4926.5    65.1
  4963.5    61.6  4982.5    55.8  4987.5    48.8  4996.5    48.5  5005.5    49.1
  5042.5    62.6 5183.06   62.56 5225.49   52.21 5254.73   62.31 5278.53   63.22
 5970.36   62.49 6037.97   60.52 6070.77   62.26 6133.55    60.8 6177.68   62.75
 6462.24   61.75 6619.64   63.84 6728.56   61.45 6796.75   64.36 7904.88   62.03
 8673.47   64.46 9799.41   62.08 10188.3   64.2510213.12   62.5511783.65   65.17
#Mann= 3 ,-1 , 0
  561.74    .068       0  4963.5     .04       0  5042.5    .068       0
#XS Ineff= 4 ,-1
 2174.02  2603.1   64.77 5931.13 6570.28   62.44 6619.13 8573.21   63.73
 8654.89 11671.9   64.08
Permanent Ineff=
       F       F       F       F
#Block Obstruct= 1 ,-1
 5128.84 5297.49   60.96
Bank Sta=4963.5,5042.5
XS Rating Curve= 0
Exp/Cntr=.3,.1