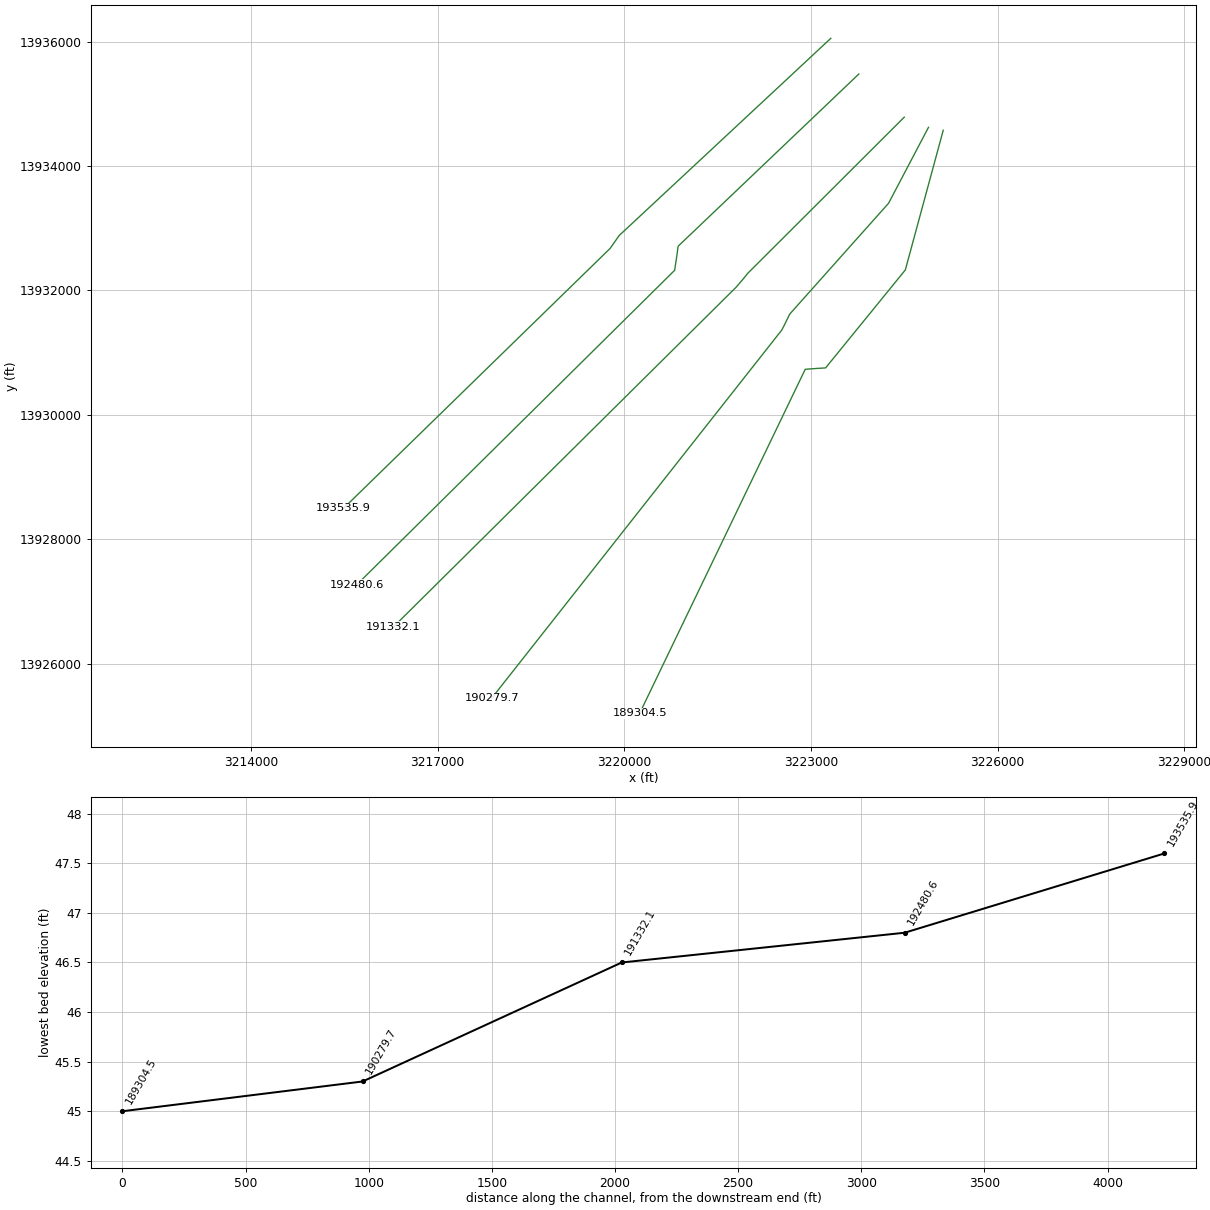
HEC-RAS study Q100-00-00.prj: Q100-00-00

--- Q100-00-00.g01 (geometry) --- (continued)

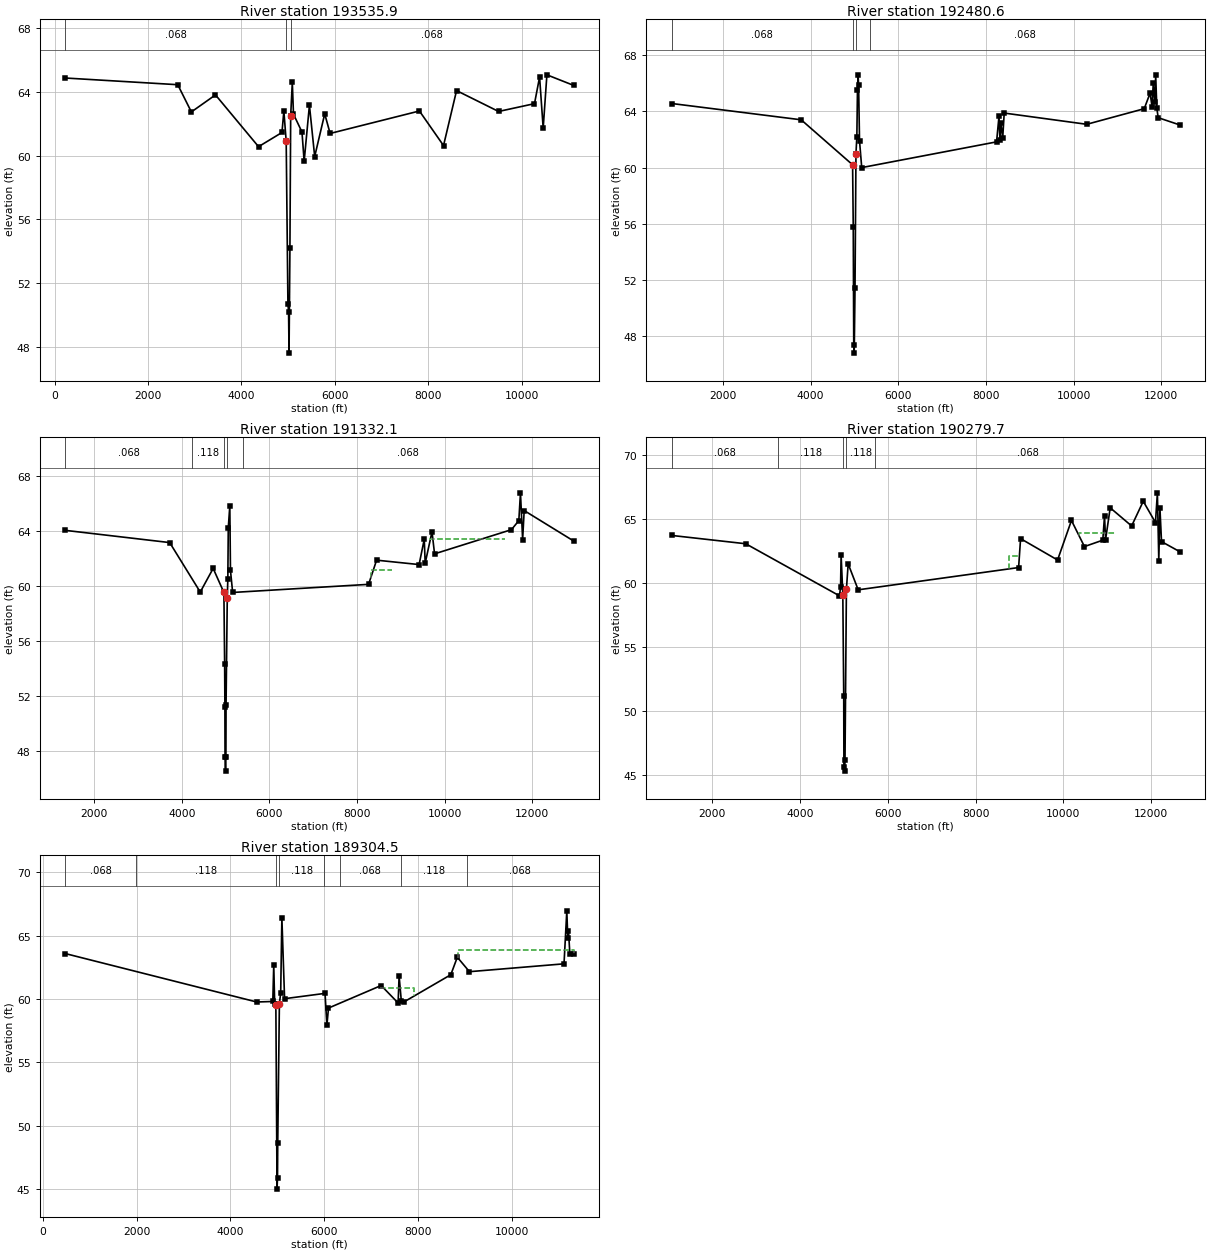
Type RM Length L Ch R = 1 ,193535.9,877.48,1055.3,1110
XS GIS Cut Line= 6
     3223318.502    13936052.943     3219916.063    13932882.551
     3219874.149      13932822.8     3219819.086    13932744.161
     3219770.144    13932674.896     3215488.641    13928500.859
#Sta/Elev= 30
  227.43   64.87  2637.4   64.45 2928.54   62.74 3444.93   63.81 4366.96   60.56
 4868.66   61.45    4909    62.8    4959    60.9    4996    50.7    5010    50.2
    5020    47.6    5039    54.2    5055    62.5    5090    64.6    5115    62.6
 5296.86   61.48 5343.45   59.64 5456.33   63.16 5569.08   59.94 5783.84   62.62
 5899.33   61.39 7811.54    62.8  8327.7   60.63 8606.63   64.08 9506.39   62.77
10275.26   63.2610384.36   64.9310461.38   61.7210540.97   65.0711111.28   64.41
#Mann= 3 ,-1 , 0
  227.43    .068       0    4959     .04       0    5055    .068       0
#XS Ineff= 3 ,-1
  2088.2  2631.7   64.29 8607.5610323.88   63.86 7394.52  8607.3   62.38
Permanent Ineff=
       F       F       F
#Block Obstruct= 2 , 0
         1090.91   64.7210333.52           64.41
Bank Sta=4959,5055
XS Rating Curve= 0
Exp/Cntr=.3,.1

Type RM Length L Ch R = 1 ,192480.6,1202.59,1148.55,1006.69
XS GIS Cut Line= 6
     3223769.891    13935480.026     3220864.541    13932711.376
     3220848.933    13932596.968     3220838.217    13932520.717
     3220808.418    13932324.128     3215696.974     13927268.22
#Sta/Elev= 30
  831.92   64.56 3785.89    63.4  4958.5    60.2  4973.5    55.8  4984.5    47.4
  4995.5    46.8  5013.5    51.4  5035.5      61  5055.5    62.2  5069.5    65.5
  5082.5    66.6  5095.5    65.9  5116.5    61.9  5166.5      60 8242.15   61.83
 8297.68   63.65 8318.77   61.99 8339.87    63.2 8382.07    62.1 8416.39   63.88
10298.76   63.08 11610.2   64.1911743.74    65.311789.67   64.3211815.89      66
11851.32   64.64 11871.4   66.5811897.54   64.22 11928.7   63.5512426.02   63.03
#Mann= 4 ,-1 , 0
  831.92    .068       0  4958.5     .04       0  5035.5    .118       0
 5353.62    .068       0
#XS Ineff= 2 ,-1
 8418.3411132.86   63.62 8293.45 8412.49   63.48
Permanent Ineff=
       F       F
#Block Obstruct= 2 , 0
         2019.07   64.7111817.66           65.78
Bank Sta=4958.5,5035.5
XS Rating Curve= 0
Exp/Cntr=.3,.1

Type RM Length L Ch R = 1 ,191332.1,940.98,1052.41,1074.8
XS GIS Cut Line= 6
     3224499.058    13934785.582     3221984.194    13932276.423
      3221940.82    13932222.059     3221891.325    13932163.073
     3221798.989    13932054.737     3216287.252    13926591.137
#Sta/Elev= 30
  1339.5   64.02 3724.09   63.13 4421.77   59.53 4716.34   61.25  4961.5    59.5
  4978.5    54.3  4984.5    51.2  4987.5    47.5  4998.5    46.5  5007.5    47.5
  5010.5    51.3  5038.5    59.1  5051.5    60.5  5061.5    64.2  5096.5    65.8
  5111.5    61.1  5161.5    59.5 8263.78   60.09 8446.51   61.85 9416.83   61.53
 9534.52   63.37 9555.64   61.63 9711.49   63.92 9769.58   62.3111525.04   64.07
11693.13   64.7311730.58   66.7511779.99   63.3511815.32   65.4612941.73   63.25
#Mann= 5 ,-1 , 0
  1339.5    .068       0 4240.06    .118       0  4961.5     .04       0
  5038.5    .118       0 5400.28    .068       0
#XS Ineff= 2 ,-1
  9668.211381.48   63.38 8308.87 8799.22   61.13
Permanent Ineff=
       F       F
#Block Obstruct= 2 , 0
                        11726.92           66.19
Bank Sta=4961.5,5038.5
XS Rating Curve= 0
Exp/Cntr=.3,.1

Type RM Length L Ch R = 1 ,190279.7,990.31,975.16,915.53
XS GIS Cut Line= 6
     3224888.786    13934622.524     3224247.135    13933402.006
      3222657.67    13931619.785     3222569.447    13931438.223
     3222528.587    13931361.619     3217867.113    13925445.304
#Sta/Elev= 30
 1071.77   63.72 2760.23   63.07    4897      59    4922    59.7    4934    62.2
    4973    59.1    4994    51.2  4998.1    45.6    5015    45.3    5023    46.2
    5055    59.5    5095    61.5 5323.56   59.47 8980.43   61.21 9025.25   63.47
 9868.65    61.810185.31   64.8910481.01   62.8510899.48   63.3510938.71   65.24
10962.95   63.3911068.18   65.8811556.69   64.4611821.63   66.3912100.05   64.73
12144.09   67.0512176.13   61.7512202.15   65.8512237.99   63.2412659.46   62.44
#Mann= 5 ,-1 , 0
 1071.77    .068       0 3505.19    .118       0    4973     .04       0
    5055    .118       0 5706.85    .068       0
#XS Ineff= 3 ,-1
10362.3411196.66   63.93  9025.110100.92   63.46 8770.66 9002.74   62.12
Permanent Ineff=
       F       F       F
#Block Obstruct= 2 , 0
                        12144.51           66.56
Bank Sta=4973,5055
XS Rating Curve= 0
Exp/Cntr=.3,.1

Type RM Length L Ch R = 1 ,189304.5,263.9,360.18,454.49
XS GIS Cut Line= 6
     3225125.819    13934575.118      3224516.33    13932329.624
     3223234.774    13930755.295       3223105.6    13930747.832
     3222907.417    13930733.042     3220245.585    13925202.248
#Sta/Elev= 30
  481.45   63.58 4558.59   59.76  4901.5    59.8  4921.5    62.7  4941.5    59.6
  4966.5    59.5  4991.5      45  5001.5    45.9  5006.5    48.6  5041.5    59.6
  5069.5    60.5  5094.5    66.4 5152.19   60.02 6013.86   60.44 6052.94   57.91
 6086.74   59.28 7208.82   61.06 7569.72   59.68 7590.31   61.82 7637.11   59.86
 7691.49   59.76 8691.19   61.91 8829.82   63.29 9088.02   62.15 11101.7   62.77
11161.09   66.9511181.94   64.8111196.81   65.3611226.46   63.5311304.32   63.55
#Mann= 8 ,-1 , 0
  481.45    .068       0 1996.65    .118       0  4966.5     .04       0
  5041.5    .118       0 6001.12    .118       0  6325.8    .068       0
 7624.55    .118       0 9031.52    .068       0
#XS Ineff= 2 ,-1
 8846.4211304.32   63.86 7194.28 7909.42   60.87
Permanent Ineff=
       F       F
#Block Obstruct= 2 , 0
                        11159.13            65.9
Bank Sta=4966.5,5041.5
XS Rating Curve= 0
Exp/Cntr=.3,.1