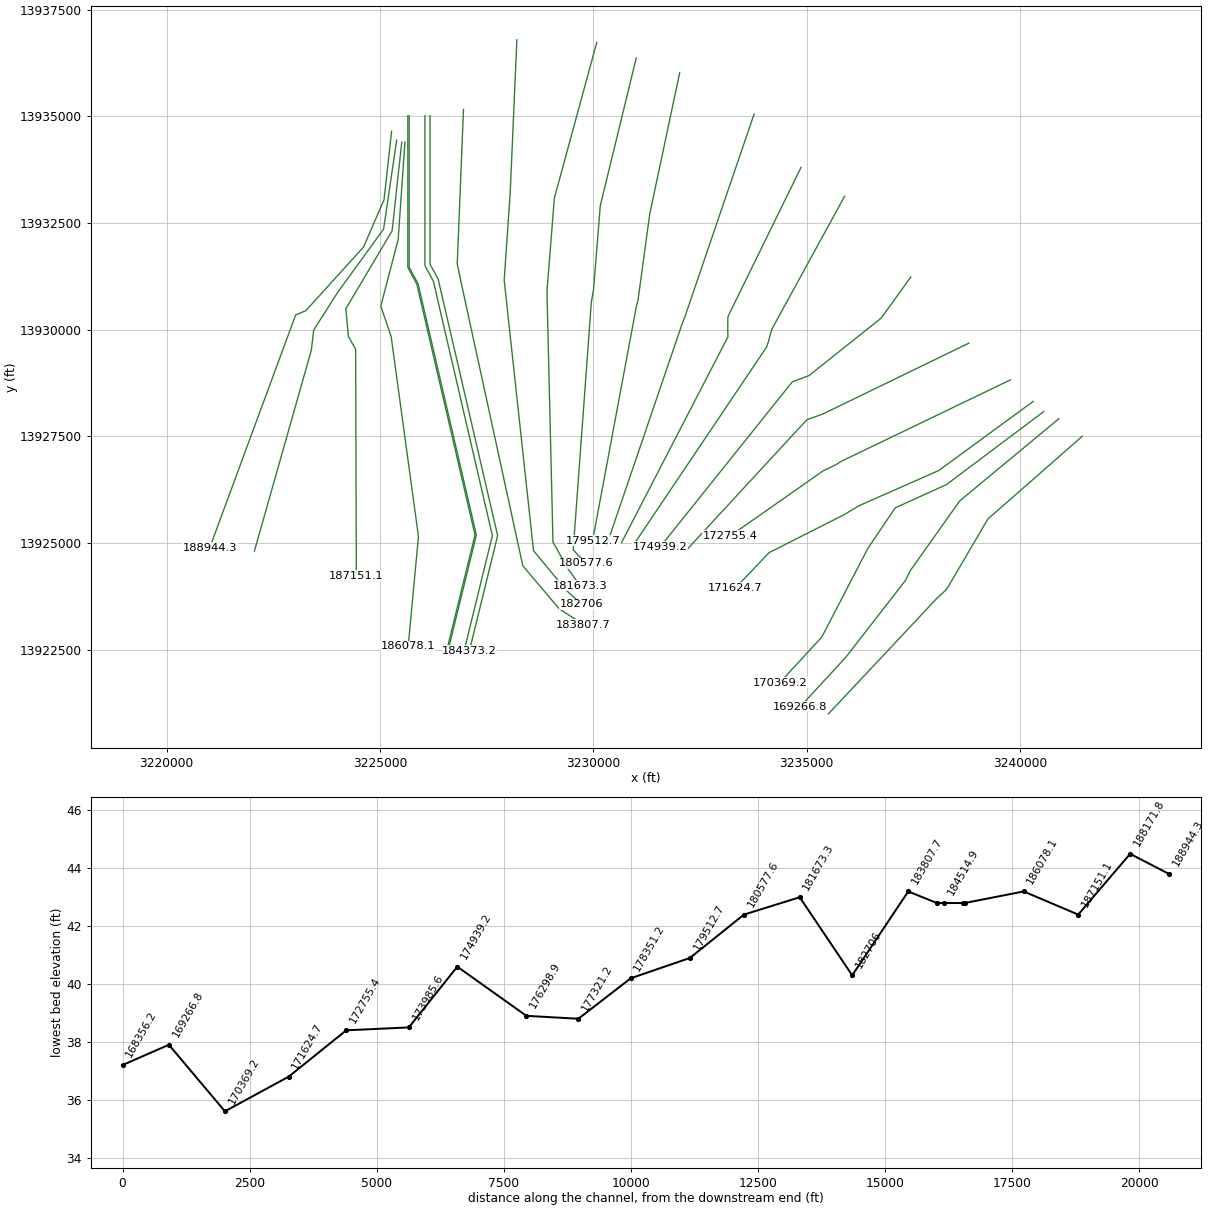
HEC-RAS study Q100-00-00.prj: Q100-00-00

--- Q100-00-00.g01 (geometry) --- (continued)

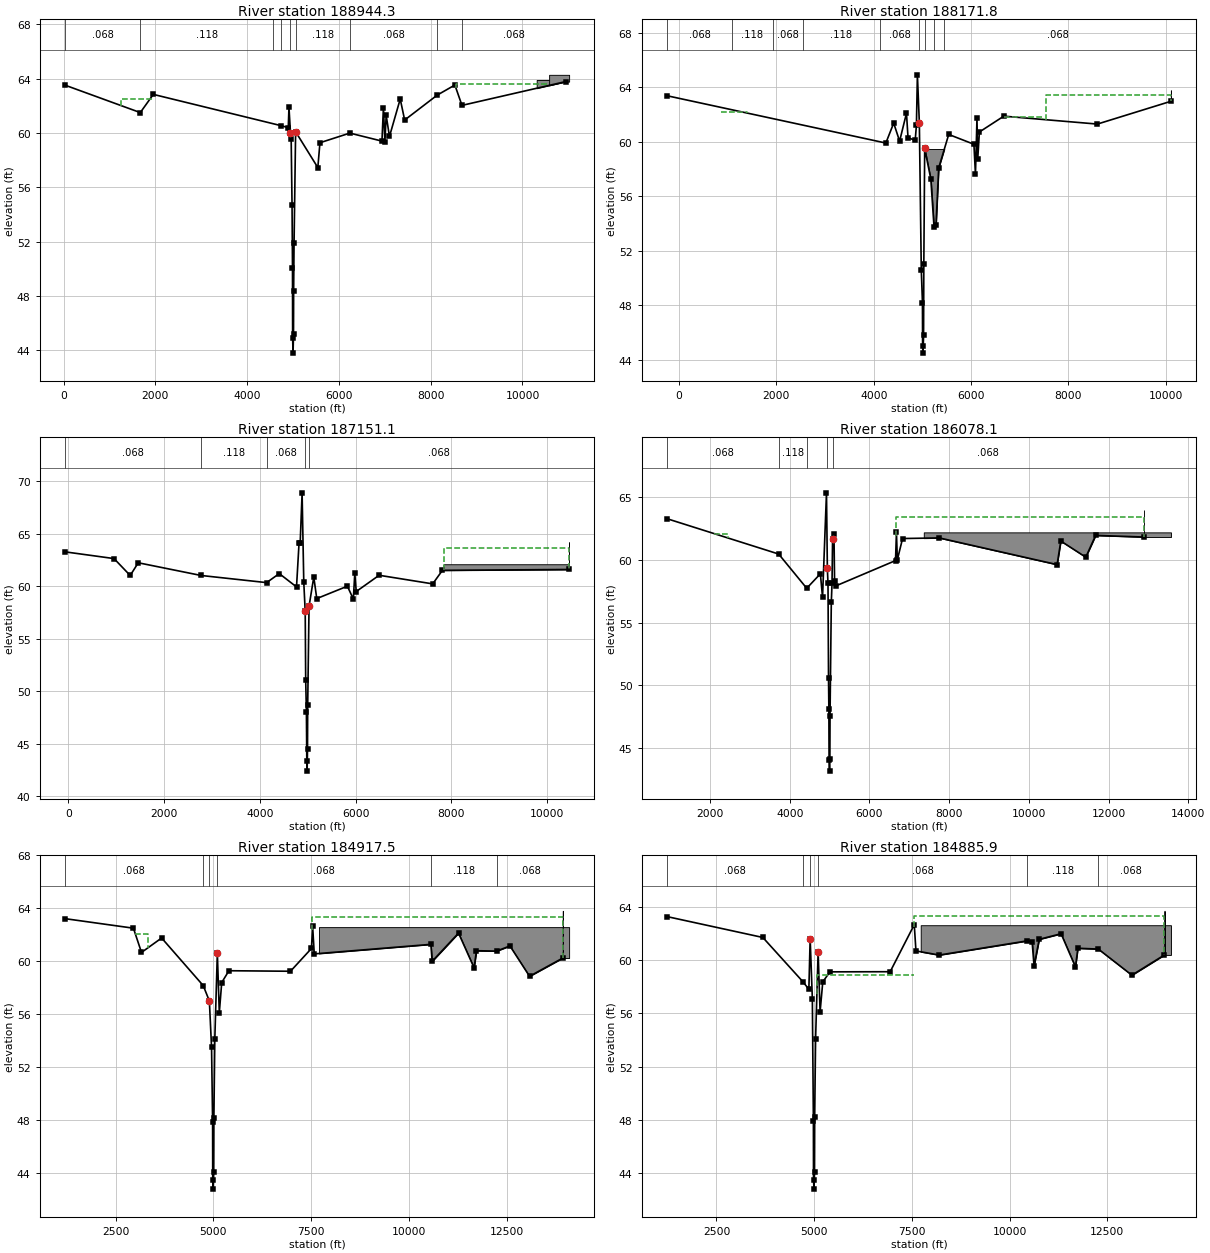
Type RM Length L Ch R = 1 ,188944.3,279.93,772.5,835.96
XS GIS Cut Line= 6
     3225271.312     13934649.67     3225094.556    13933046.114
     3224615.747    13931938.013     3223260.991    13930444.009
     3223022.469    13930342.987     3221009.474    13924889.748
#Sta/Elev= 30
   30.88   63.53 1671.44   61.51 1955.32   62.85  4736.3   60.55  4896.5    60.4
  4911.5    61.9  4944.5      60  4959.5    59.6  4978.5    54.7  4988.5    50.1
  4991.5    44.9  5000.5    43.8  5010.5    45.2  5013.5    48.4  5022.5    51.9
  5056.5    60.1 5540.46   57.46  5586.7   59.29    6238      60 6938.04   59.41
 6970.02   61.88    7002   59.36 7030.02    61.3 7101.48   59.75 7336.04   62.51
 7432.64   60.96 8143.74    62.8 8526.98   63.54 8681.72   62.0410940.04   63.79
#Mann= 9 ,-1 , 0
   30.88    .068       0 1671.44    .118       0 4568.72    .068       0
  4736.3    .118       0  4944.5     .04       0  5056.5    .118       0
    6238    .068       0 8143.74    .118       0 8681.72    .068       0
#XS Ineff= 3 ,-1
 8546.08 10525.6   63.62 1258.64 1959.48   62.51 6970.64 7293.64   61.57
Permanent Ineff=
       F       F       F
#Block Obstruct= 2 ,-1
10309.9510940.04   63.91 10580.811016.39   64.29
Bank Sta=4944.5,5056.5
XS Rating Curve= 0
Exp/Cntr=.3,.1

Type RM Length L Ch R = 1 ,188171.8,429.37,1020.75,1137.53
XS GIS Cut Line= 6
     3225390.506    13934441.081      3225084.46    13932356.946
     3223995.881    13930856.092     3223446.748     13929992.42
     3223388.969    13929512.856     3222056.246    13924811.506
#Sta/Elev= 30
 -249.36   63.37 4248.94    59.9 4410.22   61.36 4531.84   60.04 4672.92   62.09
 4704.44   60.29    4852    60.1    4877    61.2    4897    64.9    4937    61.4
    4977    50.6    5001    48.2    5004      45    5012    44.5    5024    45.8
    5029      51    5047    59.5 5172.98   57.26 5238.14   53.78 5279.82   53.91
 5334.82   58.08 5540.34   60.53 6058.06   59.81 6089.58    57.6 6120.76    61.7
 6136.36   58.73 6170.66   60.71 6671.68   61.87 8593.24   61.29 10104.4   62.96
#Mann= 9 ,-1 , 0
 -249.36    .068       0 1096.64    .118       0 1924.94    .068       0
 2546.16    .118       0 4126.22    .068       0    4937     .04       0
    5047    .068       0 5238.14    .118       0 5445.22    .068       0
#XS Ineff= 4 ,-1
 7540.39 10104.4    63.4   853.4 1387.37    62.2 6672.83 7475.59   61.82
 6119.57 6425.77    61.1
Permanent Ineff=
       F       F       F       F
#Block Obstruct= 2 ,-1
 5050.19 5449.46   59.4610103.8910104.87   63.77
Bank Sta=4937,5047
XS Rating Curve= 0
Exp/Cntr=.3,.1

Type RM Length L Ch R = 1 ,187151.1,1215.84,1072.97,1094.67
XS GIS Cut Line= 6
       3225509.7    13934396.383     3225283.291    13932315.041
     3224199.457    13930491.514     3224258.541    13929842.195
     3224428.988    13929538.857     3224445.016     13924231.01
#Sta/Elev= 30
  -66.71   63.28  956.53   62.64  1294.4   61.03 1462.65   62.24 2774.44   61.03
  4142.4   60.35 4406.67   61.21 4766.58   59.94 4819.72   64.15    4843    64.1
    4883    68.9    4918    60.4    4948    57.6    4958    51.1    4973      48
    4981    43.4    4988    42.4    4996    44.5    5000    48.7    5028    58.1
 5126.94   60.88 5189.36   58.83 5828.11   60.01 5952.91   58.78 5982.91   61.24
 6012.91    59.5 6491.19   61.05 7609.22   60.23  7812.9   61.5210456.05    61.6
#Mann= 5 ,-1 , 0
  -66.71    .068       0 2774.44    .118       0  4142.4    .068       0
    4948     .04       0    5028    .068       0
#XS Ineff= 2 ,-1
    784310456.05   63.63   970.2  1470.8   62.16
Permanent Ineff=
       F       F
#Block Obstruct= 3 ,-1
 7835.2810456.05    62.110455.9510456.91   64.2110456.1410457.29   64.19
Bank Sta=4948,5028
XS Rating Curve= 0
Exp/Cntr=.3,.1

Type RM Length L Ch R = 1 ,186078.1,556.92,1160.61,1052.74
XS GIS Cut Line= 6
     3225584.196    13934396.383     3225424.644    13932108.542
     3225018.332    13930549.986     3225260.988    13929838.649
     3225900.871     13925150.81     3225660.294    13922581.704
#Sta/Elev= 30
  913.16   63.25 3719.78   60.44 4424.46   57.72  4767.3   58.87  4821.5      57
  4920.5    65.3  4942.5    59.3  4958.5    58.1  4971.5    50.6  4980.5    48.1
  4985.5    44.1  4996.5    43.2  5005.5    44.2  5009.5    47.6  5041.5    56.6
  5059.5    58.1  5073.5    61.6  5108.5      62  5123.5    58.3  5148.5    57.9
 6653.32   59.92 6676.66   62.17 6698.74   59.98 6829.92   61.67  7749.6   61.72
10708.56    59.610802.46   61.47 11428.6   60.1911676.54   61.92 12880.5   61.79
#Mann= 5 ,-1 , 0
  913.16    .068       0 3719.78    .118       0 4424.46    .068       0
  4942.5     .04       0  5073.5    .068       0
#XS Ineff= 2 ,-1
 2085.82 2452.92   62.03 6673.49 12880.5   63.36
Permanent Ineff=
       F       F
#Block Obstruct= 2 ,-1
  7362.813566.58   62.1612880.4512881.21   63.97
Bank Sta=4942.5,5073.5
XS Rating Curve= 0
Exp/Cntr=.3,.1

Type RM Length L Ch R = 1 ,184917.5,45.28,31.63,36.44
XS GIS Cut Line= 6
     3225652.476    13935012.102      3225652.45    13931461.479
     3225709.728    13931347.976     3225862.785    13931067.534
     3227226.676    13925186.063     3226586.017    13922571.483
#Sta/Elev= 30
 1207.44   63.21 2956.64   62.49  3163.1   60.66 3677.82   61.75 4740.72   58.16
    4898      57    4954    53.5    4981    47.9    4984    43.5    4997    42.8
    5010    44.1    5014    48.2    5037    54.1    5102    60.6    5152    56.1
 5213.88   58.39 5398.42   59.28 6971.74   59.24 7507.64   60.96 7538.42   62.63
 7579.24   60.5510560.42   61.2710593.42   59.9911267.78   62.1211665.06    59.5
11726.66   60.7912238.62   60.7612582.12   61.1513083.18   58.8613934.16   60.24
#Mann= 6 ,-1 , 0
 1207.44    .068       0 4740.72    .118       0    4898     .04       0
    5102    .068       010560.42    .118       012238.62    .068       0
#XS Ineff= 2 ,-1
 3003.58 3320.62   62.04 7533.5613934.16   63.34
Permanent Ineff=
       F       F
#Block Obstruct= 2 ,-1
 7699.55 14094.6   62.57   1393413934.62    63.8
Bank Sta=4898,5102
XS Rating Curve= 0
Exp/Cntr=.5,.3

Type RM Length L Ch R = 1 ,184885.9,428.07,370.94,401.63
XS GIS Cut Line= 6
     3225682.476    13935012.266      3225682.45     13931468.62
     3225736.249    13931362.012     3225891.123    13931078.133
     3227257.516    13925185.871     3226615.155    13922564.343
#Sta/Elev= 30
 1230.69   63.26 3687.65   61.69 4712.15   58.37    4865    57.8    4898    61.6
    4954    57.1    4981    47.9    4984    43.5    4997    42.8    5010    44.1
    5014    48.2    5037    54.1    5102    60.6    5152    56.1 5221.21   58.36
 5405.09   59.11 6945.61   59.12 7561.75   62.65 7605.25   60.68  8200.6   60.37
 10441.8   61.4310577.71   61.3610627.24   59.5510758.88   61.5511318.76   61.97
11686.22   59.4811748.43   60.8812271.76   60.8213130.05   58.8613964.84   60.38
#Mann= 6 ,-1 , 0
 1230.69    .068       0 4712.15    .118       0    4898     .04       0
    5102    .068       0 10441.8    .118       012271.76    .068       0
#XS Ineff= 3 ,-1
 1230.69 4930.23   58.91  5070.2 7562.56   58.87 7565.4213964.84   63.29
Permanent Ineff=
       F       F       F
#Block Obstruct= 2 ,-1
 7726.9414129.92   62.6113964.5413967.17   63.69
Bank Sta=4898,5102
XS Rating Curve= 0
Exp/Cntr=.5,.3

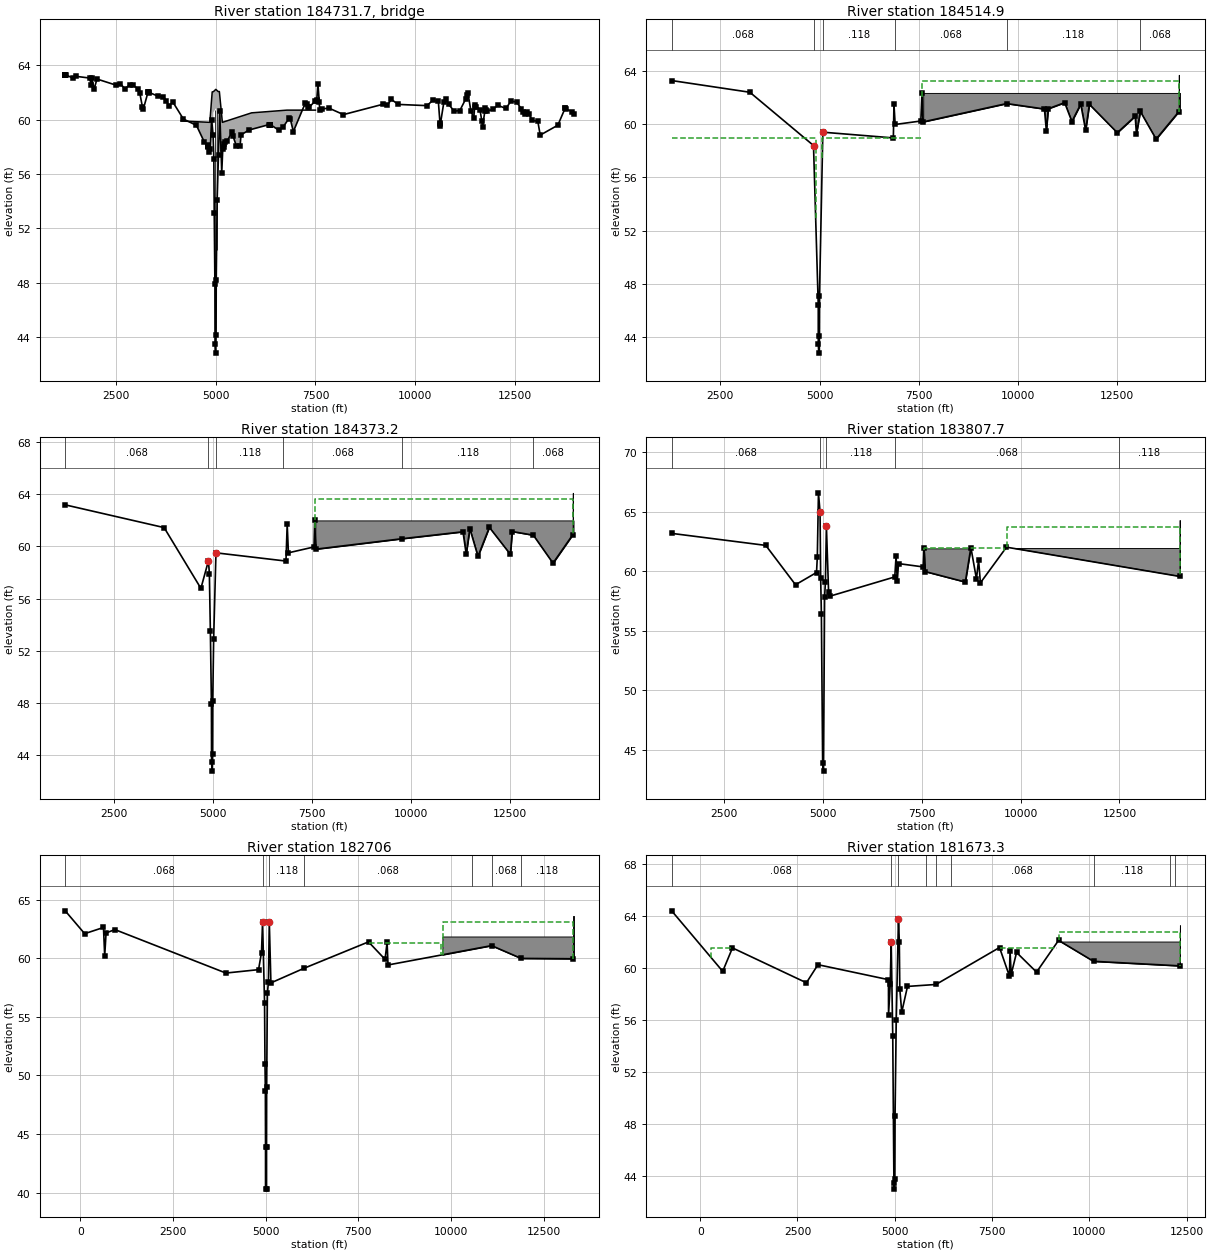
Type RM Length L Ch R = 3 ,184731.7,,,
Node Photo=G:\C2001-041_Harris_County_FEMA\3-Cedar_Bayou\Cedar_Bayou\Survey _info\121s58_crosby_eastgate\121S58P8.jpg
BEGIN DESCRIPTION:
Crosby Eastgate Road
END DESCRIPTION:
Bridge Culvert--1,0,-1,-1, 0
Deck Dist Width WeirC Skew NumUp NumDn MinLoCord MaxHiCord MaxSubmerge Is_Ogee
137,32.2,2.6,0, 11, 11, , , .95, 0, 0,0,,
  4137.3  4853.3  4912.7  4942.7  5003.7  5062.7  5092.7  5167.8  5899.3  6785.9
    7500
    59.9    59.8   62.04   62.06   62.23   62.07   62.07    59.8    60.5    60.7
    60.7
       0       0       0   60.53   60.83   60.55       0       0       0       0
       0
  4137.3  4853.3  4912.7  4942.7  5003.7  5062.7  5092.7  5167.8  5899.3  6785.9
    7500
    59.9    59.8   62.04   62.06   62.23   62.07   62.07    59.8    60.5    60.7
    60.7
       0       0       0   60.53   60.83   60.55       0       0       0       0
       0
Pier Skew, UpSta & Num, DnSta & Num=  ,4982.5, 2 ,4982.5, 2 , 0 , 0 , 0 ,,
     1.6     1.6
       0      61
     1.6     1.6
       0      61
Pier Skew, UpSta & Num, DnSta & Num=  ,5022.5, 2 ,5022.5, 2 , 0 , 0 , 0 ,,
     1.6     1.6
       0      61
     1.6     1.6
       0      61
BR Coef=-1 , 1 , 1 ,.9, 0 ,,,.8,0,2,0,
WSPro=,,,, 1 ,,,, 0 ,,,, 0 ,,,,-1 ,-1 ,-1 , 0 , 0 , 0 , 0 , 0
BR U #Sta/Elev= 142
 1230.69   63.26 1234.12   63.28 1235.37   63.29  1235.7   63.29  1236.2   63.28
 1239.86    63.3 1430.86   63.05 1499.82   63.19 1850.37   63.06 1875.78   62.53
 1903.74   63.03 1952.02   62.23 2027.23   62.99 2493.59   62.55 2612.57   62.66
 2725.18   62.26 2850.52   62.58 2930.05   62.52 3058.24   62.27 3100.97   61.93
 3166.51   60.91 3191.03   60.81  3302.8      62 3315.06   62.01  3327.5   61.99
 3338.56      62 3558.36   61.72 3687.65   61.69 3765.95    61.4 3822.08   61.03
  3928.6   61.29 4191.94   60.04 4518.09   59.58 4712.15   58.37 4809.36   58.05
 4810.29   58.03 4811.22   58.02 4812.19   58.04 4812.97   58.04    4815    58.1
    4840    57.6    4865    57.8    4898      60    4934    58.9    4954    57.1
    4964    53.1    4981    47.9    4984    43.5    4997    42.8    5010    44.1
    5014    48.2    5037    54.1    5071    57.4    5102    60.6    5152    56.1
    5177    57.8    5202      58 5217.14   58.24 5221.21   58.36 5293.21   58.42
 5405.09   59.11 5430.94   58.81 5517.91   58.07 5611.75   58.04 5633.98   58.87
 5830.14   59.23  6345.8   59.64 6354.75    59.6 6357.34    59.6 6359.13   59.63
 6361.36   59.59 6365.46   59.61 6368.74   59.61 6372.68   59.63 6581.85   59.22
  6684.4   59.43 6846.11   60.13 6869.61   60.05 6945.61   59.12 7240.91   61.19
 7291.52   61.13 7319.16   60.93 7346.25   60.93 7498.17   61.38 7530.96   61.36
 7532.17   61.45 7561.75   62.65 7594.94   61.31 7605.25   60.68 7651.21   60.78
 7836.76   60.85  8200.6   60.37 9202.83   61.14 9299.63   61.06  9400.1   61.49
 9573.63   61.1210294.06   61.03 10441.8   61.4310577.71   61.3610621.02   59.68
10627.24   59.5510631.49   59.7210717.78   61.3110758.88   61.5510833.08   61.14
 10975.4   60.6211116.29   60.6711265.76   61.5311288.14    61.811318.76   61.97
11393.74   60.6411464.77    60.111492.64   61.1111502.33   60.93 11519.8   60.96
11621.97   60.7311668.01   59.8811686.22   59.4811743.45   60.6311748.43   60.88
11760.57   60.7311792.78   60.6211953.18   60.77 12064.4   61.0612271.76   60.82
12394.92   61.3612540.32    61.312655.82   60.7912689.24   60.5712747.32    60.4
12786.19   60.4612800.02   60.5312842.27   60.4412931.99   59.9413069.94   59.88
13130.05   58.8613571.99   59.5913753.54   60.8413759.91   60.8513769.99    60.8
13929.03   60.5813964.84   60.38
BR U #Mann= 6
 1230.69    .068 4712.15    .118    4934     .04    5071    .068 10441.8    .118
12271.76    .068
BR D #Sta/Elev= 161
    1270   63.28 1351.88   63.12 1599.64   63.13  1609.3   63.44  1643.5   62.96
  1803.3   62.46  1932.8    62.5 2083.56   62.87 2105.64   62.53  2315.5   61.66
 2360.74   61.76 2643.64   61.96 2821.52   62.53 2876.44   61.99 2954.94      62
  3017.2   62.35  3242.9    62.4 3629.84   61.84  3762.8   61.58 3827.86   61.22
 3833.72   61.18  4036.7   60.38 4306.94   59.74  4308.9   59.69  4311.7   59.73
  4505.7   59.41 4520.46   58.93 4584.38   58.79  4591.7   58.62 4598.46   58.69
 4725.94   58.71 4758.14   59.15  4779.4   58.98  4784.5   58.91    4800    58.6
    4825    58.8  4848.5    58.4    4883    55.1  4917.6    50.8    4939    48.5
    4949    47.4  4968.5    46.4    4969    43.5    4982    42.8    4995    44.1
    4999    47.1    5022    49.5    5040    51.8  5051.4    54.6    5060    56.1
  5074.7    57.8  5084.2    59.4 5108.76   60.01 5118.32   60.16 5132.48   60.47
  5163.6   59.36 5196.54   58.04 5196.64   58.04 5460.58   58.86 5524.76   59.16
 5564.28   59.28  5864.7   59.66 5875.94   59.66 5905.44   59.73 5919.12   59.71
  6023.1   59.83 6444.08   60.02  6491.6   60.12 6513.28      60 6679.04   60.17
 6841.16    60.1 6862.92   58.99 6863.04   58.97 6863.52   59.05 6865.62   59.39
 6909.24   59.39 7354.38    60.4 7364.52    60.4  7370.2   60.44  7417.2   60.42
 7543.54   60.85 7555.96   60.24 7565.44   61.03 7586.76   62.36  7601.7   61.27
 7610.46   60.17    7635   60.51 7648.42   60.61 7744.52    61.1  8522.5   60.07
 8943.28    60.4 9191.86    60.2 9449.88   61.28  9452.3   61.27  9706.1   61.51
 9722.76   61.55 9727.08   61.66 9733.76   61.54 9866.46   61.11  9916.3   61.22
10145.42   60.6210151.44   60.6710158.22    60.8   10170   60.6410300.88   61.15
10365.38   60.6810556.78   60.8710675.18   61.1410724.06    59.510759.36   60.57
   10771   61.1610778.94   61.1210844.22   61.0611105.36   61.3811185.28   61.62
 11319.1   60.6511348.16    60.511367.54    60.211401.06   61.1711530.96   61.12
11591.04   61.5111651.28   61.2411689.36   60.4211712.06   59.66 11714.6   59.54
11722.92   59.69   11810   61.4911861.98   60.7711873.72   60.7911877.28   60.73
11953.94      6111975.34    60.312212.58   59.7412451.46   60.6312493.52   59.65
12513.52   59.36 12557.5   60.4412561.64   60.55   12564   60.64 12579.4   60.61
12858.36   60.47   12964    60.612965.36    60.612966.18   60.5812996.42   59.26
13094.26   60.9613101.34   61.0713103.14   61.1113105.42   61.11 13107.7   61.08
13417.62   59.24 13492.8   58.8813656.48   60.1413660.32   60.15 13663.4   60.13
13758.78   59.3313801.04    59.213915.18   59.8113983.78    60.314039.84   60.92
14065.88   60.94
BR D #Mann= 6
    1270    .068    4883     .04  5051.4    .118 6909.24    .068 9722.76    .118
13094.26    .068
BC Design=,, 0 ,, 0 ,,,,,,
BC HTab HWMax=63.3

Type RM Length L Ch R = 1 ,184514.9,120.55,141.75,121.4
XS GIS Cut Line= 6
     3226052.464    13935014.288     3226052.438    13931504.891
     3226083.042    13931444.248     3226250.032    13931137.462
     3227633.107    13925173.261     3226979.396    13922505.412
#Sta/Elev= 30
    1270   63.28  3242.9    62.4  4848.5    58.4  4968.5    46.4    4969    43.5
    4982    42.8    4995    44.1    4999    47.1  5084.2    59.4 6863.04   58.97
 6878.44   61.49 6909.24   59.98 7555.96   60.24 7586.76   62.36 7610.46   60.17
 9722.76   61.5510675.18   61.1410724.06    59.5   10771   61.1611185.28   61.62
11367.54    60.211591.04   61.51 11714.6   59.54   11810   61.4912513.52   59.36
12965.36    60.612996.42   59.2613094.26   60.96 13492.8   58.8814065.88   60.94
#Mann= 6 ,-1 , 0
    1270    .068       0  4848.5     .04       0  5084.2    .118       0
 6909.24    .068       0 9722.76    .118       013094.26    .068       0
#XS Ineff= 3 ,-1
    1270 4905.04   58.98 5070.96 7590.49      59 7590.4914065.83   63.26
Permanent Ineff=
       F       F       F
#Block Obstruct= 2 ,-1
 7616.5914095.69   62.3514065.0714066.39   63.71
Bank Sta=4848.5,5084.2
XS Rating Curve= 0
Exp/Cntr=.5,.3

Type RM Length L Ch R = 1 ,184373.2,668.98,565.5,510.17
XS GIS Cut Line= 6
     3226172.464    13935014.944     3226172.439    13931533.454
     3226286.427     13931324.85     3226363.384    13931179.858
      3227756.47    13925172.494     3227095.948    13922476.853
#Sta/Elev= 30
 1261.36   63.17  3760.4   61.43 4689.86   56.78  4881.3    58.9  4903.7    57.9
    4929    53.5    4956    47.9    4959    43.5    4972    42.8    4985    44.1
    4989    48.2    5012    52.9  5070.4    59.5 6839.26   58.87 6870.06   61.69
 6900.86    59.5 7547.58   59.95 7562.98   61.98 7593.46   59.78  9775.6   60.58
 11311.5   61.1111393.06    59.4 11484.8   61.3511690.76   59.2311977.52   61.45
12509.28   59.3812555.62   61.13 13089.2   60.8513585.92   58.71 14086.9   60.89
#Mann= 6 ,-1 , 0
 1261.36    .068       0  4881.3     .04       0  5070.4    .118       0
 6776.34    .068       0  9775.6    .118       0 13089.2    .068       0
#XS Ineff= 2 ,-1
 6871.88 7564.08   61.27  7571.1 14086.9   63.58
Permanent Ineff=
       F       F
#Block Obstruct= 2 ,-1
 7580.9714104.89   61.9814086.6714086.98   64.09
Bank Sta=4881.3,5070.4
XS Rating Curve= 0
Exp/Cntr=.3,.1

Type RM Length L Ch R = 1 ,183807.7,1155.95,1101.69,1009.43
XS GIS Cut Line= 6
     3226955.982    13935158.603     3226810.042    13931541.963
     3226895.036    13931133.992     3228346.466    13924465.927
      3229197.16    13923458.982     3229764.434    13923088.756
#Sta/Elev= 30
 1168.86   63.19  3550.3   62.18  4302.7   58.87  4834.5    59.9  4854.5    61.2
  4883.5    66.6  4923.5      65  4939.5    59.4  4957.5    56.4  4989.5    43.9
  5011.5    43.2  5038.5    57.8  5059.5    59.1  5084.5    63.8  5139.5    58.3
  5164.5    57.9 6814.76   59.53  6847.7   61.28  6878.4   59.19  6909.1   60.65
 7533.96   60.37 7553.84   61.95 7584.56   59.98 8599.98    59.1 8741.04      62
 8882.08   59.35 8935.46   60.97 8981.52   59.03 9641.62   62.0314025.04   59.57
#Mann= 5 ,-1 , 0
 1168.86    .068       0  4923.5     .04       0  5084.5    .118       0
 6825.58    .068       0 12482.3    .118       0
#XS Ineff= 2 ,-1
 9642.5414025.04   63.72 7556.35 9572.19   61.92
Permanent Ineff=
       F       F
#Block Obstruct= 3 ,-1
 7553.79 8741.61   61.93  9614.314032.79   61.9314024.7114025.75   64.32
Bank Sta=4923.5,5084.5
XS Rating Curve= 0
Exp/Cntr=.3,.1

Type RM Length L Ch R = 1 ,182706  ,1026.2,1032.66,999.88
XS GIS Cut Line= 6
     3228207.248    13936791.376     3228050.893    13933205.944
     3227910.163    13931156.664     3228597.768    13924820.527
     3229363.393     13923890.84     3229727.976    13923562.715
#Sta/Elev= 30
 -409.24   64.05  115.36    62.1  623.68   62.63  656.06    60.2  693.22   62.16
  930.36   62.45 3925.88   58.74 4806.52   59.03 4886.38   60.49 4915.25    63.1
 4968.75    56.2 4980.25      51 4990.75    48.7 4995.25    43.9  4995.3    40.3
  5022.2    40.3 5022.25    43.9 5025.75      49 5045.25      57 5073.25      58
 5096.75    63.1 5140.25    57.9 6035.24   59.15 7773.64    61.4 8219.04   59.91
 8274.48   61.35 8299.86   59.4311093.02   61.0811890.14   59.99 13302.4   59.96
#Mann= 7 ,-1 , 0
 -409.24    .068       0 4915.25     .04       0 5096.75    .118       0
 6035.24    .068       010560.08    .118       011093.02    .068       0
11890.14    .118       0
#XS Ineff= 3 ,-1
 9785.29 13302.4   63.11  536.35  822.41    62.3 7786.37 9735.39   61.32
Permanent Ineff=
       F       F       F
#Block Obstruct= 2 ,-1
 9767.23 13302.4   61.8613302.0713304.39   63.65
Bank Sta=4915.25,5096.75
XS Rating Curve= 0
Exp/Cntr=.3,.1

Type RM Length L Ch R = 1 ,181673.3,1097.91,1095.7,1042.56
XS GIS Cut Line= 6
     3230079.808    13936732.117     3229085.965    13933082.614
     3228912.626    13930896.659     3229053.497    13925021.048
     3229399.851    13924401.256     3229691.518    13924000.215
#Sta/Elev= 30
 -732.65   64.39  578.46   59.74  829.29   61.54 2729.04   58.86 3025.68   60.25
 4837.34    59.1  4839.5    56.4  4883.5    58.8  4907.5      62  4947.5    54.8
  4977.5    43.5  4989.5      43  5000.5    43.8  5006.5    48.6  5037.5      56
  5094.5    63.8  5116.5      62  5128.5    58.4  5178.5    56.6 5326.28   58.58
 6057.73   58.73 7690.95   61.57  7945.9   59.37  7960.9   61.31 7990.91   59.51
 8129.09   61.19 8642.11   59.68 9208.01   62.1210105.85   60.5112325.78   60.16
#Mann= 9 ,-1 , 0
 -732.65    .068       0  4907.5     .04       0  5094.5    .118       0
 5796.56    .068       0 6057.73    .118       0 6449.49    .068       0
10105.85    .118       012064.61    .068       0 12195.2    .118       0
#XS Ineff= 3 ,-1
 9208.0412325.78   62.74 7692.24 9158.47   61.57  286.71  838.43   61.52
Permanent Ineff=
       F       F       F
#Block Obstruct= 3 ,-1
 9207.1512325.78   62.0312325.72   12328   63.0812325.7212327.09   63.29
Bank Sta=4907.5,5094.5
XS Rating Curve= 0
Exp/Cntr=.3,.1

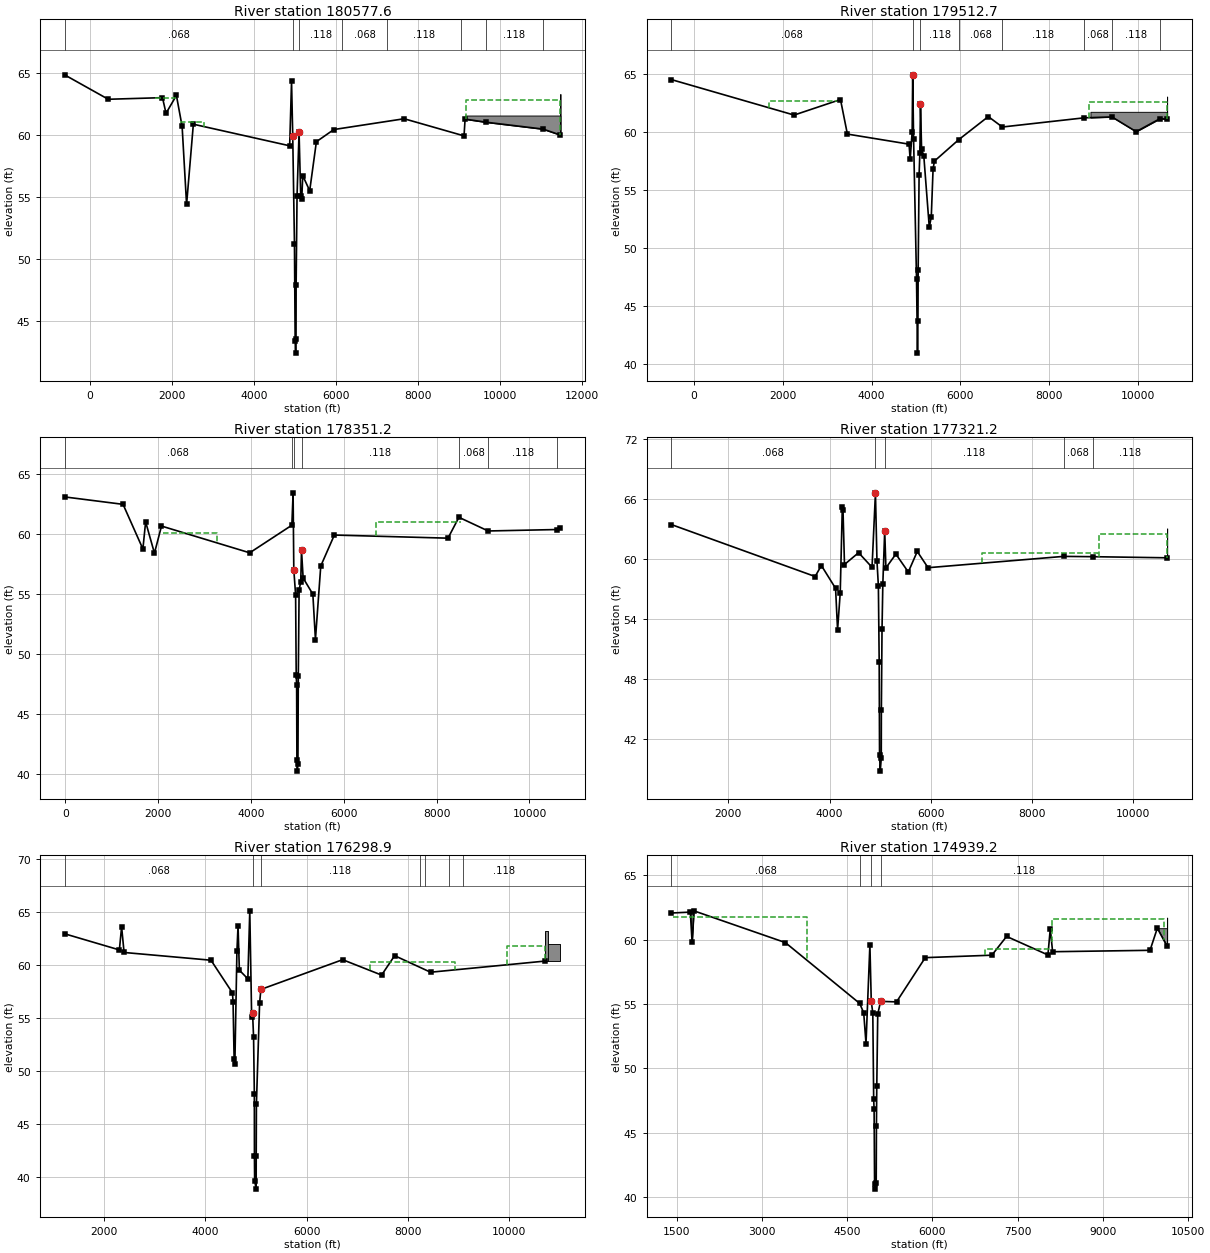
Type RM Length L Ch R = 1 ,180577.6,1113.12,1064.92,1020.96
XS GIS Cut Line= 6
     3231004.236    13936364.716     3230161.596    13932902.233
     3230005.292    13930948.515     3229952.645    13930645.321
     3229527.455    13924838.756     3229819.122    13924528.861
#Sta/Elev= 30
 -610.66   64.83  453.57   62.86 1774.94   62.99  1860.9   61.73 2114.24   63.17
 2253.26   60.67  2361.9   54.38 2526.72   60.85 4873.86   59.11  4919.5    64.3
  4948.5    59.9  4990.5    51.2  5007.5    43.4  5018.5    42.4  5028.5    43.5
    5031    47.9  5053.5    55.1  5102.5    60.2  5142.5    55.1  5167.5    54.8
  5192.5    56.7 5361.88   55.49 5524.78   59.44 5949.88   60.42  7663.3   61.29
 9122.18   59.91 9147.94   61.26  9659.1   61.01 11042.7   60.4611468.26   59.98
#Mann= 8 ,-1 , 0
 -610.66    .068       0  4948.5     .04       0  5102.5    .118       0
 6153.54    .068       0 7240.64    .118       0 9052.48    .068       0
  9659.1    .118       0 11042.7    .068       0
#XS Ineff= 5 ,-1
 1604.29 2104.89   62.98 9164.9611468.26   62.84 2201.43 2796.65   60.99
 7663.81 9149.23   60.89 5114.22 5538.46    58.7
Permanent Ineff=
       F       F       F       F       F
#Block Obstruct= 2 ,-1
 9147.2211468.26   61.5511467.8811469.91   63.29
Bank Sta=4948.5,5102.5
XS Rating Curve= 0
Exp/Cntr=.3,.1

Type RM Length L Ch R = 1 ,179512.7,1321.54,1161.51,1075.28
XS GIS Cut Line= 5
     3232023.478    13936021.019     3231322.541    13932716.255
     3231047.078    13930695.961     3231004.741    13930526.159
     3229983.184    13925057.506
#Sta/Elev= 30
 -505.24   64.49 2257.14   61.43 3300.54   62.77 3455.72   59.79  4843.4   58.92
  4868.5    57.6  4913.5      60  4925.5    64.9  4945.5    59.4  5011.5    47.3
  5033.5    40.9  5043.5    43.7  5048.5    48.1  5069.5    56.3  5087.5    58.2
  5100.5    62.4  5125.5    58.5  5175.5    57.9 5298.92   51.74  5343.7   52.66
  5384.1   56.79 5414.62   57.46 5964.96   59.32 6626.68    61.3 6942.56    60.4
 8780.04   61.19 9409.34   61.27 9953.76      6010491.12   61.1210650.28   61.08
#Mann= 8 ,-1 , 0
 -505.24    .068       0  4925.5     .04       0  5100.5    .118       0
 5964.96    .068       0 6942.56    .118       0 8780.04    .068       0
 9409.34    .118       010491.12    .068       0
#XS Ineff= 4 ,-1
 1687.72 3222.88   62.61  8894.210650.28   62.57 6625.29  8894.2   61.09
 5146.85 5832.17   58.04
Permanent Ineff=
       F       F       F       F
#Block Obstruct= 3 ,-1
 8925.5510650.28   61.7110649.8710650.88   63.0310650.37 10651.9   62.95
Bank Sta=4925.5,5100.5
XS Rating Curve= 0
Exp/Cntr=.3,.1

Type RM Length L Ch R = 1 ,178351.2,1026.09,1030.04,1060.32
XS GIS Cut Line= 6
     3233767.445    13935054.341     3232881.622    13932458.548
     3232161.521    13930348.384     3232135.699    13930277.437
     3232061.573    13930081.978     3230311.309    13924948.131
#Sta/Elev= 30
  -14.72   63.06  1244.9   62.44 1672.34   58.72  1731.1   60.98 1921.28   58.37
 2072.96   60.63 3973.46    58.4 4881.25    60.7 4908.25    63.4 4923.25      57
 4962.25    54.9 4975.25    48.2 4984.25    47.4 4990.25    41.1 4999.25    40.2
 5012.25    40.8 5020.25    48.1 5037.75    55.3 5073.25      56 5089.25    58.6
 5124.25    56.3 5333.74   54.95 5389.34   51.17  5504.1    57.3 5796.64   59.88
 8244.76   59.62 8480.54   61.36 9110.06   60.2210595.24   60.3410666.26   60.44
#Mann= 7 ,-1 , 0
  -14.72    .068       0 4881.25    .118       0 4923.25     .04       0
 5089.25    .118       0 8480.54    .068       0 9110.06    .118       0
10595.24    .068       0
#XS Ineff= 5 ,-1
   791.6 1076.45   62.21 6695.94 8523.51   60.94 1361.29 2075.25   60.61
 2108.55 3262.72   60.02 5130.54 5603.73   55.91
Permanent Ineff=
       F       F       F       F       F
#Block Obstruct= 2 , 0
                         8655.01           62.51
Bank Sta=4923.25,5089.25
XS Rating Curve= 0
Exp/Cntr=.3,.1

Type RM Length L Ch R = 1 ,177321.2,1094.57,1022.26,868.66
XS GIS Cut Line= 6
     3234866.283    13933801.254     3233155.059    13930307.506
      3233149.55     13930162.85      3233149.55     13929979.85
     3233155.059    13929833.548     3230657.663    13925002.819
#Sta/Elev= 30
  873.12   63.43 3715.88   58.24 3839.12   59.34 4120.08   57.06 4159.56    52.9
 4211.98    56.6 4253.48    65.2  4266.9   64.87 4296.28   59.44 4574.96   60.62
 4841.14   59.16  4908.5    66.6  4938.5    59.8  4966.5    57.3  4982.5    49.7
  4989.5    40.4  5003.5    38.8  5023.5    40.1  5025.5    44.9  5038.5      53
  5054.5    57.5  5091.5    62.8  5115.5    59.1  5312.3   60.48  5558.2   58.69
 5735.22   60.74 5948.76   59.12  8626.9   60.25  9211.1   60.22 10675.7   60.11
#Mann= 5 ,-1 , 0
  873.12    .068       0  4908.5     .04       0  5091.5    .118       0
  8626.9    .068       0  9211.1    .118       0
#XS Ineff= 3 ,-1
 9320.65 10675.7   62.47 4264.27  4890.7   60.95 7024.57 9316.15   60.61
Permanent Ineff=
       F       F       F
#Block Obstruct= 1 ,-1
10675.4410676.75   63.05
Bank Sta=4908.5,5091.5
XS Rating Curve= 0
Exp/Cntr=.3,.1

Type RM Length L Ch R = 1 ,176298.9,1729.01,1359.68,1015.24
XS GIS Cut Line= 6
     3235888.184    13933125.452     3234182.691    13930010.503
     3234139.044     13929854.49     3234103.068    13929720.227
     3234057.691    13929588.628     3230985.788    13925021.048
#Sta/Elev= 30
 1215.85   62.94 2298.53   61.42 2342.71   63.59 2391.63   61.18 4109.06   60.45
 4532.86   57.38 4544.88   56.55 4566.02   51.14 4580.59   50.68 4621.27   61.28
 4643.37   63.68  4669.8   59.51  4837.5    58.7  4875.5    65.1  4912.5    55.1
  4930.5    55.5  4950.5    53.2  4965.5    47.9  4967.5      42  4971.5    39.7
  5001.5    38.9  5002.5      42  5006.5    46.9  5069.5    56.4  5094.5    57.7
 6710.18    60.5 7480.48   59.05 7737.49   60.88 8447.84   59.3210711.83   60.37
#Mann= 7 ,-1 , 0
 1215.85    .068       0  4930.5     .04       0  5094.5    .118       0
 8242.88    .068       0 8337.84    .118       0 8812.63    .068       0
 9097.51    .118       0
#XS Ineff= 3 ,-1
 9956.0610709.84   61.77 7244.76 8937.06   60.25 4461.54 4657.34   56.04
Permanent Ineff=
       F       F       F
#Block Obstruct= 5 ,-1
10711.7810712.72   62.6110712.7511013.11   61.9410712.9710712.97   63.81
   1071410714.51   63.0810715.0210768.72   63.22
Bank Sta=4930.5,5094.5
XS Rating Curve= 0
Exp/Cntr=.3,.1

Type RM Length L Ch R = 1 ,174939.2,1109.92,953.62,920.11
XS GIS Cut Line= 6
     3237439.681    13931232.953     3236746.205    13930271.048
     3235052.483    13928921.961     3234788.589    13928824.285
     3234661.858    13928776.128     3231569.122    13924911.673
#Sta/Elev= 30
 1408.28   62.07 1741.72   62.14 1772.74   59.81 1804.18   62.24 3413.64   59.77
 4721.04   55.04 4791.62   54.31 4832.08   51.92  4900.5    59.6  4924.5    55.2
  4951.5    54.3    4967    47.6  4974.5    46.8    4983      41  4998.5    40.6
  5011.5    41.1  5015.5    45.5  5021.5    48.6  5038.5    54.2  5088.5    55.2
 5369.02   55.16 5874.46    58.6 7045.72   58.79 7305.12   60.25 8032.22   58.81
  8073.6   60.85 8114.38   59.06 9828.28   59.17  9956.4   60.8910126.06   59.51
#Mann= 4 ,-1 , 0
 1408.28    .068       0 4721.04    .118       0  4924.5     .04       0
  5088.5    .118       0
#XS Ineff= 4 ,-1
 1437.23 3800.87   61.77  8097.210069.21   61.61 6932.59 8069.93   59.25
 4643.36 4881.12   55.03
Permanent Ineff=
       F       F       F       F
#Block Obstruct= 3 ,-1
 1408.28 1806.66   62.04 9956.7710126.06   60.8910125.6410129.62   61.71
Bank Sta=4924.5,5088.5
XS Rating Curve= 0
Exp/Cntr=.3,.1

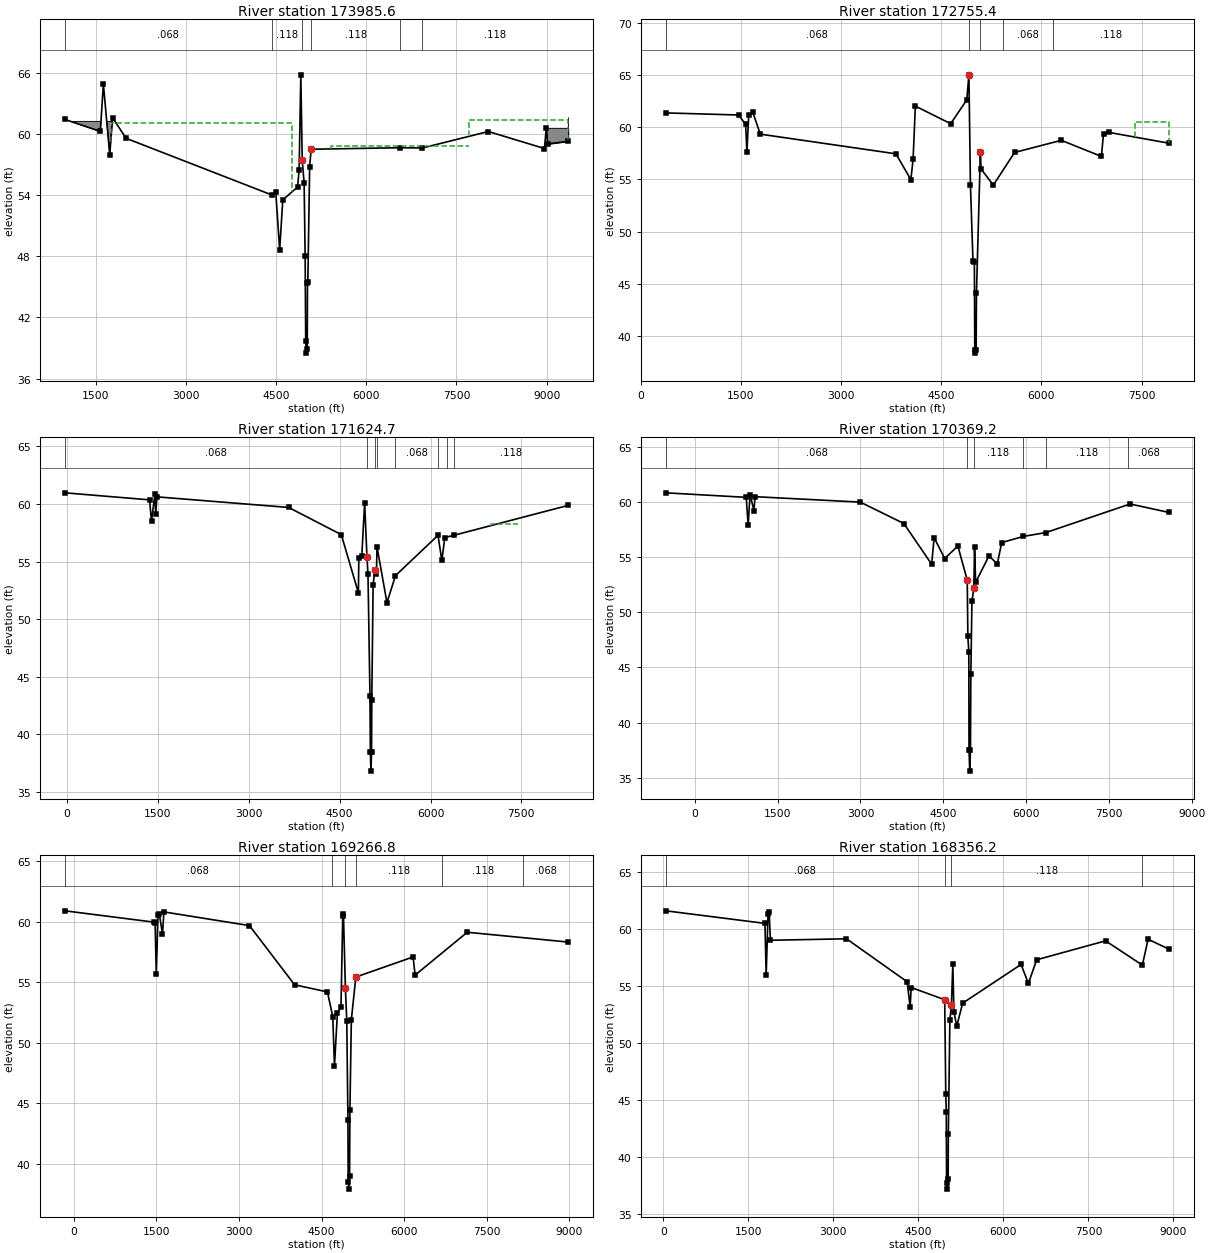
Type RM Length L Ch R = 1 ,173985.6,1189.87,1230.22,1160.88
XS GIS Cut Line= 6
     3238799.729    13929683.101     3235385.816    13928026.128
     3235217.276    13927965.834     3235130.824    13927934.368
     3235005.608    13927890.711     3232170.684    13924820.527
#Sta/Elev= 30
  983.12   61.42 1571.62   60.25  1622.6   64.89 1728.76   57.98 1775.72   61.59
  2001.9   59.57 4424.52   54.02 4491.72   54.31 4557.12   48.62 4608.92   53.53
    4856    54.8    4881    56.5    4909    65.8    4933    57.4    4964    55.2
    4981      48  4990.5    39.7    5003    38.5    5016    38.9    5020    45.4
    5026    45.5    5056    56.8    5081    58.5 6563.62   58.65 6930.96   58.62
 8030.78   60.24 8964.12   58.57 8995.54    60.6 9016.48   59.02 9360.36   59.28
#Mann= 6 ,-1 , 0
  983.12    .068       0 4424.52    .118       0    4933     .04       0
    5081    .118       0 6563.62    .068       0 6930.96    .118       0
#XS Ineff= 3 ,-1
 7703.98 9360.36   61.41 1745.16 4761.44   61.12  5412.2 7703.96   58.79
Permanent Ineff=
       F       F       F
#Block Obstruct= 3 ,-1
  983.12 1779.16   61.23 8995.55 9360.36    60.6 9360.36 9360.42   61.64
Bank Sta=4933,5081
XS Rating Curve= 0
Exp/Cntr=.3,.1

Type RM Length L Ch R = 1 ,172755.4,1140.4,1130.7,1093.88
XS GIS Cut Line= 6
     3239775.404    13928823.012     3235816.518    13926916.881
     3235693.366    13926841.344     3235540.113    13926763.258
     3235397.247    13926698.131     3233209.747    13925166.881
#Sta/Elev= 30
  375.72   61.36 1464.43   61.16 1569.97   60.26 1589.35   57.59 1616.66   61.18
 1675.47   61.47 1789.36   59.33 3821.05   57.45 4044.82   54.98 4078.02   56.92
 4112.17   62.01 4640.59   60.33    4882    62.6    4914      65    4937    54.5
    4975    47.2    4996    47.1    5002    38.7    5012    38.4    5022    38.7
    5027    44.1    5086    57.6    5096      56 5279.84   54.46  5598.3   57.58
  6298.2   58.74 6898.69    57.2 6929.85   59.37 7008.85    59.5 7913.26   58.46
#Mann= 5 ,-1 , 0
  375.72    .068       0    4914     .04       0    5086    .118       0
 5425.87    .068       0 6179.62    .118       0
#XS Ineff= 3 ,-1
 1197.76 4134.64   60.72 7403.26 7913.26   60.51 6297.81 7015.84   58.65
Permanent Ineff=
       F       F       F
#Block Obstruct= 2 , 0
         1617.84   60.84  7913.2           61.03
Bank Sta=4914,5086
XS Rating Curve= 0
Exp/Cntr=.3,.1

Type RM Length L Ch R = 1 ,171624.7,434.09,1255.52,1456.97
XS GIS Cut Line= 6
      3240307.78    13928317.448     3238095.163    13926698.131
     3236235.788    13925877.819     3235854.566    13925651.128
     3234120.738    13924775.008     3233327.159     13923944.19
#Sta/Elev= 30
  -35.43   60.97 1360.62   60.36  1393.8   58.52 1448.48   60.83 1462.68   59.12
  1483.1   60.62 3658.12    59.7  4526.8   57.34 4809.14   52.29  4816.5    55.3
  4865.5    55.5  4912.5    60.1  4950.5    55.4  4967.5    53.9  5000.5    43.3
  5006.5    38.5  5016.5    36.8  5026.5    38.5  5030.5      43  5052.5      53
  5082.5    54.3  5107.5    53.9 5116.34    56.3 5280.66   51.43 5421.82   53.78
 6123.62   57.28  6186.8    55.1 6236.88   57.09  6384.2   57.28 8273.86   59.88
#Mann= 8 ,-1 , 0
  -35.43    .068       0  4950.5     .04       0  5082.5    .068       0
 5116.34    .118       0 5421.82    .068       0 6123.62    .118       0
 6279.64    .068       0  6384.2    .118       0
#XS Ineff= 1 ,-1
 6996.42 7439.81   58.28
Permanent Ineff=
       F
#Block Obstruct= 2 , 0
         1489.87   60.64  8273.8           59.91
Bank Sta=4950.5,5082.5
XS Rating Curve= 0
Exp/Cntr=.3,.1

Type RM Length L Ch R = 1 ,170369.2,1217.98,1102.39,1014.76
XS GIS Cut Line= 6
     3240556.664    13928080.415     3238277.455    13926370.006
      3237074.33    13925823.131     3236429.653    13924867.438
     3235354.031    13922795.783     3234370.104    13921727.932
#Sta/Elev= 30
 -523.82   60.81  931.64    60.4  966.22   57.86 1000.48   60.65 1071.54    59.2
  1091.4   60.46 2996.14   59.97 3786.26   58.03 4289.58   54.34 4334.34   56.74
 4527.28   54.86 4764.16   55.99  4934.5    52.9  4945.5    47.8  4962.5    46.4
  4966.5    37.5  4979.5    35.6  4992.5    37.5  4999.5    44.4  5019.5      51
  5054.5    52.2  5066.5    55.9  5086.5    52.7 5327.28   55.09  5479.2   54.38
  5558.4    56.3 5947.98   56.86  6358.8   57.21 7884.02    59.8 8591.38   59.03
#Mann= 6 ,-1 , 0
 -523.82    .068       0  4934.5     .04       0  5054.5    .118       0
 5947.98    .068       0  6358.8    .118       0 7850.44    .068       0
#Block Obstruct= 2 , 0
         1003.58   60.58 7882.93           59.78
Bank Sta=4934.5,5054.5
XS Rating Curve= 0
Exp/Cntr=.3,.1

Type RM Length L Ch R = 1 ,169266.8,895.8,910.63,828.63
XS GIS Cut Line= 6
     3240912.214    13927914.492     3238587.351    13925987.194
     3237432.691    13924359.461     3237312.899    13924119.878
     3235917.046    13922322.232      3234844.17    13921159.052
#Sta/Elev= 30
 -160.62   60.89 1464.95   59.95 1476.92    59.9 1498.22   55.66 1530.18   60.55
 1552.23   60.65 1610.92   58.99 1636.71    60.8 3190.36   59.67 4010.88   54.78
 4607.19   54.19 4704.18   52.14 4734.97   48.06 4788.21   52.45 4853.11   52.93
    4886   60.64 4898.73   60.46  4933.5    54.5  4958.5    51.8  4979.5    43.6
  4984.5    38.5  4999.5    37.9  5009.5      39  5015.5    44.4  5041.5    51.9
 5122.94   55.42 6163.42   57.08 6199.67   55.58  7146.6   59.12 8981.31   58.31
#Mann= 6 ,-1 , 0
 -160.62    .068       0  4684.6    .118       0  4933.5     .04       0
 5122.94    .118       0 6695.83    .118       0 8158.54    .068       0
#XS Ineff= 1 ,-1
 4545.45 4909.09   53.39
Permanent Ineff=
       F
#Block Obstruct= 2 , 0
          1632.9   60.46 8814.52           59.61
Bank Sta=4933.5,5122.94
XS Rating Curve= 0
Exp/Cntr=.3,.1

Type RM Length L Ch R = 1 ,168356.2,1176.65,1073.85,1093.04
XS GIS Cut Line= 6
      3241457.39    13927499.684      3239245.88     13925561.59
     3238297.274    13923942.795     3238238.033    13923875.597
     3238039.202    13923690.561     3235507.863    13920993.129
#Sta/Elev= 30
   46.51   61.59 1794.12   60.49 1815.38   55.93  1848.3   61.28 1867.76   61.51
 1890.12   59.01 3232.08   59.14  4302.7   55.37 4354.86   53.15 4373.32   54.87
 4964.47    53.8 4983.48    45.5 4992.49      44 4997.49    37.7  5013.5    37.2
 5025.51    38.1 5028.51      42 5055.53      52 5082.55    53.3 5107.57    56.9
 5127.59    52.7 5177.63    51.5 5281.68    53.5 6311.38   56.89 6440.56   55.23
 6586.74    57.3 7801.86   58.96 8450.76   56.83 8552.34    59.1 8923.72   58.22
#Mann= 4 ,-1 , 0
   46.51    .068       0 4964.47     .04       0 5082.55    .118       0
 8450.76    .068       0
#Block Obstruct= 2 , 0
         1866.81   61.38 8570.94           59.39
Bank Sta=4964.47,5082.55
XS Rating Curve= 0
Exp/Cntr=.3,.1