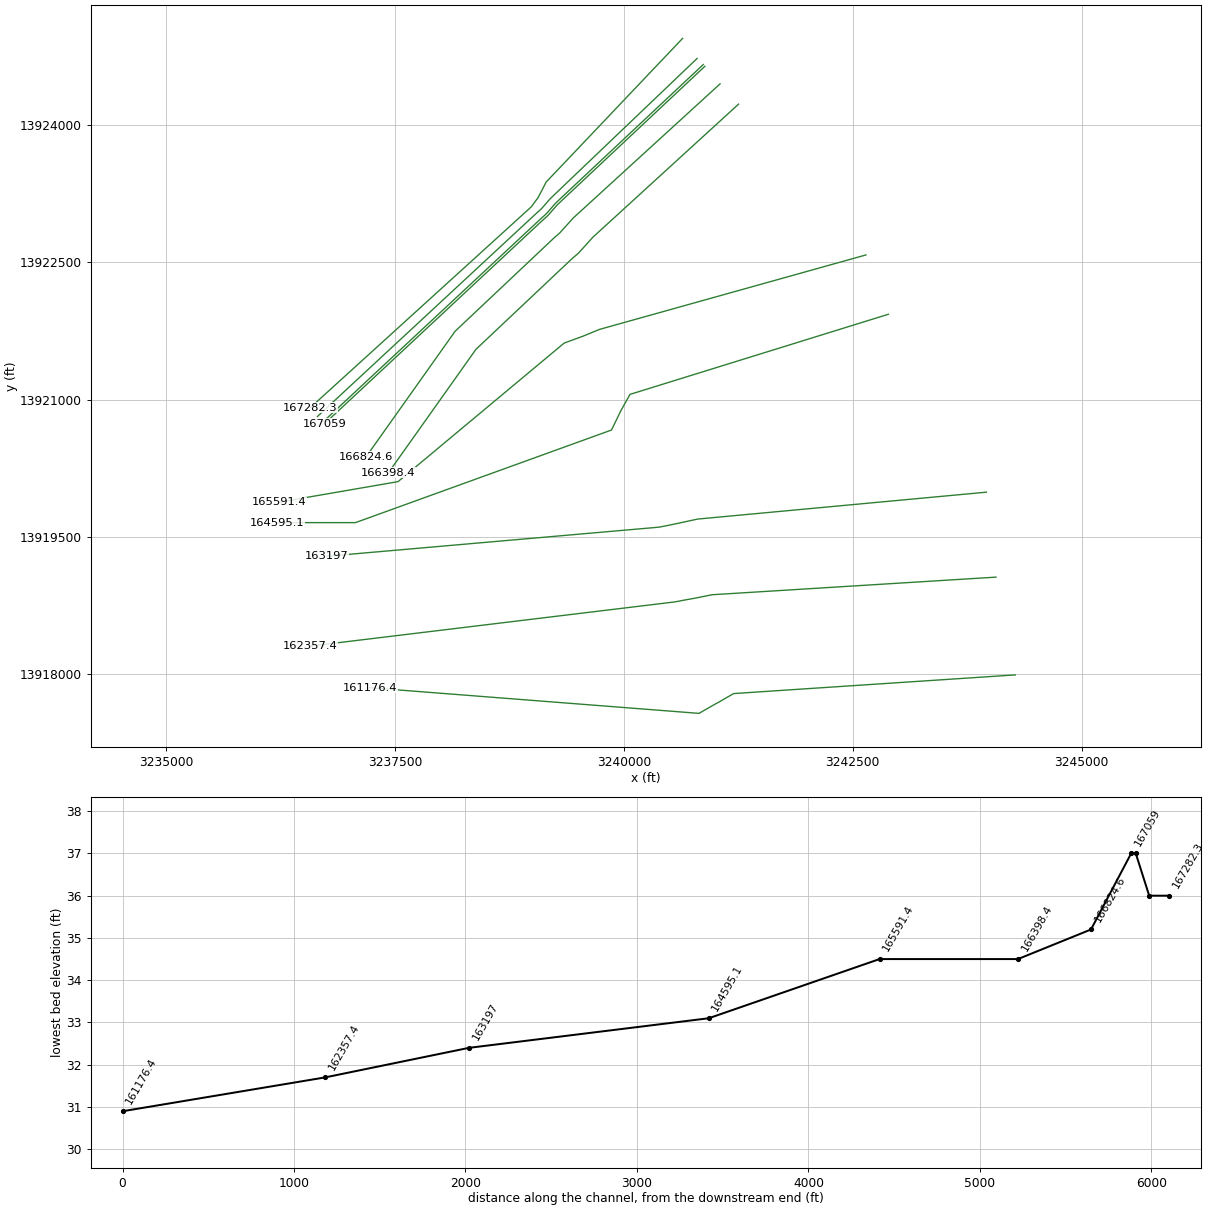
HEC-RAS study Q100-00-00.prj: Q100-00-00

--- Q100-00-00.g01 (geometry) --- (continued)

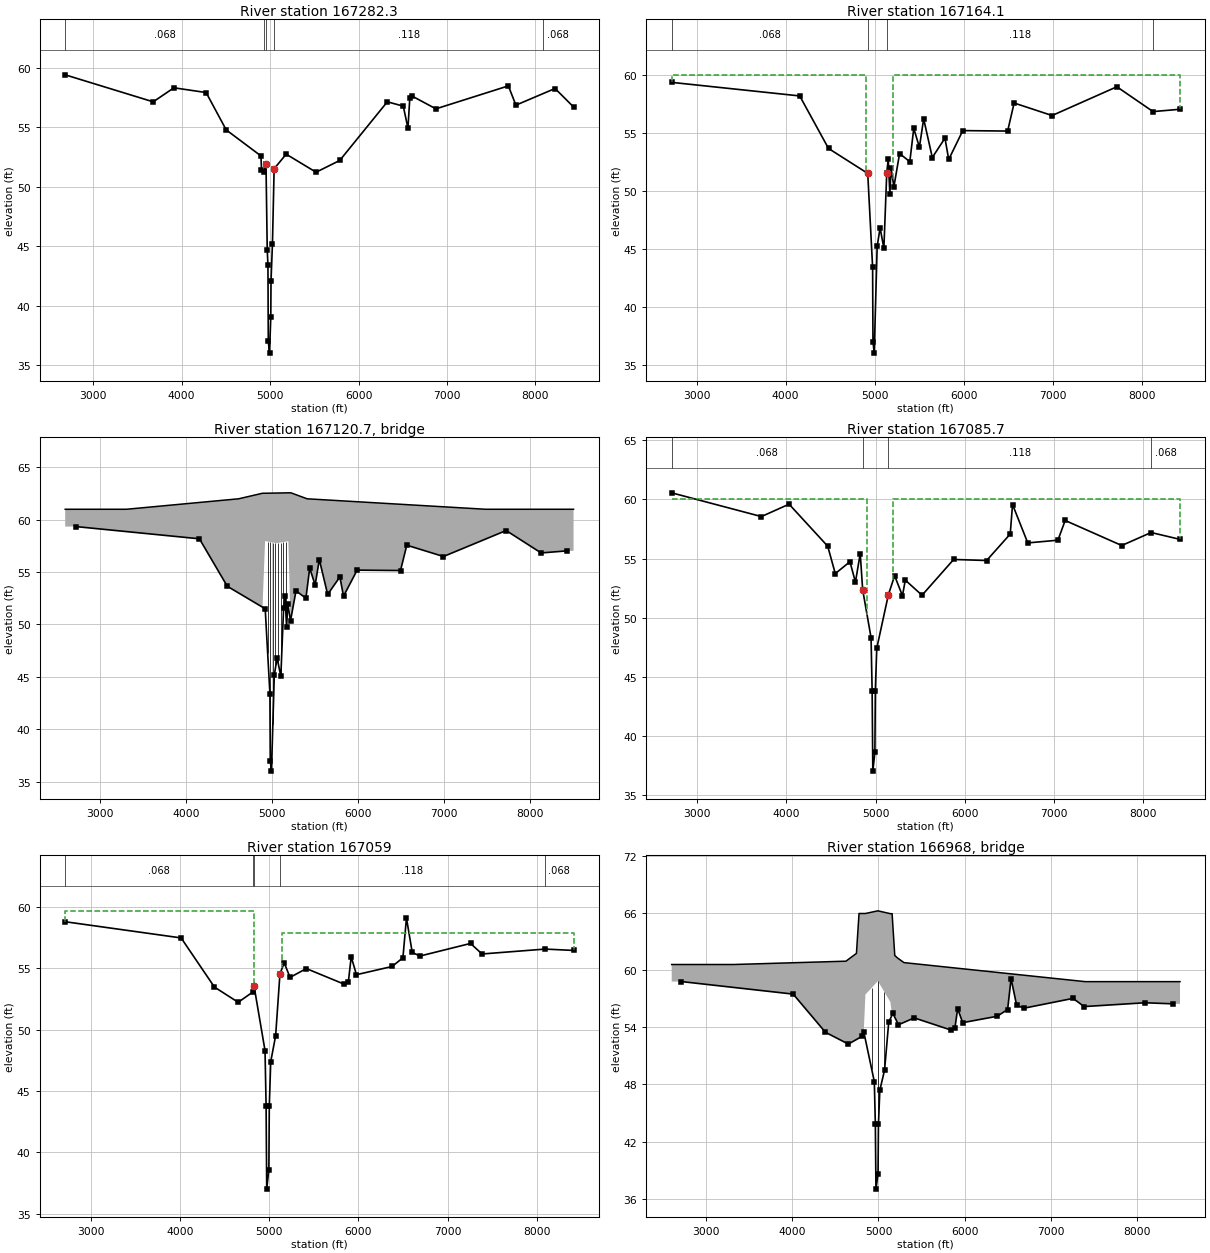
Type RM Length L Ch R = 1 ,167282.3,194.91,118.19,94.85
XS GIS Cut Line= 6
     3240642.373    13924951.472     3239150.973    13923378.723
      3239104.03    13923286.886     3239060.839    13923205.655
     3238988.275    13923107.559     3236574.918    13920911.133
#Sta/Elev= 30
 2683.63    59.4 3678.42   57.13 3913.14   58.31 4276.98   57.91 4504.21   54.77
 4897.23   52.58    4903    51.4    4929    51.2    4954    51.9    4968    44.7
    4976    43.4    4980      37    4994      36    5008      39    5011    42.1
    5027    45.2    5046    51.5 5182.05   52.73 5520.12   51.21 5787.84    52.2
 6325.85   57.13 6506.07   56.77 6559.16   54.91  6580.4   57.49  6606.7   57.61
 6875.29   56.54 7694.54   58.47 7779.77   56.85 8222.66   58.25 8431.45    56.7
#Mann= 5 ,-1 , 0
 2683.63    .068       0    4929    .118       0    4954     .04       0
    5046    .118       0 8086.58    .068       0
#Block Obstruct= 2 , 0
                         7686.01           59.17
Bank Sta=4954,5046
XS Rating Curve= 0
Exp/Cntr=.5,.3

Type RM Length L Ch R = 1 ,167164.1,85.97,78.4,77.71
XS GIS Cut Line= 6
     3240800.679    13924731.831     3239246.871    13923246.322
     3239193.643    13923194.874     3239100.032    13923087.188
     3239033.089    13923026.598     3236652.741    13920814.333
#Sta/Elev= 30
 2720.32   59.35 4157.72   58.18 4480.98   53.65 4921.28    51.5    4976    43.4
    4980      37    4994      36    5027    45.2    5060    46.8 5102.62   45.04
 5134.72   51.55 5151.34   52.73 5169.68   49.73 5183.18   51.95 5215.02   50.35
  5278.7   53.21 5393.72   52.51 5437.92   55.38 5501.18   53.76 5549.12    56.2
 5646.16   52.87 5788.16   54.54 5830.26    52.7 5988.28   55.19 6491.82   55.15
 6564.56   57.57 6990.66   56.49    7718   58.97 8123.98   56.83 8426.64   57.03
#Mann= 4 ,-1 , 0
 2720.32    .068       0 4921.28     .04       0 5134.72    .118       0
 8123.98    .068       0
#XS Ineff= 2 , 0
       0    4905      60    5202       0      60
Permanent Ineff=
       F       F
#Block Obstruct= 2 , 0
                         7718.09           58.96
Bank Sta=4921.28,5134.72
XS Rating Curve= 0
Exp/Cntr=.5,.3

Type RM Length L Ch R = 3 ,167120.7,,,
Node Photo=G:\C2001-041_Harris_County_FEMA\3-Cedar_Bayou\Cedar_Bayou\Survey _info\1101's\1101S30P1.jpg
BEGIN DESCRIPTION:
Southern Pacific RR (Just North of HWY 90)
END DESCRIPTION:
Bridge Culvert--1,0,-1,-1, 0
Deck Dist Width WeirC Skew NumUp NumDn MinLoCord MaxHiCord MaxSubmerge Is_Ogee
43.5,20,2.6,0, 11, 11, , , .95, 0, 0,0,,
    2600    3310    4613    4890    4920    5055    5190    5220    5408    7482
    8500
      61      61      62   62.53   62.53   62.55   62.57   62.57      62      61
      61
       0       0       0       0   57.96   57.76   57.95       0       0       0
       0
    2600    3310    4613    4890    4920    5055    5190    5220    5408    7482
    8500
      61      61      62   62.53   62.53   62.55   62.57   62.57      62      61
      61
       0       0       0       0   57.96   57.76   57.95       0       0       0
       0
Pier Skew, UpSta & Num, DnSta & Num=  ,4950, 2 ,4950, 2 , 0 , 0 , 0 ,,
    1.37    1.37
       0   62.53
    1.37    1.37
       0   62.53
Pier Skew, UpSta & Num, DnSta & Num=  ,4980, 2 ,4980, 2 , 0 , 0 , 0 ,,
    1.37    1.37
       0   62.54
    1.37    1.37
       0   62.54
Pier Skew, UpSta & Num, DnSta & Num=  ,5010, 2 ,5010, 2 , 0 , 0 , 0 ,,
    1.37    1.37
       0   62.54
    1.37    1.37
       0   62.54
Pier Skew, UpSta & Num, DnSta & Num=  ,5040, 2 ,5040, 2 , 0 , 0 , 0 ,,
    1.37    1.37
       0   62.55
    1.37    1.37
       0   62.55
Pier Skew, UpSta & Num, DnSta & Num=  ,5070, 2 ,5070, 2 , 0 , 0 , 0 ,,
    1.37    1.37
       0   62.55
    1.37    1.37
       0   62.55
Pier Skew, UpSta & Num, DnSta & Num=  ,5100, 2 ,5100, 2 , 0 , 0 , 0 ,,
    1.37    1.37
       0   62.56
    1.37    1.37
       0   62.56
Pier Skew, UpSta & Num, DnSta & Num=  ,5130, 2 ,5130, 2 , 0 , 0 , 0 ,,
    1.37    1.37
       0   62.56
    1.37    1.37
       0   62.56
Pier Skew, UpSta & Num, DnSta & Num=  ,5160, 2 ,5160, 2 , 0 , 0 , 0 ,,
    1.37    1.37
       0   62.57
    1.37    1.37
       0   62.57
BR Coef=-1 , 1 , 1 ,.9, 0 ,,,.8,0,1.2,0,
WSPro=,,,, 1 ,,,, 0 ,,,, 0 ,,,,-1 ,-1 ,-1 , 0 , 0 , 0 , 0 , 0
BC Design=,, 0 ,, 0 ,,,,,,
BC HTab HWMax=59.69

Type RM Length L Ch R = 1 ,167085.7,28.85,26.73,26.12
XS GIS Cut Line= 6
     3240867.067    13924664.386     3239300.152     13923191.69
     3239248.637    13923141.898     3239154.444    13923033.542
     3239085.344    13922970.999     3236713.469    13920755.231
#Sta/Elev= 30
 2712.46   60.56  3719.6   58.55 4029.94    59.6 4463.74   56.04 4548.48   53.72
 4713.22   54.73  4774.6      53 4828.56   55.42 4855.78   52.36    4950    48.3
    4962    43.8  4969.8      37    4993    38.6    4998    43.8    5014    47.4
  5144.8   51.94 5214.44   53.54 5302.34   51.85 5334.26   53.17 5522.06   51.89
 5877.24   54.92 6246.72   54.83  6511.8   57.07 6537.84   59.57 6708.62   56.32
 7047.28   56.55 7128.34   58.22 7763.32    56.1 8092.92    57.2 8417.06   56.62
#Mann= 4 ,-1 , 0
 2712.46    .068       0 4855.78     .04       0  5144.8    .118       0
 8092.92    .068       0
#XS Ineff= 2 , 0
       0    4905      60    5200       0      60
Permanent Ineff=
       F       F
#Block Obstruct= 2 , 0
                         6538.62           59.63
Bank Sta=4855.78,5144.8
XS Rating Curve= 0
Exp/Cntr=.5,.3

Type RM Length L Ch R = 1 ,167059  ,257.85,234.44,258.33
XS GIS Cut Line= 6
     3240884.873    13924645.441     3239318.091    13923172.869
     3239267.518    13923123.988     3239173.046     13923015.31
     3239102.943     13922951.86     3236731.218    13920736.232
#Sta/Elev= 30
 2709.56   58.81 4010.32   57.49 4384.44   53.48 4650.72   52.24  4811.5   53.06
 4829.42   53.54    4952    48.3    4964    43.8    4971      37    4995    38.6
    5000    43.8    5016    47.4    5071    49.5 5119.42   54.56 5167.42   55.46
 5232.66   54.27 5415.46   54.99    5843   53.71 5886.94   53.89 5919.26   55.95
 5977.94   54.49 6377.84   55.16 6499.34   55.87 6539.32   59.11 6604.08   56.31
 6689.72   56.01 7258.34   57.04 7387.46   56.18 8095.12   56.58 8414.26   56.47
#Mann= 5 ,-1 , 0
 2709.56    .068       0  4811.5    .118       0 4829.42     .03       0
 5119.42    .118       0 8095.12    .068       0
#XS Ineff= 2 , 0
       0    4833    59.7    5147       0    57.9
Permanent Ineff=
       F       F
#Block Obstruct= 2 , 0
                         6542.49           59.03
Bank Sta=4829.42,5119.42
XS Rating Curve= 0
Exp/Cntr=.5,.3

Type RM Length L Ch R = 3 ,166968  ,,,
BEGIN DESCRIPTION:
US HWY 90 (Beaumont Highway)
END DESCRIPTION:
Bridge Culvert--1,0,-1,-1, 0
Deck Dist Width WeirC Skew NumUp NumDn MinLoCord MaxHiCord MaxSubmerge Is_Ogee
24,137,2.6,0, 14, 14, , , .95, 0, 0,0,,
    2600    3320  4622.9  4744.5  4774.5  4848.5  4993.5  5138.5  5158.5  5189.5
  5219.5    5296    7400    8500
    60.6    60.6   60.95   61.77   65.96   65.96   66.24   65.94   65.94   61.55
    61.3    60.8    58.8    58.8
       0       0       0       0       0   57.44   58.86   56.66       0       0
       0       0       0       0
    2600    3320  4622.9  4744.5  4774.5  4848.5  4993.5  5138.5  5158.5  5189.5
  5219.5    5296    7400    8500
    60.6    60.6   60.95   61.77   65.96   65.96   66.24   65.94   65.94   61.55
    61.3    60.8    58.8    58.8
       0       0       0       0       0   57.44   58.86   56.66       0       0
       0       0       0       0
Pier Skew, UpSta & Num, DnSta & Num=  ,4921, 2 ,4921, 2 , 0 , 0 , 0 ,,
    2.61    2.61
       0   62.12
    2.61    2.61
       0   62.12
Pier Skew, UpSta & Num, DnSta & Num=  ,4993.5, 2 ,4993.5, 2 , 0 , 0 , 0 ,,
    2.61    2.61
       0   62.25
    2.61    2.61
       0   62.25
Pier Skew, UpSta & Num, DnSta & Num=  ,5066, 2 ,5066, 2 , 0 , 0 , 0 ,,
    2.61    2.61
       0   62.38
    2.61    2.61
       0   62.38
BR Coef=-1 , 1 , 1 ,.9, 0 ,,,.8,0,1.2,0,
WSPro=,,,, 1 ,,,, 0 ,,,, 0 ,,,,-1 ,-1 ,-1 , 0 , 0 , 0 , 0 , 0
BC Design=,, 0 ,, 0 ,,,,,,
BC HTab HWMax=59.21

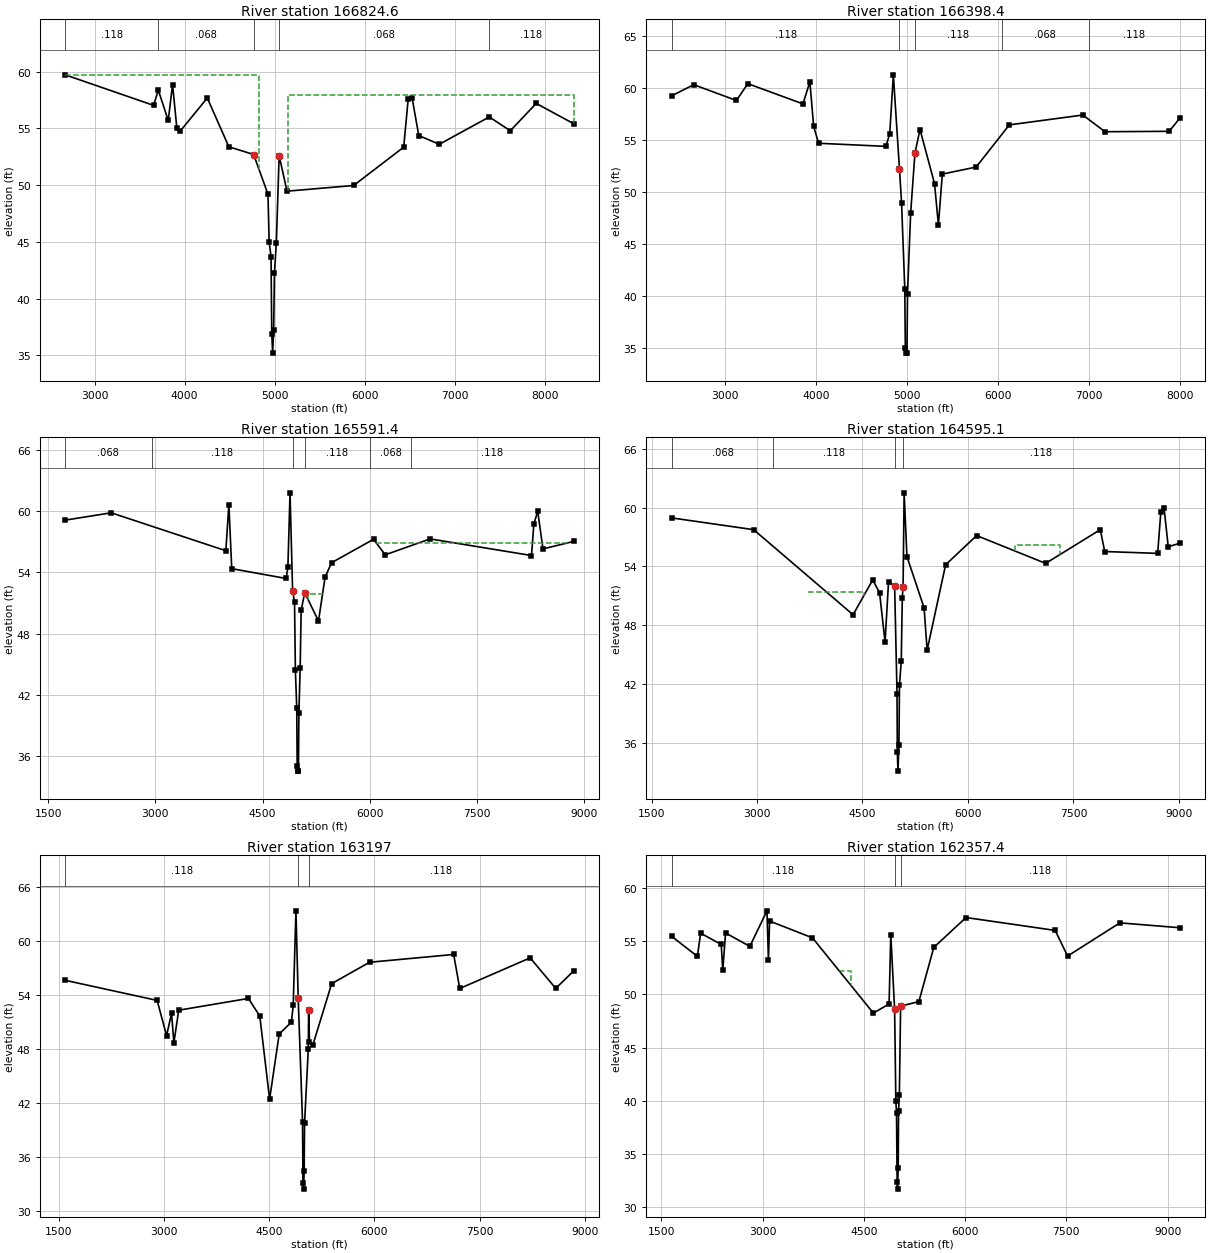
Type RM Length L Ch R = 1 ,166824.6,330.73,426.12,352.13
XS GIS Cut Line= 6
     3241051.009     13924453.35     3239446.139    13922985.065
     3239295.244    13922817.303     3239241.262    13922771.651
     3238157.121    13921747.266     3237183.955    13920372.883
#Sta/Elev= 30
 2673.36   59.72    3655   57.03 3707.74   58.37 3817.88    55.7  3866.1   58.86
  3913.1   55.06 3947.92   54.73 4251.88   57.68  4491.3   53.38 4766.74    52.7
    4926    49.2    4939      45    4960    43.7    4968    36.9    4978    35.2
    4989    37.2    4998    42.3    5019    44.9    5050    52.6 5137.44   49.47
 5878.24   49.97  6433.9   53.35  6483.9   57.61 6527.16   57.69 6601.22   54.37
 6829.08    53.6  7384.8   56.01 7618.04   54.79 7905.84    57.2 8320.54   55.42
#Mann= 5 ,-1 , 0
 2673.36    .118       0 3707.74    .068       0 4766.74     .03       0
    5050    .068       0  7384.8    .118       0
#XS Ineff= 2 , 0
       0    4830    59.7    5150       0    57.9
Permanent Ineff=
       F       F
#Block Obstruct= 2 , 0
                         6524.82           57.64
Bank Sta=4766.74,5050
XS Rating Curve= 0
Exp/Cntr=.5,.3

Type RM Length L Ch R = 1 ,166398.4,1185.96,807.02,706.74
XS GIS Cut Line= 6
     3241253.513    13924232.008     3239663.298    13922777.131
     3239502.531    13922599.707     3239441.291    13922547.918
     3238384.773    13921549.633     3237428.792     13920199.52
#Sta/Elev= 30
 2412.34   59.28 2654.67   60.35  3123.5   58.83 3248.68   60.45 3854.37    58.5
 3930.29   60.63 3971.41   56.35 4025.62   54.71 4764.48   54.41    4807    55.6
    4847    61.3  4914.5    52.2    4937      49  4972.5    40.7  4978.5      35
  4988.5    34.5  4996.5    34.5  5002.5    40.2    5037      48  5084.5    53.8
 5139.98   56.03 5299.41   50.82 5341.88   46.84 5384.78   51.74 5756.23   52.42
 6120.96   56.48 6927.92   57.43 7171.83   55.82 7876.46   55.86 7995.21   57.15
#Mann= 5 ,-1 , 0
 2412.34    .118       0  4914.5     .04       0  5084.5    .118       0
 6041.21    .068       0  6990.3    .118       0
#XS Ineff= 2 ,-1
 3958.04 4839.16   55.97 5181.82 5951.05   53.71
Permanent Ineff=
       F       F
#Block Obstruct= 2 , 0
                         6927.29           57.45
Bank Sta=4914.5,5084.5
XS Rating Curve= 0
Exp/Cntr=.3,.1

Type RM Length L Ch R = 1 ,165591.4,759.81,996.34,982.78
XS GIS Cut Line= 6
     3242644.553    13922582.059     3239734.602    13921767.603
      3239552.32    13921692.635     3239347.994     13921617.64
     3237533.246    13920101.998      3236236.99    13919877.833
#Sta/Elev= 30
  1737.1   59.12 2381.57   59.84 3985.98   56.12  4028.5   60.65  4068.5   54.36
  4829.5    53.4  4854.5    54.5  4884.5    61.8  4920.5    52.2  4947.5    51.1
  4959.5    44.4  4978.5    40.7  4984.5      35  4994.5    34.5  5002.5    34.5
  5008.5    40.2  5026.5    44.6  5040.5    50.3  5090.5      52 5282.92   49.23
  5375.4   53.54 5467.19   54.95 6053.77   57.24 6217.51   55.72 6845.59   57.28
 8264.95   55.65 8297.56   58.71 8351.99      60 8425.61    56.3 8853.56   57.03
#Mann= 6 ,-1 , 0
  1737.1    .068       0  2946.9    .118       0  4920.5     .04       0
  5090.5    .118       0 6006.98    .068       0  6576.3    .118       0
#XS Ineff= 2 ,-1
 6101.31 8799.76   56.87 5139.86 5391.61   51.86
Permanent Ineff=
       F       F
#Block Obstruct= 2 , 0
                         8370.68           56.94
Bank Sta=4920.5,5090.5
XS Rating Curve= 0
Exp/Cntr=.3,.1

Type RM Length L Ch R = 1 ,164595.1,1610.02,1398.1,1082.45
XS GIS Cut Line= 6
     3242890.041    13921933.268     3240066.924    13921056.523
     3239968.278    13920879.118     3239864.983    13920666.753
     3237068.458    13919653.732     3236209.249    13919653.732
#Sta/Elev= 30
 1786.79   58.94 2952.53   57.74 4366.34   49.06 4646.05   52.62 4742.92   51.31
 4821.36   46.28 4870.52   52.39  4957.5      52  4991.5      41  4995.5    35.1
  5004.5    33.1  5018.5    35.8  5026.5    41.9  5051.5    44.3  5066.5    50.8
  5077.5    51.9  5092.5    61.5  5132.5      55 5376.42   49.76 5419.65   45.45
 5682.53   54.16 6123.66   57.14 7104.86    54.3 7881.87   57.74 7945.19   55.51
 8698.21   55.32 8743.21   59.58 8788.21      60 8848.21      56 9015.62   56.36
#Mann= 4 ,-1 , 0
 1786.79    .068       0 3232.56    .118       0  4957.5     .04       0
  5077.5    .118       0
#XS Ineff= 4 ,-1
 6674.61 7307.51   56.14 5132.87 5709.79   51.86 4650.35 4923.08   51.76
 3724.67 4518.47   51.42
Permanent Ineff=
       F       F       F       F
#Block Obstruct= 2 , 0
                         7307.51           56.29
Bank Sta=4957.5,5077.5
XS Rating Curve= 0
Exp/Cntr=.3,.1

Type RM Length L Ch R = 1 ,163197  ,873.06,839.6,849.77
XS GIS Cut Line= 6
     3243959.669    13919986.895     3240807.691    13919692.795
     3240645.655    13919657.783     3240499.911    13919626.804
     3240385.816    13919604.253      3236752.83      13919285.5
#Sta/Elev= 30
 1595.47   55.66 2905.58   53.42 3040.05    49.5 3110.72   51.99  3144.3   48.71
 3212.83   52.33 4206.46   53.64 4368.35   51.67  4508.1   42.41 4644.94   49.68
  4819.5      51  4844.5    52.9  4883.5    63.4  4915.5    53.7  4977.5    39.9
  4983.5    33.1  4992.5    32.4  5000.5    34.4  5006.5    39.8  5059.5      48
  5064.5    52.4  5076.5    48.8  5126.5    48.5 5392.57   55.29 5932.65   57.67
 7131.09   58.54 7217.78   54.75 8220.98   58.16 8585.41   54.76 8839.16   56.69
#Mann= 3 ,-1 , 0
 1595.47    .118       0  4915.5     .04       0  5064.5    .118       0
#XS Ineff= 3 ,-1
  2536.6 4090.82   53.12  4300.7 4869.46   52.17 5065.41 5335.81   51.94
Permanent Ineff=
       F       F       F
#Block Obstruct= 2 , 0
                          7073.9           56.07
Bank Sta=4915.5,5064.5
XS Rating Curve= 0
Exp/Cntr=.3,.1

Type RM Length L Ch R = 1 ,162357.4,1105.29,1180.95,1143.67
XS GIS Cut Line= 6
     3244064.879    13919057.546     3240961.203    13918864.662
     3240771.691    13918826.087     3240684.043    13918810.632
     3240557.691    13918786.545     3236577.481    13918303.546
#Sta/Elev= 30
 1652.88   55.45 2034.06   53.57 2081.45   55.75 2386.99   54.69 2409.78   52.26
 2451.38   55.77 2811.06   54.51 3064.42   57.85 3086.09   53.22 3103.27   56.89
    3739   55.31 4640.47   48.24  4873.5    49.1  4898.5    55.6  4955.5    48.6
  4973.5      40  4983.5    38.9  4992.5    32.4  4998.5    31.7  5008.5    33.7
  5013.5      39  5025.5    40.5  5044.5    48.9  5314.8   49.32 5535.75   54.41
 6012.89   57.22 7334.14   56.01 7517.82    53.6 8292.49   56.72 9182.98   56.26
#Mann= 3 ,-1 , 0
 1652.88    .118       0  4955.5     .04       0  5044.5    .118       0
#XS Ineff= 2 ,-1
 7127.53 8045.29   54.71 4137.34 4312.87   52.21
Permanent Ineff=
       F       F
#Block Obstruct= 2 , 0
          3146.6   55.52
Bank Sta=4955.5,5044.5
XS Rating Curve= 0
Exp/Cntr=.3,.1

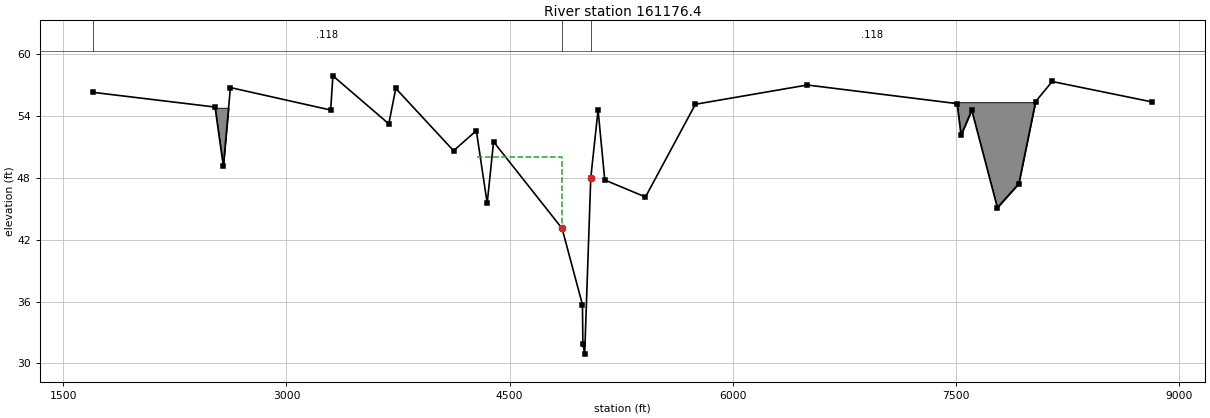
Type RM Length L Ch R = 1 ,161176.4,1229.17,862.97,581.03
XS GIS Cut Line= 6
     3244275.297    13917987.918     3241199.295    13917783.752
      3241046.78     13917695.55     3240966.315    13917650.948
     3240820.924    13917567.081     3237226.272    13917847.639
#Sta/Elev= 30
 1697.85   56.31 2519.76   54.88 2575.64   49.13 2623.18   56.77 3297.23   54.59
 3312.26   57.91 3688.08   53.25 3734.94   56.69 4123.66   50.64 4276.63   52.59
 4349.54   45.54 4392.58   51.51    4853    43.1    4990    35.7    4993    31.9
    5005    30.9    5046      48    5095    54.6    5140    47.8 5413.74   46.15
 5749.45   55.15 6501.56   57.02 7509.12   55.21 7535.17   52.15 7607.21   54.58
 7779.55   45.12 7923.86   47.44 8036.66   55.41 8147.92   57.36 8822.23   55.37
#Mann= 3 ,-1 , 0
 1697.85    .118       0    4853     .04       0    5046    .118       0
#XS Ineff= 1 ,-1
 4282.19 4853.78   50.02
Permanent Ineff=
       F
#Block Obstruct= 2 ,-1
 2090.91 2696.97   54.81  7478.7 8038.25   55.35
Bank Sta=4853,5046
XS Rating Curve= 0
Exp/Cntr=.3,.1