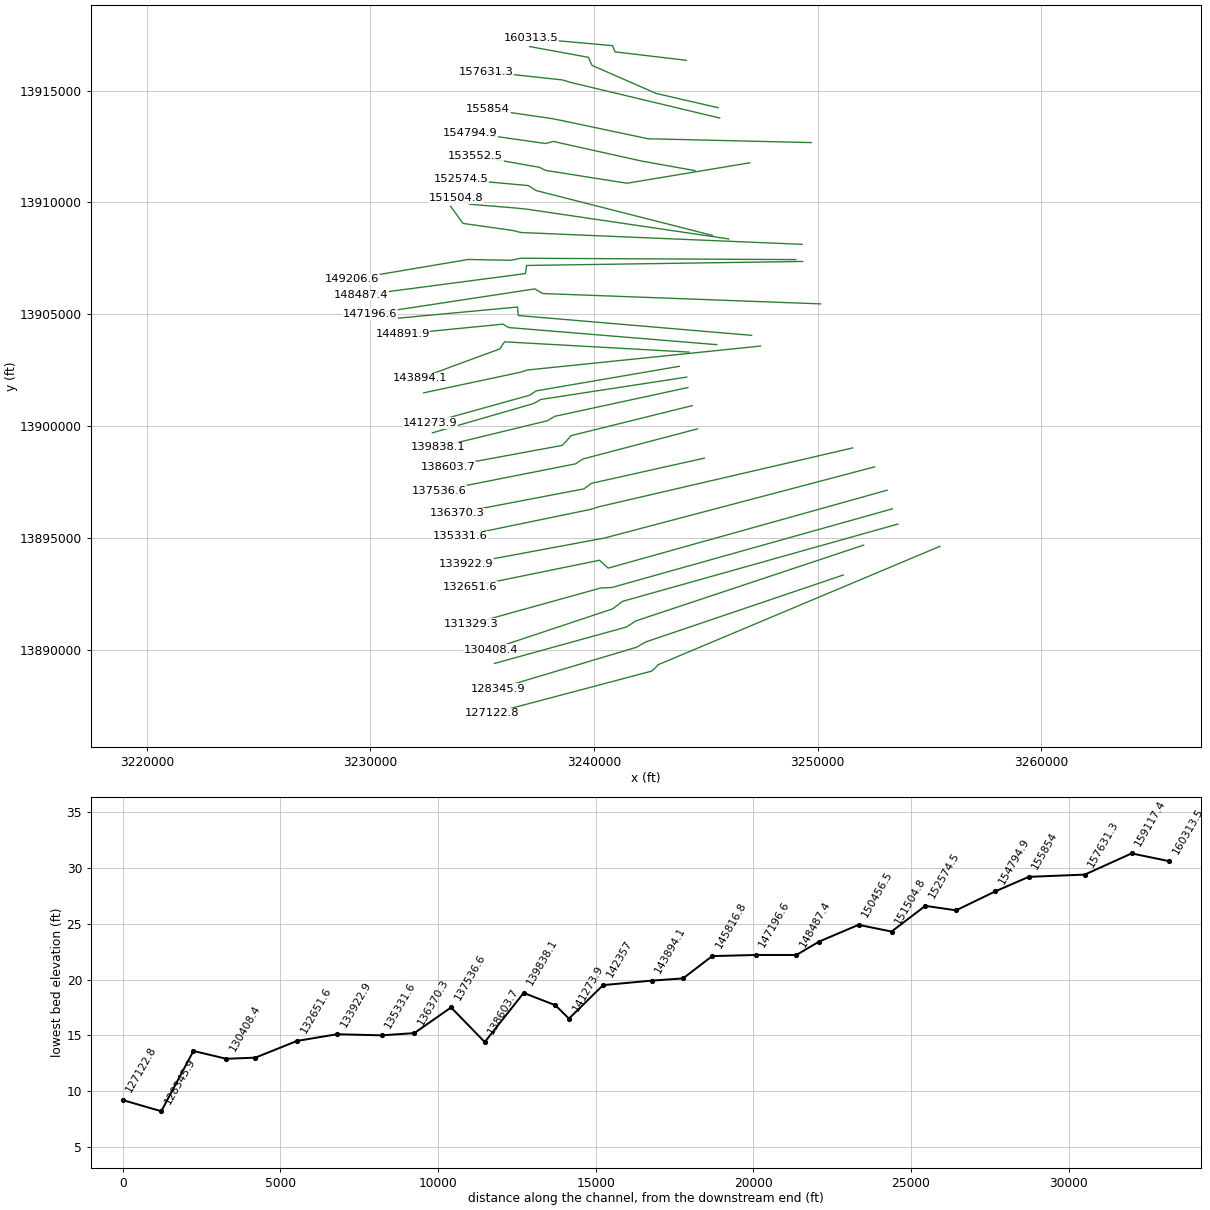
HEC-RAS study Q100-00-00.prj: Q100-00-00

--- Q100-00-00.g01 (geometry) --- (continued)

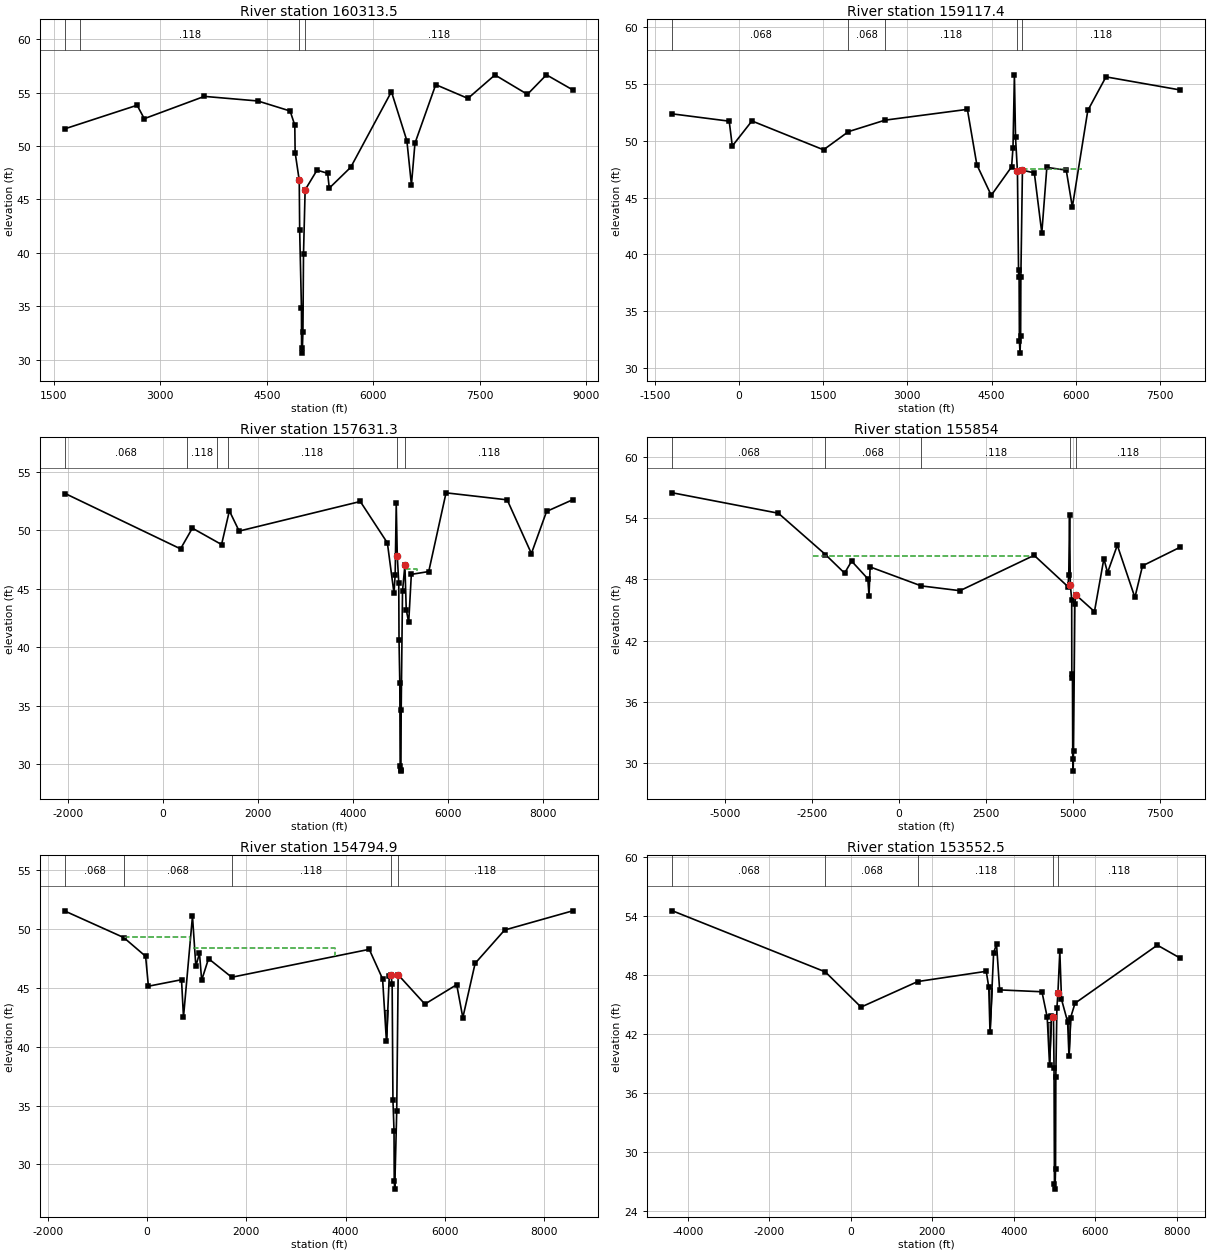
Type RM Length L Ch R = 1 ,160313.5,1274.29,1196.04,1039.87
XS GIS Cut Line= 6
     3244117.483    13916357.173     3240937.899    13916734.461
     3240898.926    13916824.487     3240867.833    13916901.443
     3240828.524    13917010.503     3237191.203    13917339.127
#Sta/Elev= 30
 1660.46   51.63 2673.91   53.83 2774.97   52.57 3621.26   54.66 4375.05   54.23
 4830.18   53.29 4895.87   51.95  4900.5    49.4  4958.5    46.8  4964.5    42.1
  4989.5    34.8  4991.5    31.1  5000.5    30.6  5010.5    32.6  5018.5    39.9
  5041.5    45.9    5209   47.75 5358.68   47.45 5381.56   46.06 5684.36   48.02
 6257.37    55.1    6475    50.5 6539.07   46.37 6588.91   50.27 6881.48   55.76
 7335.25   54.47 7715.89   56.67 8173.24   54.85 8441.36   56.68 8811.51   55.27
#Mann= 4 ,-1 , 0
 1660.46    .068       0 1874.99    .118       0  4958.5     .04       0
  5041.5    .118       0
#XS Ineff= 2 ,-1
 6195.43 6977.25   53.81 2678.32  3601.4   53.76
Permanent Ineff=
       F       F
#Block Obstruct= 2 , 0
            2669   53.76
Bank Sta=4958.5,5041.5
XS Rating Curve= 0
Exp/Cntr=.3,.1

Type RM Length L Ch R = 1 ,159117.4,1150.69,1486.15,1572.69
XS GIS Cut Line= 6
     3245546.208     13914237.69     3242782.761    13914873.073
      3239909.11     13916129.22     3239800.681    13916363.874
     3239750.399     13916489.67     3237121.063    13916970.894
#Sta/Elev= 30
 -1182.5   52.36 -172.54   51.72 -117.56   49.53  232.18   51.74 1507.12    49.2
 1951.58    50.8 2602.96   51.81 4069.02   52.76 4237.76   47.88 4494.04   45.19
  4856.5    47.7  4881.5    49.4  4906.5    55.8  4926.5    50.3  4960.5    47.3
  4981.5      38  4989.5    38.6  4995.5    32.4  5006.5    31.3  5017.5    32.8
  5021.5      38  5049.5    47.4  5261.3   47.17 5394.42   41.88 5484.12   47.65
 5829.64   47.41 5938.16   44.16  6213.6   52.66  6537.3   55.62 7856.24   54.47
#Mann= 5 ,-1 , 0
 -1182.5    .068       0 1951.58    .068       0 2602.96    .118       0
  4960.5     .04       0  5049.5    .118       0
#XS Ineff= 2 ,-1
 4130.54 4911.42    47.6 5074.59 6111.89   47.51
Permanent Ineff=
       F       F
#Block Obstruct= 2 , 0
         3547.45   53.84 5224.82           44.88
Bank Sta=4960.5,5049.5
XS Rating Curve= 0
Exp/Cntr=.3,.1

Type RM Length L Ch R = 1 ,157631.3,1760.53,1777.24,1794.13
XS GIS Cut Line= 6
     3245617.318    13913775.476     3238922.274    13915375.086
     3238797.145    13915415.342     3238722.011    13915439.754
     3238583.733    13915479.253     3235164.165    13915849.514
#Sta/Elev= 30
-2052.35   53.13  375.05    48.4  623.43   50.17 1237.83   48.77 1402.17   51.65
 1607.39   49.92 4156.34   52.45 4726.01   48.91  4865.5    44.6    4890    46.2
  4912.5    52.3    4934    47.8  4965.5    45.5    4971    40.6  4987.5    36.9
  4994.9    29.8  5002.5    29.4  5010.8    29.5  5016.5    34.6  5044.5    44.8
  5094.5      47    5123    43.2 5174.67   42.11 5229.95   46.22 5596.02   46.46
 5960.15   53.19 7246.48   52.59 7755.74      48 8075.33    51.6 8624.95    52.6
#Mann= 6 ,-1 , 0
-2052.35    .068       0   510.2    .118       0 1150.84    .068       0
 1364.38    .118       0    4934     .04       0  5094.5    .118       0
#XS Ineff= 2 ,-1
 4615.38 4909.09   47.08 5088.58 5349.65   46.64
Permanent Ineff=
       F       F
#Block Obstruct= 2 , 0
         3102.19   52.68  7228.1           52.47
Bank Sta=4934,5094.5
XS Rating Curve= 0
Exp/Cntr=.3,.1

Type RM Length L Ch R = 1 ,155854  ,1001.12,1059.16,1156.04
XS GIS Cut Line= 6
 3249709.812799613912676.6945709     3242412.469     13912848.36
     3238516.024    13913671.961     3238251.673    13913720.268
     3238151.441    13913744.878     3235262.365    13914165.312
#Sta/Elev= 30
-6503.08    56.5-3463.08    54.5-2113.08   50.45 -1561.9   48.62 -1359.6    49.8
  -894.9   48.07 -860.42   46.42 -828.24   49.23  639.76   47.37 1751.22    46.9
    3881   50.37  4850.5    47.3  4875.5    48.4  4898.5    54.3  4919.5    47.5
  4959.5      46  4962.5    38.7  4981.5    38.3  4989.5    30.4  5001.5    29.2
  5011.5    31.2  5050.5    45.6  5076.5    46.5 5612.64   44.85 5883.72   50.04
 5988.86   48.67 6269.18   51.36 6773.72   46.24 6992.98   49.34 8070.28   51.16
#Mann= 5 ,-1 , 0
-6503.08    .068       0-2113.08    .068       0  639.76    .118       0
  4919.5     .04       0  5076.5    .118       0
#XS Ineff= 1 ,-1
-2457.97 3785.18   50.28
Permanent Ineff=
       F
#Block Obstruct= 2 , 0
                         6304.74           51.16
Bank Sta=4919.5,5076.5
XS Rating Curve= 0
Exp/Cntr=.3,.1

Type RM Length L Ch R = 1 ,154794.9,1294.14,1242.34,1090.81
XS GIS Cut Line= 6
 3244515.180222713911422.3509844     3242145.453    13911846.662
     3238172.274    13912729.253     3237951.981    13912667.386
     3237833.733    13912635.503     3234473.295    13913113.219
#Sta/Elev= 30
-1646.47    51.5 -466.47   49.26   -26.4   47.67   29.87   45.13  697.07   45.68
  736.58    42.5  917.78   51.08  985.39   46.84 1059.06   47.92 1102.94   45.64
 1241.24   47.47 1708.36   45.89 4478.25   48.26 4747.23   45.75 4824.57   40.44
 4881.11   45.96  4914.5    46.1  4939.5    45.3  4955.5    35.5  4977.5    32.8
  4981.5    28.6  4991.5    27.9  5031.5    34.5  5060.5    46.1 5599.03   43.61
 6239.95   45.26 6363.32   42.46 6610.84   47.07 7205.12    49.9 8576.49   51.53
#Mann= 5 ,-1 , 0
-1646.47    .068       0 -466.47    .068       0 1708.36    .118       0
  4914.5     .04       0  5060.5    .118       0
#XS Ineff= 4 ,-1
 -448.25  867.69   49.32  935.34 3781.49   48.34 4629.37  4895.1   45.94
 5132.87 6559.44   45.41
Permanent Ineff=
       F       F       F       F
#Block Obstruct= 1 ,-1
 4730.68  4899.3   43.12
Bank Sta=4914.5,5060.5
XS Rating Curve= 0
Exp/Cntr=.3,.1

Type RM Length L Ch R = 1 ,153552.5,1149.56,977.99,966.44
XS GIS Cut Line= 6
 3246957.962360413911771.8855777     3241472.832    13910859.027
     3237838.941    13911432.378     3237674.933    13911507.477
     3237559.435    13911570.149     3234701.248    13912078.661
#Sta/Elev= 30
-4377.32    54.5 -627.32   48.29  248.98   44.71 1641.23   47.31 3321.95   48.35
 3383.33   46.74 3413.76   42.19 3502.88   50.24 3574.15   51.11 3649.85   46.46
  4688.4   46.27 4817.28   43.69  4874.7   38.85    4921    43.8    4971    43.7
    4985    38.5    4995    26.7    5010    26.2    5022    28.2    5029    37.6
    5055    44.6    5080    46.1 5126.95   50.38 5168.21    45.5 5318.15   43.22
 5351.64   39.74 5393.33   43.65 5499.07    45.1  7519.9   51.01 8076.96    49.7
#Mann= 5 ,-1 , 0
-4377.32    .068       0 -627.32    .068       0 1641.23    .118       0
    4971     .04       0    5080    .118       0
#XS Ineff= 2 ,-1
 -289.11 1806.77   46.73 5151.52 6214.45   46.38
Permanent Ineff=
       F       F
#Block Obstruct= 3 ,-1
 3105.39 3555.04   46.67  4754.1 4922.72    43.2 5166.28 8076.96   43.66
Bank Sta=4971,5080
XS Rating Curve= 0
Exp/Cntr=.3,.1

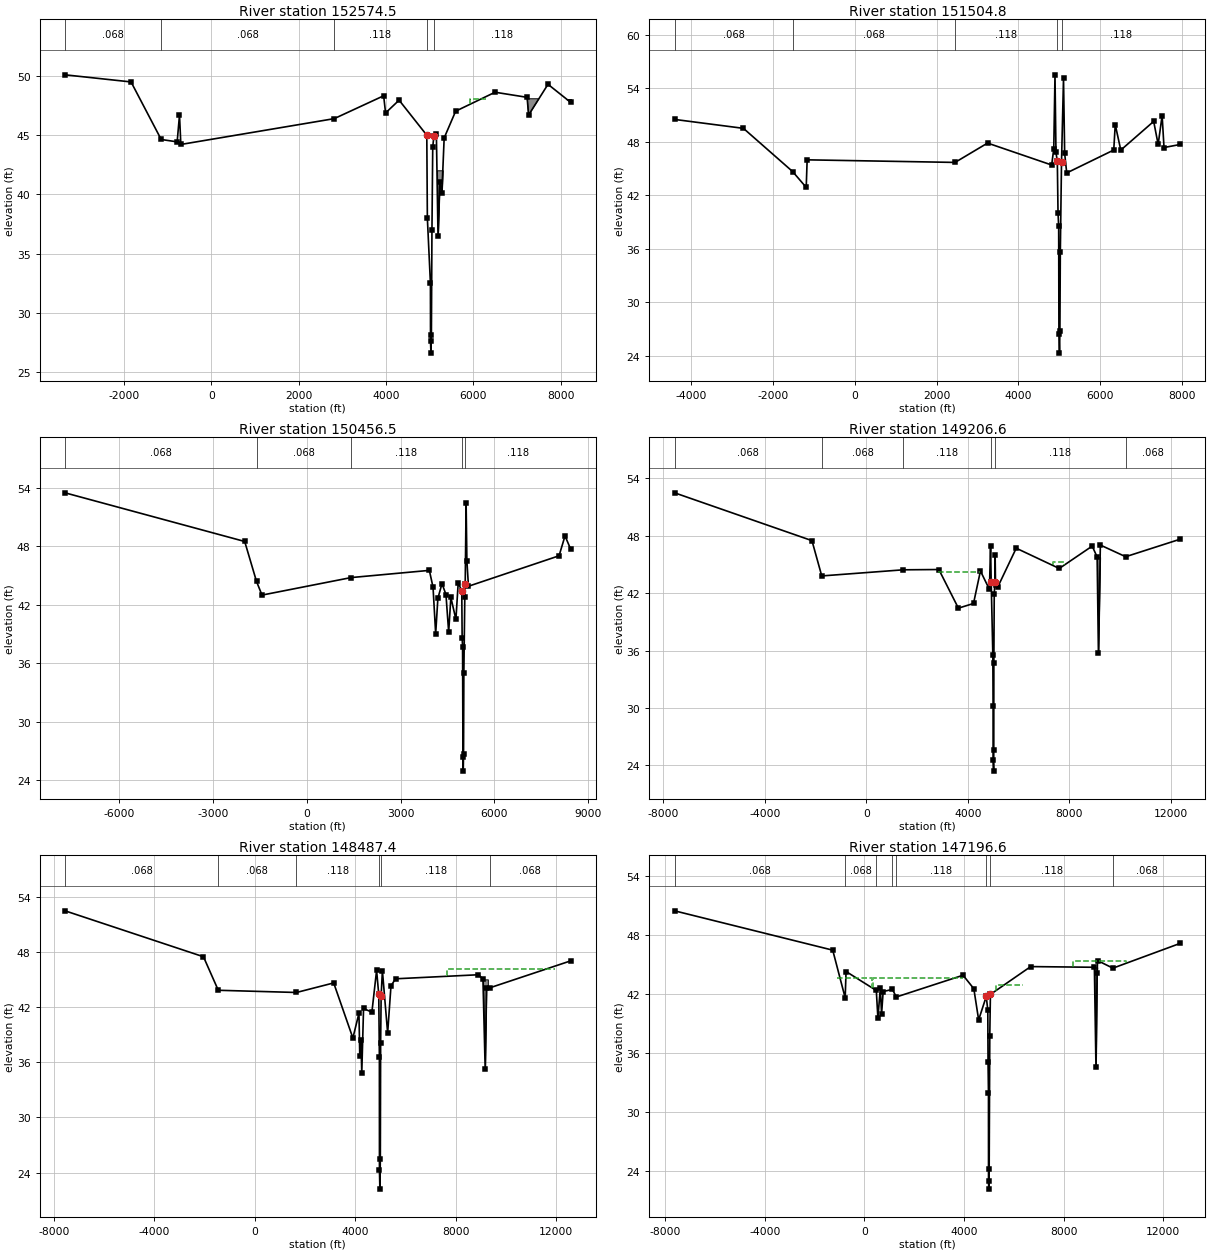
Type RM Length L Ch R = 1 ,152574.5,956.91,1069.75,1114.06
XS GIS Cut Line= 6
 3245293.207826813908525.9042777     3237407.559    13910532.508
     3237290.184    13910608.424     3237176.124    13910682.495
     3237060.886    13910754.957     3234052.458    13911026.567
#Sta/Elev= 30
-3346.41    50.1-1836.41    49.5-1146.41   44.64 -781.16   44.44 -727.59    46.7
 -696.63   44.22 2813.41    46.4 3944.45   48.33 3988.44   46.88 4298.01   47.96
    4932      45    4945      38    5015    32.5    5017    27.6    5027    26.6
    5037    28.1    5050      37    5068      44    5093    44.9 5151.37   45.08
 5189.14   36.45 5228.24   41.07 5276.77   40.12 5329.42   44.77 5592.34   47.03
 6494.58   48.63 7227.96    48.2 7261.82    46.7 7705.43    49.3 8223.12   47.78
#Mann= 5 ,-1 , 0
-3346.41    .068       0-1146.41    .068       0 2813.41    .118       0
    4932     .04       0    5093    .118       0
#XS Ineff= 3 ,-1
 5925.26 6281.29   48.02-2286.07 3570.99   46.12 5121.21  5496.5   44.71
Permanent Ineff=
       F       F       F
#Block Obstruct= 2 ,-1
 5131.15 5344.26   42.04 7206.35 8223.12   48.08
Bank Sta=4932,5093
XS Rating Curve= 0
Exp/Cntr=.3,.1

Type RM Length L Ch R = 1 ,151504.8,1038.46,1048.28,996.99
XS GIS Cut Line= 6
 3246020.896283813908368.8071258     3236969.149    13909703.211
     3236779.983    13909720.396     3236500.399    13909750.086
     3234476.863    13909916.723     3233842.039    13910184.893
#Sta/Elev= 30
-4393.35    50.5-2713.35    49.5-1513.35   44.66-1180.82   42.88-1157.87   45.97
 2452.42   45.68 3245.87   47.85 4810.72   45.39    4862    47.2    4892    55.5
    4916    46.8    4949    45.8    4966      40    4982    38.5    4988    26.5
    5002    24.3    5012    26.8    5022    35.6    5051    45.7    5100    55.1
    5128    46.7    5178    44.5 6326.17   47.07  6362.7   49.92 6497.97   47.06
  7301.1   50.28 7410.21   47.69 7506.96   50.94 7553.22   47.35 7946.86   47.69
#Mann= 5 ,-1 , 0
-4393.35    .068       0-1513.35    .068       0 2452.42    .118       0
    4949     .04       0    5051    .118       0
#XS Ineff= 1 ,-1
-2674.65 3299.12   45.57
Permanent Ineff=
       F
Bank Sta=4949,5051
XS Rating Curve= 0
Exp/Cntr=.3,.1

Type RM Length L Ch R = 1 ,150456.5,1162.05,1249.92,1393.31
XS GIS Cut Line= 6
   3249301.5534713908126.7606858     3236743.103    13908654.696
     3236635.667    13908677.428     3236376.207    13908744.254
     3234140.132     13909062.66     3233579.016    13909834.195
#Sta/Elev= 30
-7726.27    53.5-1984.27    48.5-1606.27   44.39-1431.18   42.99  1415.1   44.79
 3918.15   45.53 4035.95   43.81 4120.41   39.01 4190.88   42.66 4322.83   44.17
 4449.17   43.05  4536.1   39.18 4605.83   42.75 4767.38   40.49 4841.18   44.27
  4954.5    43.4  4966.5    38.6  4980.5    37.7  4992.5    26.4  5001.5    24.9
  5011.5    26.7  5021.5      35  5051.5    42.8  5064.5    44.1  5093.5    52.5
  5118.5    46.5  5168.5    43.9  8064.6   47.03 8254.88   49.07 8433.65   47.73
#Mann= 5 ,-1 , 0
-7726.27    .068       0-1606.27    .068       0  1415.1    .118       0
  4954.5     .04       0  5064.5    .118       0
#XS Ineff= 2 ,-1
-3075.29 2824.67   44.77  3895.1 4881.12   43.81
Permanent Ineff=
       F       F
Bank Sta=4954.5,5064.5
XS Rating Curve= 0
Exp/Cntr=.3,.1

Type RM Length L Ch R = 1 ,149206.6,391.09,719.16,724.51
XS GIS Cut Line= 6
 3249021.207988713907444.3407173     3236713.941    13907505.295
     3236426.587    13907443.965     3236279.388    13907414.381
     3234368.086     13907449.45     3229177.759    13906572.706
#Sta/Elev= 30
-7552.64    52.5-2138.64    47.5-1752.64   43.81 1457.84   44.45 2864.25   44.48
 3633.44   40.44 4229.27   40.93 4502.33   44.33  4856.5    42.4  4901.5    46.9
  4926.5    43.2  4991.5    35.5  5001.5    30.2  5004.5    24.6  5021.5    23.4
  5028.5    25.6  5031.5    34.7  5046.5    41.9  5073.5    43.2  5081.5      46
  5097.5    42.9 5191.94   42.69 5913.16   46.71 7609.47   44.59 8907.93   46.93
 9102.57   45.79 9153.25   35.72 9229.32   47.0410227.48   45.8212374.23   47.65
#Mann= 6 ,-1 , 0
-7552.64    .068       0-1752.64    .068       0 1457.84    .118       0
  4926.5     .04       0  5073.5    .118       010227.48    .068       0
#XS Ineff= 4 ,-1
 7353.19 7812.12   45.24 9000.61 9424.16   45.11-2486.06  2166.1   44.34
 2817.12 4494.31   44.27
Permanent Ineff=
       F       F       F       F
#Block Obstruct= 1 ,-1
 9102.39 9222.79   45.77
Bank Sta=4926.5,5073.5
XS Rating Curve= 0
Exp/Cntr=.3,.1

Type RM Length L Ch R = 1 ,148487.4,1467.97,1290.81,793.97
XS GIS Cut Line= 6
 3249328.183134313907361.2348678     3236979.566    13907182.378
     3236962.962    13907033.718     3236949.741    13906939.643
     3236928.179    13906818.194     3229581.061    13905853.776
#Sta/Elev= 30
-7545.86    52.5-2035.86    47.5-1445.86   43.85 1668.36   43.61 3149.29   44.65
 3913.46   38.65 4155.38   41.35 4188.29   36.65  4233.3   38.41 4267.83   34.86
 4338.31   41.87 4670.41   41.46 4857.49   46.02  4943.5    43.4  4968.5    36.6
  4971.5    24.3  4988.5    22.2  5006.5    25.5  5018.5    38.1  5038.5    43.2
  5088.5      46 5297.75   39.19 5430.39   44.33 5611.78    45.1 8911.18   45.54
 9091.98   45.09 9180.52   35.33 9232.49   44.12 9378.58   44.1312582.13   47.05
#Mann= 6 ,-1 , 0
-7545.86    .068       0-1445.86    .068       0 1668.36    .118       0
  4943.5     .04       0  5038.5    .118       0 9378.58    .068       0
#XS Ineff= 4 ,-1
 7679.2611957.22   46.12-1751.14 2275.03   43.88 2431.74 4902.73   43.81
 5082.53 5548.74   43.21
Permanent Ineff=
       F       F       F       F
#Block Obstruct= 1 ,-1
 9091.34 9286.95   45.04
Bank Sta=4943.5,5038.5
XS Rating Curve= 0
Exp/Cntr=.3,.1

Type RM Length L Ch R = 1 ,147196.6,1275.4,1379.82,805.74
XS GIS Cut Line= 6
 3250132.6315242 13905463.898217     3237703.524     13905927.17
     3237593.027    13905990.742     3237499.471    13906038.411
     3237359.774    13906135.503     3229984.364    13905012.101
#Sta/Elev= 30
 -7620.4    50.5 -1270.4    46.5  -770.4   41.65 -735.34   44.33   479.4    42.4
  543.48   39.58  640.55   42.65  690.84   39.99  754.19   42.29 1123.85   42.51
 1285.19   41.74 3963.15   43.95 4395.78   42.58 4588.87   39.41 4894.38   41.79
  4956.5    40.4  4966.5    35.1  4983.5      32  4985.5      23  4996.5    22.2
  5011.5    24.2  5036.5    37.8  5061.5      42 6679.14   44.83 9236.78   44.76
  9299.8   34.64 9342.99   44.13  9365.8   45.44 9980.27   44.6712680.42   47.19
#Mann= 8 ,-1 , 0
 -7620.4    .068       0  -770.4    .068       0   479.4    .118       0
 1123.85    .068       0 1285.19    .118       0 4894.38     .04       0
  5061.5    .118       0 9980.27    .068       0
#XS Ineff= 5 ,-1
 8369.7810493.32   45.43 6675.91 7990.48   44.16  345.85 3962.17   43.71
-1089.02  320.82   43.66  5283.6 6357.87   42.99
Permanent Ineff=
       F       F       F       F       F
#Block Obstruct= 1 ,-1
 9236.72 9355.88   44.75
Bank Sta=4894.38,5061.5
XS Rating Curve= 0
Exp/Cntr=.3,.1

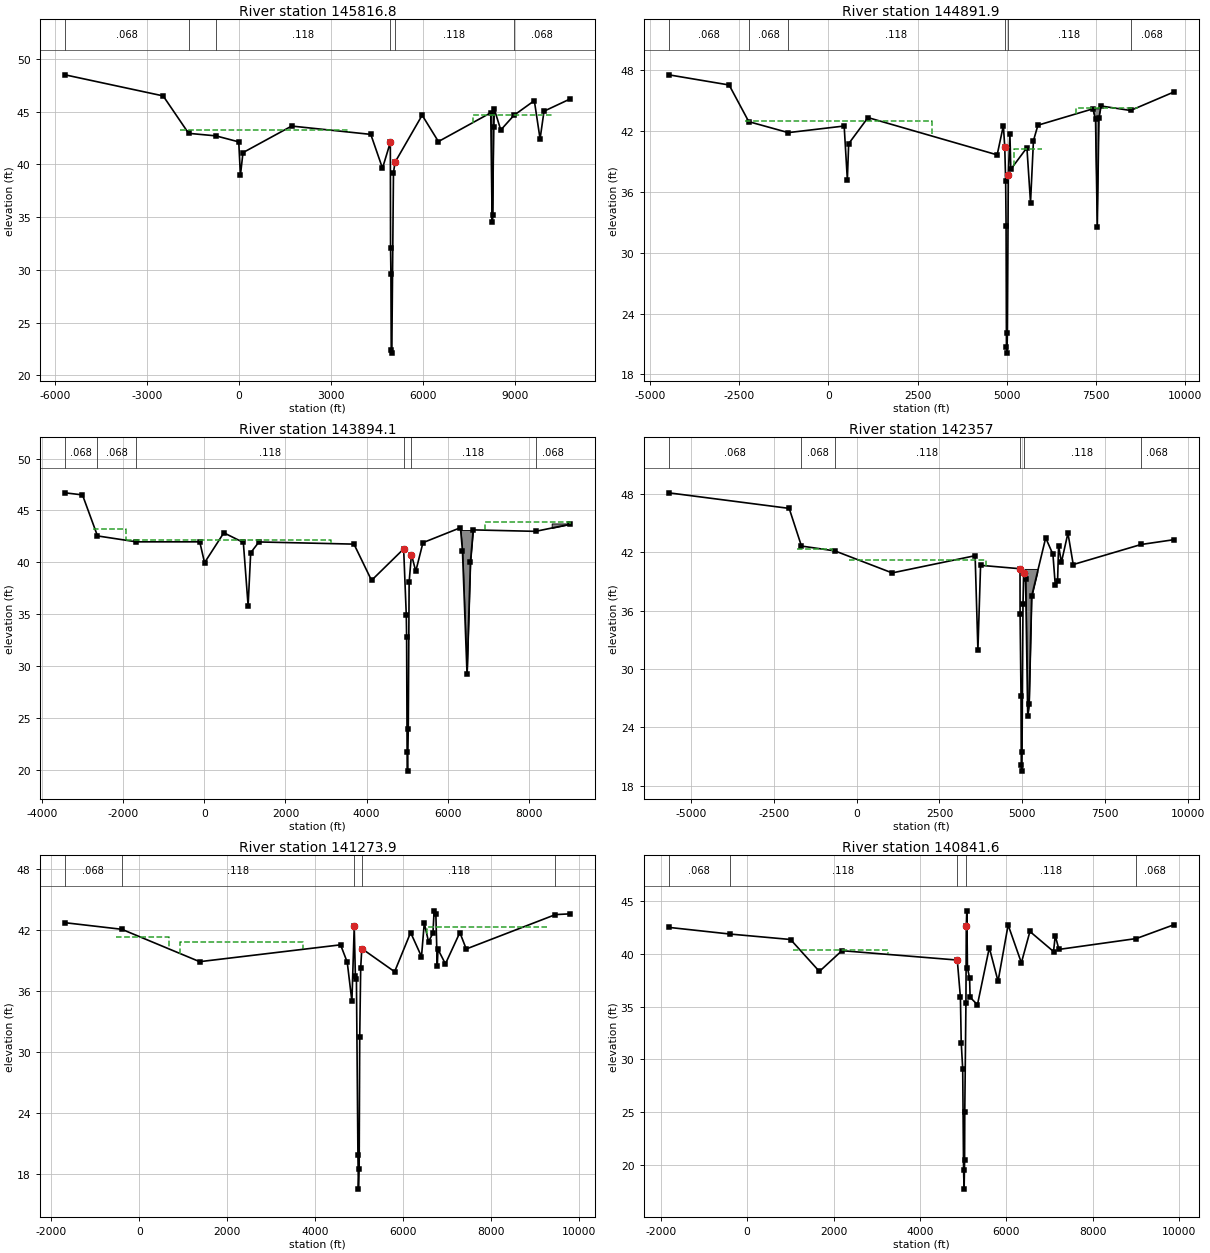
Type RM Length L Ch R = 1 ,145816.8,714.47,924.91,868.3
XS GIS Cut Line= 6
 3247046.053890713904057.0254183     3236614.983    13904942.795
     3236597.963    13905088.149     3236589.073    13905189.761
     3236573.316    13905323.003     3230983.852    13904801.682
#Sta/Elev= 30
-5670.16    48.5-2470.16    46.5-1640.27   42.95 -749.62   42.71   -4.67   42.14
   49.82   38.96  133.07   41.12 1720.24   43.64 4301.71   42.85 4683.26   39.64
    4939    42.1    4946    32.1    4958    29.6    4968    22.4    4987    22.1
    5041    39.2    5091    40.2 5976.62   44.67 6506.72   42.17 8213.66    44.9
 8258.85   34.58 8273.92   35.19 8304.05   43.52 8322.82    45.3 8541.09   43.27
 8970.89   44.66  9635.1   46.05  9822.5   42.42 9950.85   45.05 10794.7    46.2
#Mann= 6 ,-1 , 0
-5670.16    .068       0-1640.27    .068       0 -749.62    .118       0
    4939     .04       0    5091    .118       0 8970.89    .068       0
#XS Ineff= 2 ,-1
 7630.7810253.68   44.72-1920.02 3591.86   43.22
Permanent Ineff=
       F       F
#Block Obstruct= 1 ,-1
 8212.92 8319.77   44.79
Bank Sta=4939,5091
XS Rating Curve= 0
Exp/Cntr=.3,.1

Type RM Length L Ch R = 1 ,144891.9,708.34,997.84,1275.24
XS GIS Cut Line= 6
 3245488.729985213903640.4153625     3236177.483    13904406.336
     3236099.542     13904451.46      3236034.59     13904488.96
     3235927.483    13904557.378     3231439.759    13904117.822
#Sta/Elev= 30
-4471.71    47.5-2781.71    46.5-2231.71   42.89 -1124.3   41.81  441.28   42.46
  530.54   37.17   567.8   40.72 1108.77   43.29 4727.72   39.62 4901.66    42.5
  4940.5    40.4  4965.5      37  4977.5    32.6  4987.5    20.7  5002.5    20.1
  5014.5    22.1  5040.5    37.6  5084.5    41.7  5110.5    38.2 5561.16   40.33
 5662.51   34.92 5744.51   41.02 5869.59   42.54 7409.06   44.15 7483.84   43.11
 7533.17    32.5 7578.39   43.21 7640.19   44.43 8464.98   43.99 9672.34    45.8
#Mann= 6 ,-1 , 0
-4471.71    .068       0-2231.71    .068       0 -1124.3    .118       0
  4940.5     .04       0  5040.5    .118       0 8464.98    .068       0
#XS Ineff= 3 ,-1
 6930.07 8678.99   44.27-2324.43 2909.19   42.93 5188.81 5972.03   40.23
Permanent Ineff=
       F       F       F
#Block Obstruct= 1 ,-1
 7402.71 7633.05   44.15
Bank Sta=4940.5,5040.5
XS Rating Curve= 0
Exp/Cntr=.3,.1

Type RM Length L Ch R = 1 ,143894.1,1451.88,1537.07,1227.89
XS GIS Cut Line= 6
 3244240.588125713903307.5464673      3235998.83    13903767.124
     3235926.083    13903664.988     3235867.792    13903571.703
     3235788.412    13903451.496     3232211.294    13902136.379
#Sta/Elev= 30
-3433.44    46.7-3003.44    46.5-2633.44   42.55-1675.78   41.98 -112.24   41.98
    5.69   39.97   480.8   42.85  961.99   41.92 1079.74   35.83 1143.28   40.93
 1347.34   41.97 3689.18   41.76 4122.36   38.27    4914    41.3    4979    34.9
    4987    32.8    4999    21.7    5009    19.9    5028      24    5049    38.1
 5105.74   40.76  5212.6   39.15 5389.86    41.9 6313.76   43.34 6363.78    41.1
  6476.1   29.26 6560.34   40.05    6628   43.13 8166.68   42.99 9011.78   43.67
#Mann= 6 ,-1 , 0
-3433.44    .068       0-2633.44    .068       0-1675.78    .118       0
    4914     .04       0 5105.74    .118       0 8166.68    .068       0
#XS Ineff= 4 ,-1
 6916.31 9011.78   43.87-2742.37-1936.72   43.26 5935.85 6866.35   42.69
-1936.72 3127.25   42.16
Permanent Ineff=
       F       F       F       F
#Block Obstruct= 2 ,-1
 6312.72 6627.19   43.12 8563.18 9011.78   43.75
Bank Sta=4914,5105.74
XS Rating Curve= 0
Exp/Cntr=.3,.1

Type RM Length L Ch R = 1 ,142357  ,1043.23,1083.1,1188.14
XS GIS Cut Line= 6
 3247442.541757813903577.1200444     3237005.608    13902505.295
      3236902.26    13902465.618     3236792.285    13902431.996
     3236677.483    13902401.128     3232386.643    13901487.588
#Sta/Elev= 30
 -5661.1    48.1 -2031.1    46.5 -1661.1   42.63 -650.99   42.13 1074.02   39.87
 3575.67   41.64  3659.7   31.95 3740.35   40.65  4929.5    40.3  4931.5    35.6
  4959.5    27.2  4967.5    20.1  4979.5    19.5  4990.5    21.5  5019.5    36.7
  5044.5    39.9 5096.99   39.25 5161.92   25.15 5203.14   26.42 5279.82   37.47
 5703.63   43.47 5921.95   41.78 5992.63   38.61 6061.96      39 6092.64   42.68
 6177.29   40.96 6374.81   43.96 6534.05   40.73 8579.32   42.79 9562.32   43.28
#Mann= 6 ,-1 , 0
 -5661.1    .068       0 -1661.1    .068       0 -650.99    .118       0
  4931.5     .04       0  5044.5    .118       0 8579.32    .068       0
#XS Ineff= 3 ,-1
 5704.22 9137.36    42.8-1789.07 -726.13   42.33  -223.6 3891.36   41.15
Permanent Ineff=
       F       F       F
#Block Obstruct= 1 ,-1
 5070.14 5453.53   40.28
Bank Sta=4929.5,5044.5
XS Rating Curve= 0
Exp/Cntr=.3,.1

Type RM Length L Ch R = 1 ,141273.9,447.73,432.32,422.12
XS GIS Cut Line= 6
     3243810.759    13902671.861     3237419.156    13901575.263
     3237298.806    13901496.933     3237197.664    13901428.712
     3237083.733    13901369.878     3232649.667    13900137.402
#Sta/Elev= 30
-1687.66   42.75 -396.23    42.1 1373.48   38.91 4578.64   40.57 4729.84   38.86
 4836.24   35.01  4889.1    42.4    4915    37.5    4939    37.2    4973    19.9
    4984    16.5    5001    18.5    5014    31.5    5036    38.3    5061    40.2
 5807.32   37.92 6171.32   41.78 6418.74   39.41 6481.76   42.72  6578.7   40.88
 6679.52   41.72 6705.18   43.92 6745.36    43.6 6777.22   38.45 6793.52   40.13
 6962.62   38.69 7291.04   41.78 7435.94   40.16  9465.8   43.55 9793.32   43.62
#Mann= 5 ,-1 , 0
-1687.66    .068       0 -396.23    .118       0  4889.1     .04       0
    5061    .118       0  9465.8    .068       0
#XS Ineff= 4 ,-1
 6537.95 9275.03   42.31 -531.47  685.31    41.3  928.31 3717.35   40.87
 6153.31 6493.36   40.75
Permanent Ineff=
       F       F       F       F
Bank Sta=4889.1,5061
XS Rating Curve= 0
Exp/Cntr=.3,.1

Type RM Length L Ch R = 1 ,140841.6,898.81,1003.45,915.9
XS GIS Cut Line= 6
     3244147.615    13902190.158      3237612.04    13901189.495
      3237498.89    13901116.507     3237379.942    13901050.573
     3237261.342    13900996.612     3232772.411     13899699.03
#Sta/Elev= 30
-1812.58   42.53  -402.7    41.9 1005.66   41.38 1673.06   38.35 2193.88   40.32
  4864.6   39.43    4937    35.9    4956    31.6    4990    29.1    5010    19.5
    5023    17.7    5034    20.5    5038      25    5065    35.4    5073    42.7
    5085    44.1    5100    38.7    5150    37.7 5161.36    35.9 5331.56   35.19
 5605.98    40.6 5808.32   37.42 6041.46   42.76  6348.2   39.17 6545.74   42.14
 7092.42   40.24 7132.16   41.73 7217.88   40.44 9009.16   41.47  9872.8   42.77
#Mann= 5 ,-1 , 0
-1812.58    .068       0  -402.7    .118       0  4864.6     .04       0
    5073    .118       0 9009.16    .068       0
#XS Ineff= 4 ,-1
 6038.12 9646.01   42.38  -895.1  881.12   41.39 1066.01 3251.83   40.43
  5616.2 5968.14   40.05
Permanent Ineff=
       F       F       F       F
Bank Sta=4864.6,5073
XS Rating Curve= 0
Exp/Cntr=.3,.1

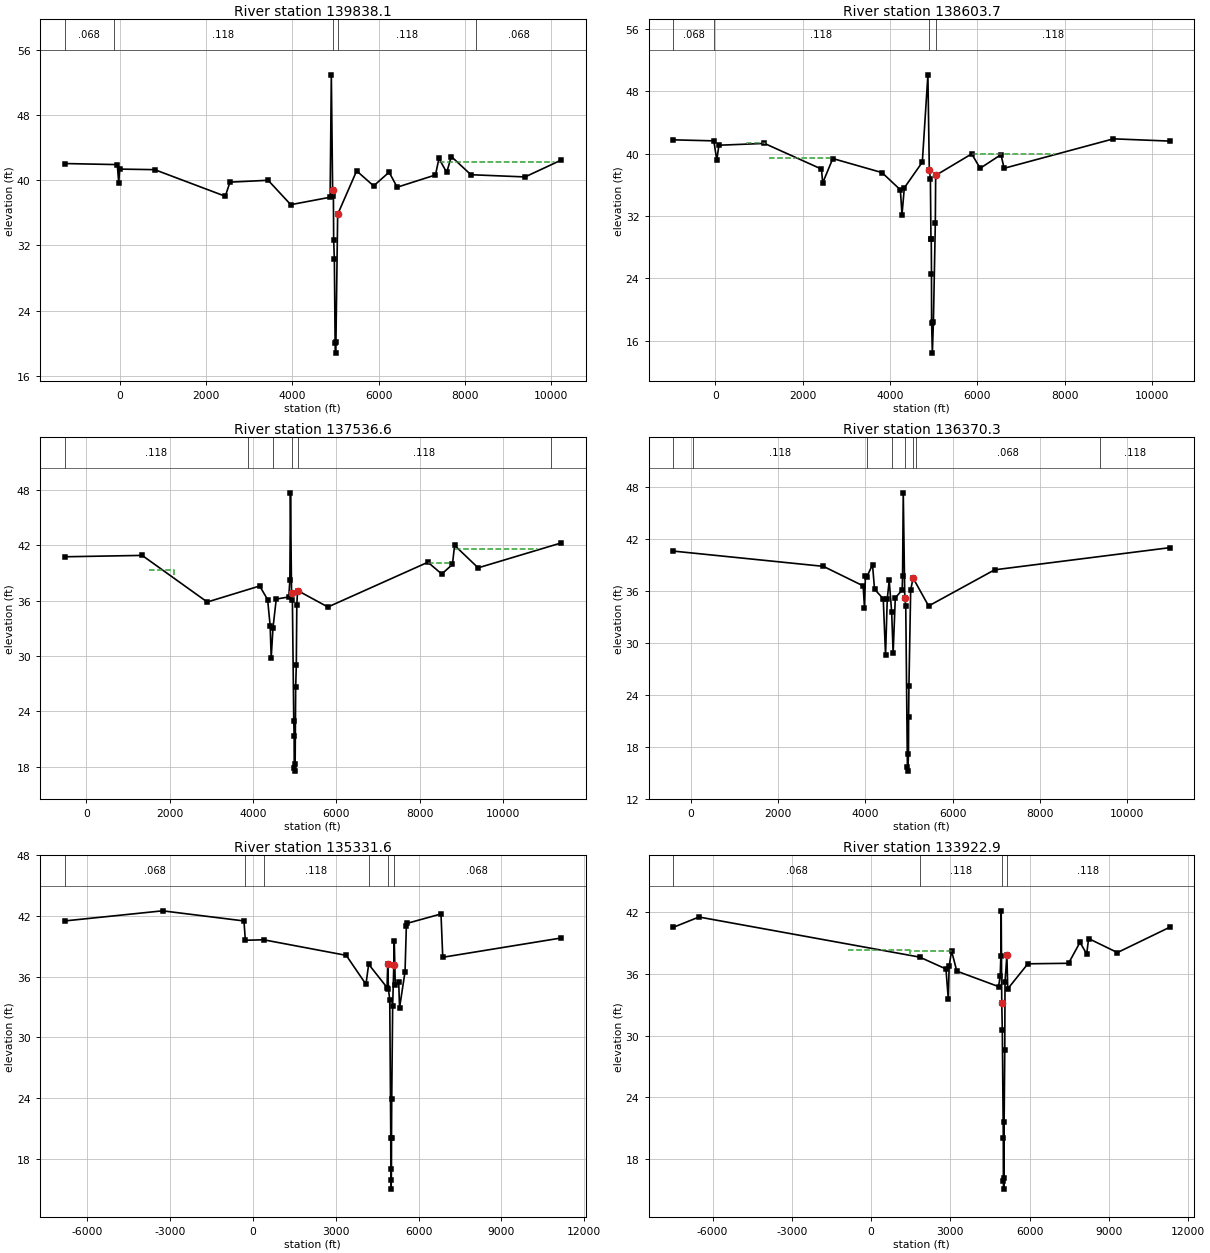
Type RM Length L Ch R = 1 ,139838.1,1066.92,1234.44,1298.19
XS GIS Cut Line= 6
     3244195.042    13901722.359     3238243.296    13900435.495
     3238116.232    13900361.447     3238031.373    13900310.458
     3237927.668    13900242.611     3233017.899    13899050.239
#Sta/Elev= 30
-1285.42   42.03  -62.51    41.9  -29.84   39.65    -7.3   41.35  804.74   41.28
 2441.86   38.02 2551.48   39.75 3436.14   39.98  3961.4   36.99  4874.5    37.9
  4902.5    52.9  4932.5    38.8  4950.5      38  4956.5    32.7  4972.5    30.3
  4990.5      20  5000.5    18.8  5009.5    20.2  5049.5    35.8 5489.64   41.13
  5884.3   39.29 6242.68   40.97 6429.88   39.13  7318.4   40.63 7399.12   42.65
 7579.14   40.94 7686.32   42.89 8140.26   40.66 9396.44   40.3910226.34   42.43
#Mann= 5 ,-1 , 0
-1285.42    .068       0-134.235    .118       04930.935     .04       0
5046.045    .118       08269.335    .068       0
#XS Ineff= 4 ,-1
 7403.22 10071.1   42.19 -939.39  773.89   41.28 5490.16 7403.22   40.98
 1046.45 3374.08   39.72
Permanent Ineff=
       F       F       F       F
Bank Sta=4932.5,5049.5
XS Rating Curve= 0
Exp/Cntr=.3,.1

Type RM Length L Ch R = 1 ,138603.7,1181.7,1067.08,994.14
XS GIS Cut Line= 6
     3244385.385     13900912.09     3238974.358    13899573.003
     3238756.435    13899325.886      3238675.47    13899235.965
     3238573.316    13899135.503     3233456.271     13898191.03
#Sta/Elev= 30
 -964.34   41.76  -37.36   41.63   32.03   39.17   79.64   41.07 1124.26    41.3
 2430.54   38.01 2458.14   36.23 2690.06   39.36 3816.56   37.56 4238.12   35.35
 4275.94   32.16 4328.82    35.6  4741.5    38.9  4869.5    50.1  4901.5    37.9
  4926.5    36.8  4939.5      29  4946.5      29  4951.5    24.6  4954.5    18.3
  4971.5    14.4  4995.5    18.4  5039.5    31.1  5047.5    37.2 5873.62   39.96
  6066.2   38.11 6544.02   39.86 6615.64   38.11 9121.08   41.8910407.14    41.6
#Mann= 4 ,-1 , 0
 -964.34    .068       0  -37.36    .118       0  4901.5     .04       0
  5047.5    .118       0
#XS Ineff= 4 ,-1
  9122.510080.33    41.6  727.83 1130.66   41.34 5875.58  7749.2   39.92
 1224.13  2695.4   39.37
Permanent Ineff=
       F       F       F       F
#Block Obstruct= 2 , 0
          703.25   41.5810090.12           41.97
Bank Sta=4901.5,5047.5
XS Rating Curve= 0
Exp/Cntr=.3,.1

Type RM Length L Ch R = 1 ,137536.6,1186.73,1166.29,1207.37
XS GIS Cut Line= 6
     3244629.032    13899874.914     3239495.191    13898526.128
     3239360.138    13898435.046      3239272.26    13898375.772
     3239182.691    13898312.586     3233070.504    13897103.866
#Sta/Elev= 30
 -523.59   40.76 1338.94   40.91 2902.52   35.85 4161.36   37.59 4352.31   36.11
 4413.04   33.26 4438.03   29.79  4481.6   33.07 4559.44   36.17    4861    36.4
    4886    38.2    4901    47.7    4927    36.8    4947    36.1    4980    22.9
    4989    21.3    4991    17.8    5001    17.5    5013    18.3    5026    26.6
    5041      29    5053    35.5    5071    37.1 5799.49   35.31 8202.24   40.17
 8533.93   38.89 8790.86   39.93 8842.51      42 9407.71   39.5611393.54   42.25
#Mann= 6 ,-1 , 0
 -523.59    .118       0 3885.75    .068       0  4481.6    .118       0
    4927     .04       0    5071    .118       0 11155.2    .068       0
#XS Ineff= 4 ,-1
 8845.7110813.49   41.59 1093.23 1332.86    40.8 8192.49 8736.16   40.04
 1500.59 2104.97   39.35
Permanent Ineff=
       F       F       F       F
#Block Obstruct= 2 , 0
          1031.3   41.12
Bank Sta=4927,5071
XS Rating Curve= 0
Exp/Cntr=.3,.1

Type RM Length L Ch R = 1 ,136370.3,1100.14,1038.71,972.96
XS GIS Cut Line= 6
     3244936.436    13898566.333      3239874.04    13897437.029
     3239749.277    13897341.019     3239640.059    13897261.668
     3239552.483    13897192.795     3233859.574    13896104.378
#Sta/Elev= 30
 -408.68   40.58 3033.68   38.82 3946.99   36.57 3977.72   34.02 3999.21    37.7
 4032.13   37.62 4162.15   39.01 4208.25   36.18 4408.05   35.08 4461.13   28.56
 4500.26   35.06 4545.07    37.2 4601.46   33.53 4635.23   28.78 4684.68   35.18
  4842.5    36.1  4851.5    37.7  4867.5    47.3  4902.5    35.2  4924.5    34.3
  4962.5    15.7  4972.5    15.2  4987.5    17.2  4990.5    21.5  4997.5      25
  5037.5    36.1 5093.22   37.47 5448.96   34.25 6964.38   38.4210978.01   40.97
#Mann= 8 ,-1 , 0
 -408.68    .068       0   46.79    .118       0 4032.13    .068       0
 4601.46    .118       0  4902.5     .04       0 5093.22    .118       0
  5170.8    .068       0 9383.88    .118       0
#XS Ineff= 1 ,-1
 2193.57 4162.29   38.65
Permanent Ineff=
       F
#Block Obstruct= 2 , 0
          177.99   40.76
Bank Sta=4902.5,5093.22
XS Rating Curve= 0
Exp/Cntr=.3,.1

Type RM Length L Ch R = 1 ,135331.6,1400.7,1408.69,1368.83
XS GIS Cut Line= 6
 3251557.9655754 13899020.733273     3240193.108    13896385.503
     3240089.117    13896348.039     3239987.749    13896317.047
     3239854.566    13896276.128     3234017.388    13895069.819
#Sta/Elev= 30
-6826.22    41.5-3276.22    42.5 -326.22    41.5 -276.22   39.59  385.14   39.64
 3380.27    38.1 4094.79   35.24 4192.99   37.22 4858.86   34.92 4884.58   37.23
    4909    34.8    4957    33.7    4994    20.1    4997    15.9    5009      15
    5019      17    5021    20.1    5029    23.9    5063    33.1    5104    37.1
  5120.6   39.52 5157.51   35.16 5281.52   35.48 5312.74   32.92 5511.07   36.49
 5559.31   41.03 5595.02   41.27 6814.31   42.19 6878.14   37.9111156.54   39.81
#Mann= 6 ,-1 , 0
-6826.22    .068       0 -276.22    .068       0  385.14    .118       0
 4192.99    .068       0 4884.58     .03       0    5104    .068       0
#Block Obstruct= 2 , 0
                        10989.31           40.57
Bank Sta=4884.58,5104
XS Rating Curve= 0
Exp/Cntr=.3,.1

Type RM Length L Ch R = 1 ,133922.9,1355.29,1271.34,995.02
XS GIS Cut Line= 6
 3252545.651353713898175.0029652      3240665.39    13895046.011
     3240533.707    13895007.338      3240413.86    13894979.669
     3240275.729    13894957.451     3234289.111    13893841.602
#Sta/Elev= 30
-7484.06    40.5-6514.06    41.5 1836.84   37.61 2830.84   36.46 2919.94   33.53
 2952.22   36.74 3042.72   38.21 3241.48   36.25 4822.24   34.75  4883.5    35.8
  4908.5    37.7  4921.5    42.1  4942.5    33.2  4963.5    30.5  5000.5    20.1
  5003.5    15.9  5014.5    15.1  5026.5    16.2  5032.5    21.6  5056.5    28.6
  5065.5    35.2 5136.14   37.77 5169.18   34.53 5929.42   36.96  7470.3   37.01
 7902.16   39.04    8157   37.91 8227.86   39.41 9318.22   38.0511291.22    40.5
#Mann= 4 ,-1 , 0
-7484.06    .068       0 1836.84    .118       0  4942.5     .04       0
 5136.14    .118       0
#XS Ineff= 3 ,-1
 8230.4810520.41    39.3 -887.12 1454.64   38.34 1478.42 3042.13   38.17
Permanent Ineff=
       F       F       F
Bank Sta=4942.5,5136.14
XS Rating Curve= 0
Exp/Cntr=.3,.1

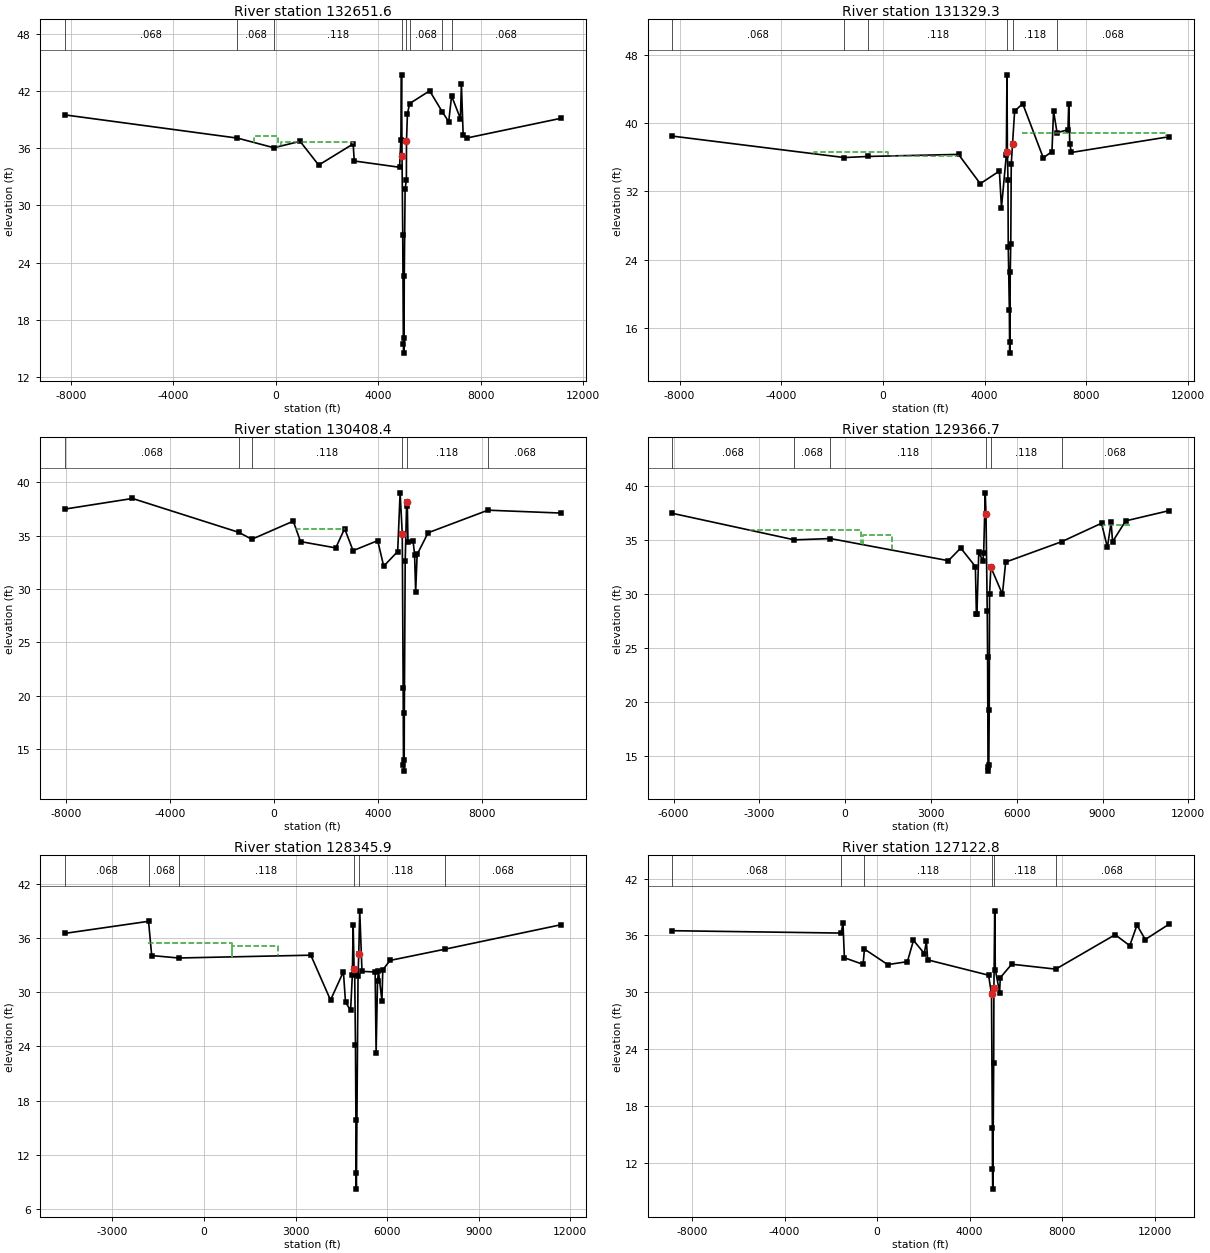
Type RM Length L Ch R = 1 ,132651.6,908.55,1322.27,1306.37
XS GIS Cut Line= 6
  3253105.87875313897131.3025639     3240629.967    13893646.772
     3240457.122    13893803.247     3240376.863    13893875.513
     3240245.191    13894000.086     3234459.215    13892817.238
#Sta/Elev= 30
-8242.56    39.5-1492.56   37.06  -72.81   36.05  951.61   36.72 1677.68   34.23
 3023.22   36.45 3066.04   34.66    4836      34    4886    36.9    4911    43.7
    4931    35.2    4959    26.9    4983    15.5    4996    14.5    5010    16.1
    5019    22.6    5051    31.7    5101    32.7 5105.68   36.77 5141.86   39.56
 5224.38   40.68 6009.16   42.02 6509.18   39.79 6754.24   38.78 6866.26   41.49
 7210.62   39.11 7249.02    42.7 7318.22   37.39  7459.5   37.0711138.88   39.14
#Mann= 8 ,-1 , 0
-8242.56    .068       0-1492.56    .068       0  -72.81    .118       0
    4931     .04       0 5105.68    .118       0 5224.38    .068       0
 6509.18    .118       0 6866.26    .068       0
#XS Ineff= 3 ,-1
 6198.0411138.88   38.91 -832.58   98.09   37.26  220.07 3004.98   36.65
Permanent Ineff=
       F       F       F
Bank Sta=4931,5105.68
XS Rating Curve= 0
Exp/Cntr=.3,.1

Type RM Length L Ch R = 1 ,131329.3,737.19,920.92,1096.81
XS GIS Cut Line= 6
 3253340.9880238 13896298.881254     3240789.374    13892778.889
     3240620.159    13892774.421     3240469.366    13892766.518
     3240311.153    13892761.177     3234518.959    13891153.541
#Sta/Elev= 30
-8283.22    38.5-1523.22   35.98 -576.06   36.11 2972.66   36.35 3827.74   32.91
 4580.62   34.39 4662.66    30.1  4854.5    36.3  4878.5    45.7  4896.5    36.6
  4917.5    33.4  4929.5    25.5  4972.5    18.1  4985.5      13  4995.5    14.3
  5007.5    22.5  5028.5    25.8  5047.5    35.2  5097.5    37.6 5180.46   41.44
 5498.56   42.31  6307.3   35.94 6648.74   36.69    6711   41.45    6849    38.9
 7278.06   39.25 7307.96   42.32 7349.26   37.56 7416.62   36.5811242.36   38.42
#Mann= 6 ,-1 , 0
-8283.22    .068       0-1523.22    .068       0 -576.06    .118       0
  4896.5     .04       0  5097.5    .118       0    6849    .068       0
#XS Ineff= 3 ,-1
 5464.5511118.58   38.82-2693.58  213.08   36.59  268.36 2976.83   36.19
Permanent Ineff=
       F       F       F
#Block Obstruct= 2 , 0
        -7188.26   39.32
Bank Sta=4896.5,5097.5
XS Rating Curve= 0
Exp/Cntr=.3,.1

Type RM Length L Ch R = 1 ,130408.4,1014.25,1041.74,961.82
XS GIS Cut Line= 6
 3253582.636658813895616.4970367     3241267.594    13892158.973
     3241116.042    13892041.383     3241010.622    13891961.944
     3240824.797    13891822.447     3235373.713    13890007.165
#Sta/Elev= 30
 -8051.3    37.5 -5441.3    38.5 -1351.3   35.32  -851.2   34.67   743.1   36.37
 1022.88   34.45 2376.79   33.86 2718.66   35.67 3042.44    33.6 3991.06   34.54
 4221.14   32.14 4758.98   33.52 4852.94   39.03    4935    35.2    4970    20.7
    4982    13.5    4995    12.9    5009    13.9    5015    18.4    5048    32.6
    5105    38.2    5130    37.8    5155    34.4 5349.44   34.55 5409.57   33.22
 5450.51   29.71 5506.38   33.24 5928.38   35.28 8231.53    37.411041.47   37.13
#Mann= 6 ,-1 , 0
 -8051.3    .068       0 -1351.3    .068       0  -851.2    .118       0
    4935     .04       0    5105    .118       0 8231.53    .068       0
#XS Ineff= 4 ,-1
 9172.3810160.99   36.98-3025.23  747.98   36.33  814.88 2714.86   35.67
 5122.38 5938.23   35.08
Permanent Ineff=
       F       F       F       F
#Block Obstruct= 2 , 0
        -6546.45   38.3210188.31           37.51
Bank Sta=4935,5105
XS Rating Curve= 0
Exp/Cntr=.3,.1

Type RM Length L Ch R = 1 ,129366.7,1052.98,1020.74,1035.26
XS GIS Cut Line= 6
 3252056.107753313894676.7259689     3241854.566    13891281.336
     3241650.791    13891144.618     3241566.835    13891092.156
     3241427.001      13891007.7     3235544.664    13889383.697
#Sta/Elev= 30
-6045.06    37.5-1775.06   35.04 -519.86   35.16 3609.24   33.11 4041.98   34.28
 4553.25   32.57 4588.84   28.19 4606.94   28.16 4671.87   33.87  4818.5    33.1
  4843.5    33.8  4898.5    39.4  4925.5    37.4  4968.5    28.4  4981.5    24.2
  4995.5      14  5008.5    13.6  5023.5    14.2  5038.5    19.3  5049.5      30
  5095.5    32.5 5499.61      30 5613.66   32.98 7571.76   34.87 8965.66   36.58
 9170.42   34.34 9300.43   36.66 9352.24   34.87 9810.03    36.811316.84   37.74
#Mann= 6 ,-1 , 0
-6045.06    .068       0-1775.06    .068       0 -519.86    .118       0
  4925.5     .04       0  5095.5    .118       0 7571.76    .068       0
#XS Ineff= 3 ,-1
  9009.410010.59   36.41-3360.41  569.86   35.97  627.32 1650.11   35.48
Permanent Ineff=
       F       F       F
Bank Sta=4925.5,5095.5
XS Rating Curve= 0
Exp/Cntr=.3,.1

Type RM Length L Ch R = 1 ,128345.9,1137.89,1223.15,1229.37
XS GIS Cut Line= 6
 3251140.828652213893338.3941808     3242330.308    13890352.361
      3242147.05    13890252.237     3242050.842    13890198.908
      3241887.51    13890104.394     3235705.559    13888257.432
#Sta/Elev= 30
-4566.94    36.5-1816.94   37.84-1713.82   34.05 -833.72   33.78 3499.02   34.09
  4144.6   29.12 4566.18   32.26 4635.58   28.87 4802.64      28    4859    31.9
    4886    37.4    4916    32.6    4936      32    4961    24.2    4976    15.9
    4978      10    4991     8.2    5046    31.8    5069    34.2    5101      39
    5175    32.3 5605.78   32.23 5637.72   23.31 5684.06   31.22 5715.36   32.31
 5828.68   29.03 5855.68   32.46 6092.98   33.51 7900.74   34.7611695.32   37.46
#Mann= 6 ,-1 , 0
-4566.94    .068       0-1816.94    .068       0 -833.72    .118       0
    4916     .04       0    5069    .118       0 7900.74    .068       0
#XS Ineff= 4 ,-1
 9554.2311356.38   35.79-1825.79  905.27   35.46  910.34 2438.51   35.14
 5265.73 6146.85    32.1
Permanent Ineff=
       F       F       F       F
#Block Obstruct= 2 , 0
        -1819.07   37.72
Bank Sta=4916,5069
XS Rating Curve= 0
Exp/Cntr=.3,.1

Type RM Length L Ch R = 1 ,127122.8,902.84,921.02,834.46
XS GIS Cut Line= 6
 3255468.415786813894622.3642381     3242861.664    13889325.071
      3242776.64    13889228.164     3242701.829    13889155.919
     3242578.274    13889041.681     3235434.049     13887151.28
#Sta/Elev= 30
-8851.67    36.5-1551.67   36.25-1472.32   37.29-1411.96   33.64 -602.39   32.94
 -545.22   34.56   462.1   32.92 1312.52   33.23 1575.63   35.48 2044.94   34.09
 2133.67   35.41 2189.44   33.42 4822.81    31.8    4950    29.8    4986    15.7
    4992    11.3    5004     9.2    5044    22.5    5054    30.5    5089    38.6
    5114    32.4 5300.76   29.97  5327.9   31.53 5822.95   32.96 7727.73   32.44
10297.13   36.0810927.69   34.9211239.96   37.0911599.45   35.5712614.11   37.17
#Mann= 6 ,-1 , 0
-8851.67    .068       0-1551.67    .068       0 -545.22    .118       0
    4950     .04       0    5054    .118       0 7727.73    .068       0
#XS Ineff= 2 ,-1
11245.5312407.63   36.37-1506.68 2134.29   35.37
Permanent Ineff=
       F       F
#Block Obstruct= 2 , 0
        -1475.57   36.92
Bank Sta=4950,5054
XS Rating Curve= 0
Exp/Cntr=.3,.1