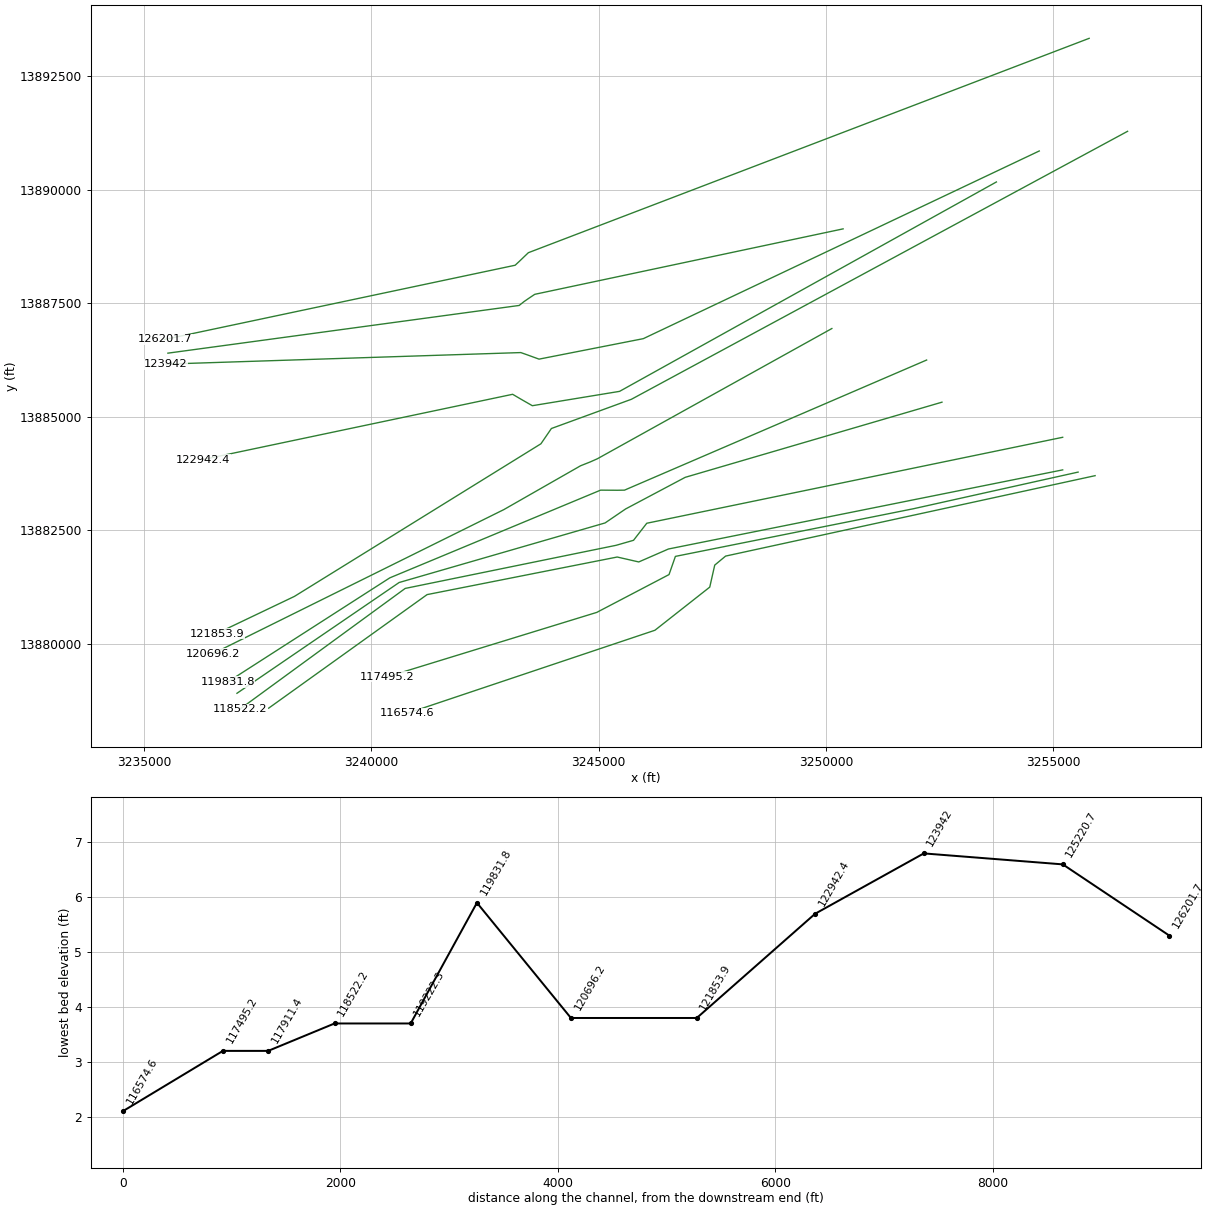
HEC-RAS study Q100-00-00.prj: Q100-00-00

--- Q100-00-00.g01 (geometry) --- (continued)

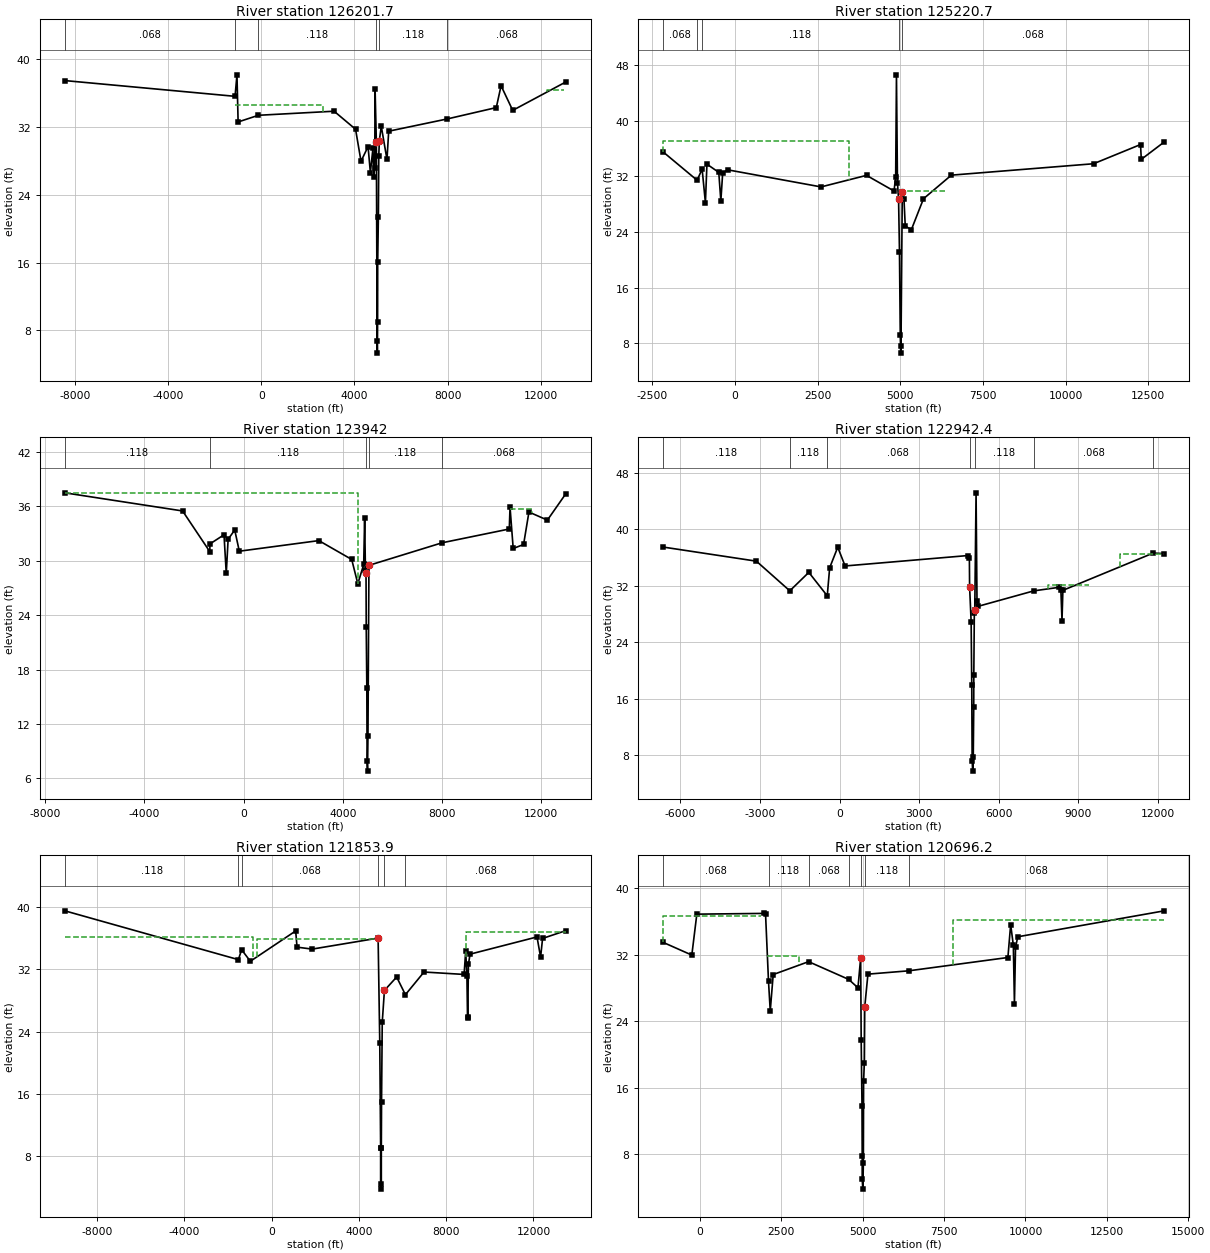
Type RM Length L Ch R = 1 ,126201.7,984.95,981.09,872.99
XS GIS Cut Line= 6
 3255788.346939513893329.9709135     3243453.524    13888609.461
     3243338.508    13888499.632     3243264.416    13888428.082
     3243162.766    13888333.205     3235454.161    13886698.763
#Sta/Elev= 30
-8422.24    37.5-1122.24   35.64-1040.54   38.18 -991.16   32.61  -120.8    33.4
 3125.22   33.88    4046   31.75  4279.8   27.97 4582.02    29.7  4681.4   26.64
 4792.34   29.51  4817.5    26.1  4867.5    27.2  4883.5    36.5  4938.5    30.2
  4971.5     6.7  4980.5     5.3  4991.5       9  4995.5    16.1  5024.5    21.4
  5041.5    28.6  5066.5    30.4 5148.04   32.11 5393.34   28.18 5467.04   31.52
 7980.42   32.9710081.32   34.31 10286.5   36.8910785.92   33.9813066.04   37.34
#Mann= 6 ,-1 , 0
-8422.24    .068       0-1122.24    .068       0  -120.8    .118       0
  4938.5     .04       0  5066.5    .118       0 7980.42    .068       0
#XS Ineff= 2 ,-1
12262.6912983.15   36.36-1132.48 2629.25   34.57
Permanent Ineff=
       F       F
#Block Obstruct= 2 , 0
        -1031.56    36.8
Bank Sta=4938.5,5066.5
XS Rating Curve= 0
Exp/Cntr=.3,.1

Type RM Length L Ch R = 1 ,125220.7,1445.18,1278.69,1001.79
XS GIS Cut Line= 6
 3250376.467272213889134.2029349     3243594.149    13887692.795
     3243443.688    13887592.203     3243351.943    13887527.963
     3243251.326    13887447.611     3235524.552    13886397.085
#Sta/Elev= 30
-2169.16    35.5-1147.16   31.45 -994.12   33.04 -895.12   28.21 -849.12   33.76
 -490.96   32.58  -428.6   28.47 -372.96   32.48 -226.38   32.95 2603.34   30.49
 3977.16   32.15    4809    29.9    4859    31.9    4883    46.6    4913    31.1
    4947    28.7    4974    21.2    4998     9.2    5011     6.6    5020     7.6
    5059    29.8    5109    28.8 5148.84   24.86 5334.52   24.35 5700.06   28.79
 6542.98   32.1810843.96   33.8212264.18   36.5812287.74   34.4512984.24   36.96
#Mann= 5 ,-1 , 0
-2169.16    .068       0-1147.16    .068       0 -994.12    .118       0
    4947     .04       0    5059    .068       0
#XS Ineff= 3 ,-1
-2169.16 3447.55    37.112228.4212755.67    35.9 5079.07 6337.82   29.85
Permanent Ineff=
       F       F       F
#Block Obstruct= 2 , 0
        -2168.39   37.04
Bank Sta=4947,5059
XS Rating Curve= 0
Exp/Cntr=.3,.1

Type RM Length L Ch R = 1 ,123942  ,1011.84,999.53,990.04
BEGIN DESCRIPTION:
Ineffective area is due to blocked flow downstream (see station 122942.4). A "contraction" ratio of 1:1 was used.
END DESCRIPTION:
XS GIS Cut Line= 6
 3254690.851798613890849.5591645      3245981.78     13886716.44
     3243688.119    13886265.397     3243407.432    13886367.436
     3243286.556    13886409.845     3235484.329    13886155.742
#Sta/Elev= 30
-7211.82    37.5-2461.82    35.5-1361.82      31-1361.82   31.86 -791.16   32.87
 -700.76   28.61 -625.13   32.38  -359.1    33.4 -174.39   31.06 3033.83   32.23
 4359.92   30.15 4606.31   27.47  4843.5    29.6  4881.5    34.7  4913.5      29
  4937.5    28.7  4945.5    22.7  4969.5      16  4980.5     7.9  4997.5     6.8
  5015.5    10.7  5054.5    29.5 8007.69   31.9910716.02   33.5110746.37   35.91
10873.95   31.36 11292.9    31.811508.62   35.3812253.18   34.4912998.94   37.41
#Mann= 5 ,-1 , 0
-7211.82    .118       0-1361.82    .118       0  4937.5     .04       0
  5054.5    .118       0 8007.69    .068       0
#XS Ineff= 2 ,-1
-7211.82 4607.26   37.4610751.5711619.56   35.69
Permanent Ineff=
       F       F
#Block Obstruct= 2 , 0
                        12208.81           36.83
Bank Sta=4937.5,5054.5
XS Rating Curve= 0
Exp/Cntr=.3,.1

Type RM Length L Ch R = 1 ,122942.4,575.55,1088.5,1477.32
XS GIS Cut Line= 6
 3253748.2601364 13890167.118653      3245459.47    13885555.752
     3243540.783    13885239.823     3243283.427     13885387.29
     3243107.441    13885491.161     3236297.373    13884054.472
#Sta/Elev= 30
-6646.76    37.5-3136.76    35.5-1876.76   31.29-1159.72   33.91 -464.69   30.58
 -374.25   34.56  -68.98   37.48   207.6   34.82 4843.85    36.3 4893.85      36
 4901.85    31.9 4960.15    26.9 4983.15    17.9 4998.15     7.2 5019.15     5.7
 5040.15     7.7 5058.15    14.8 5061.15    19.4 5080.15    28.1 5097.15    28.5
 5146.15    45.2 5181.15    29.8 5231.15    29.1 7327.96   31.29 8282.24   31.79
 8343.84   31.38 8385.92   27.06 8419.18   31.3611825.08   36.6512243.88   36.57
#Mann= 7 ,-1 , 0
-6646.76    .118       0-1876.76    .118       0 -464.69    .068       0
 4901.85     .04       0 5097.15    .118       0 7327.96    .068       0
11825.08    .118       0
#XS Ineff= 4 ,-1
-5770.05  -79.89   36.5710580.6512243.88   36.49  -61.82  4845.9   36.26
  7842.1 9410.87   32.11
Permanent Ineff=
       F       F       F       F
Bank Sta=4901.85,5097.15
XS Rating Curve= 0
Exp/Cntr=.3,.1

Type RM Length L Ch R = 1 ,121853.9,1094.75,1157.72,896.56
XS GIS Cut Line= 6
 3256633.6424038 13891282.762002     3245720.625    13885381.648
     3243959.801    13884737.692     3243729.547    13884401.167
     3238306.976    13881040.066     3236597.338    13880222.962
#Sta/Elev= 30
-9475.12    39.5-1522.15   33.24-1372.04   34.51 -973.52   33.03 1104.46   36.92
 1167.17   34.84    1861   34.59    4883      36    4959    22.5    4998     9.1
    4998     4.4    5030     3.8    5030     9.1    5040      15    5072    25.2
    5172   29.29  5732.9   31.01 6133.31   28.74 6986.68   31.65 8823.91   31.34
 8896.86   34.32  8952.9   31.14 8980.84   25.78 8992.96   25.86 9021.66   32.62
 9095.18   33.9412165.15   36.1512330.12   33.5612421.02   35.9613488.55   36.96
#Mann= 6 ,-1 , 0
-9475.12    .118       0-1522.15    .118       0-1372.04    .068       0
    4883     .04       0    5172    .118       0 6133.31    .068       0
#XS Ineff= 3 ,-1
 8910.2613488.55   36.83-9475.12 -850.82   36.13 -651.46 4882.23   35.87
Permanent Ineff=
       F       F       F
#Block Obstruct= 2 , 0
                        11032.24           35.45
Bank Sta=4883,5172
XS Rating Curve= 0
Exp/Cntr=.3,.1

Type RM Length L Ch R = 1 ,120696.2,954.42,864.39,676.82
XS GIS Cut Line= 6
     3250128.865    13886939.245     3244973.698    13884072.691
     3244819.167     13884003.65     3244601.024    13883916.688
     3242913.582    13882951.851     3236512.052    13879778.212
#Sta/Elev= 30
-1125.82   33.45 -249.48   31.93  -95.49   36.85 1964.58   36.94 2016.17   36.81
2106.39528.77062 2159.84   25.23 2250.65   29.593337.71531.139994569.03529.01004
  4854.5      28  4937.5    31.6  4953.5    21.7  4978.5    13.8  4984.5     7.8
  4984.5       5  5004.5     3.8  5020.5       7  5027.5    16.8  5051.5      19
  5062.5    25.7 5160.58   29.646416.01530.03999 9460.27   31.64 9545.36    35.6
 9627.59    33.1 9661.08   26.08 9694.56   32.85  9763.1   34.1314265.68   37.25
#Mann= 7 ,-1 , 0
-1125.82    .068       02106.395    .118       03337.715    .068       0
4569.035    .118       0  4937.5     .04       0  5062.5    .118       0
6416.015    .068       0
#XS Ineff= 3 ,-1
-1125.82 1881.12    36.6 7765.0214265.68   36.09 2045.77 3037.51   31.87
Permanent Ineff=
       F       F       F
#Block Obstruct= 2 , 0
          -93.47   36.79
Bank Sta=4937.5,5062.5
XS Rating Curve= 0
Exp/Cntr=.3,.1

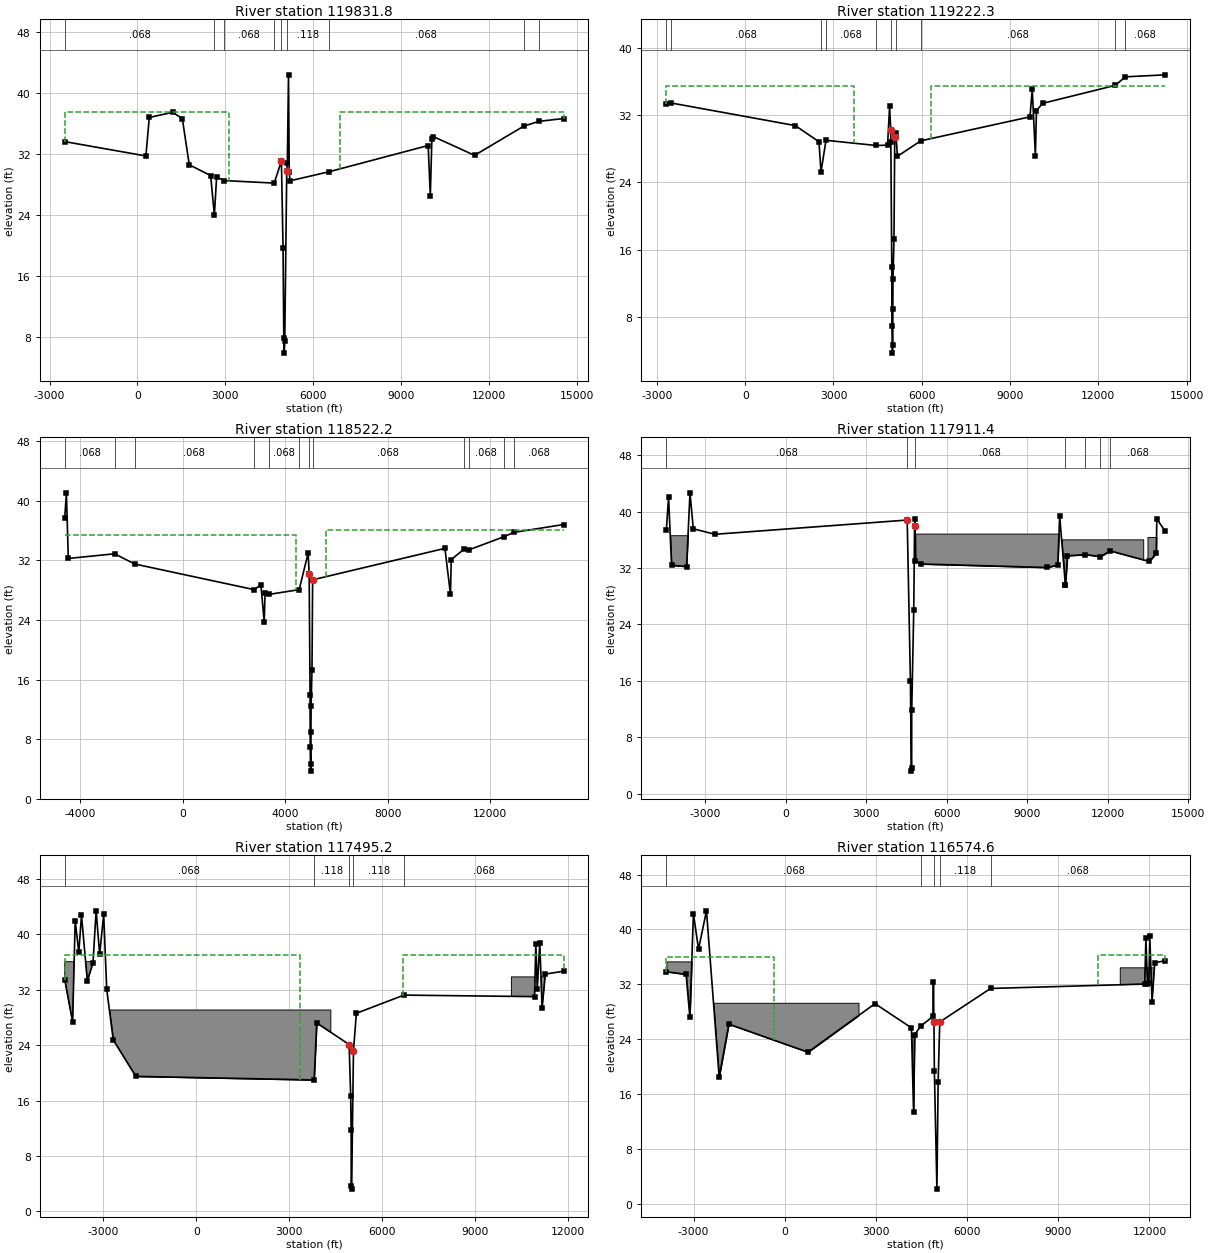
Type RM Length L Ch R = 1 ,119831.8,345.88,609.48,733.53
XS GIS Cut Line= 6
     3252213.308    13886245.634     3245568.108    13883380.295
      3245410.71     13883377.91     3245042.066    13883380.295
     3240405.684    13881448.787     3236837.554    13879154.334
#Sta/Elev= 30
-2483.59   33.64  286.48   31.76  402.89   36.81 1198.07   37.48 1530.26   36.67
 1767.29    30.6 2497.12   29.19 2624.66      24 2701.08   28.99 2965.21   28.53
 4667.97    28.2    4913    31.1    4969    19.7    4994     7.9    5009     5.9
    5027     7.5    5095    29.8    5115    30.8    5155    42.4    5180    29.7
    5205    28.5 6540.99   29.69  9922.8   33.13 9995.87   26.5510049.41   34.02
10094.87   34.3111506.09   31.8413181.72   35.6613692.55   36.2914543.92   36.67
#Mann= 9 ,-1 , 0
-2483.59    .068       0 2624.66    .118       0 2965.21    .068       0
 4667.97    .118       0    4913     .04       0    5095    .118       0
 6540.99    .068       013181.72    .118       013692.55    .068       0
#XS Ineff= 2 , 0
         3108.63    37.5 6903.71            37.5
Permanent Ineff=
       F       F
#Block Obstruct= 2 , 0
        -2483.36   37.43
Bank Sta=4913,5095
XS Rating Curve= 0
Exp/Cntr=.3,.1

Type RM Length L Ch R = 1 ,119222.3,675.1,700.15,567.08
XS GIS Cut Line= 6
     3252551.086    13885317.613     3246903.977    13883662.716
     3245592.019    13882965.738     3245141.033    13882658.248
     3240610.678     13881346.29     3237043.791    13878906.868
#Sta/Elev= 30
-2680.08   33.32-2510.5533.41035 1700.86   30.73 2506.12   28.812575.605 25.2405
2745.14528.980024440.52528.36998  4838.5    28.4  4906.5      33  4946.5    30.2
4949.13528.80885  4981.5    13.9  4986.5     6.9  5001.5     3.7  5016.5     4.7
  5016.5     8.9  5021.5    12.5  5056.5    17.3  5081.5    29.45118.675 29.8487
 5173.16   27.085966.36428.91999 9678.23   31.77 9755.74   35.07 9862.06   27.16
 9898.04   32.5110107.52   33.3712578.35   35.5112917.43   36.5214273.73   36.76
#Mann= 10 ,-1 , 0
-2680.08    .118       0-2510.55    .068       02575.605    .118       0
2745.145    .068       04440.525    .118       04949.135     .04       0
5118.675    .118       05966.364    .068       012578.35    .118       0
12917.43    .068       0
#XS Ineff= 2 , 0
         3707.71   35.43 6304.58           35.43
Permanent Ineff=
       F       F
#Block Obstruct= 2 , 0
        -2679.77   36.65
Bank Sta=4946.5,5081.5
XS Rating Curve= 0
Exp/Cntr=.3,.1

Type RM Length L Ch R = 1 ,118522.2,873.86,610.8,556.62
XS GIS Cut Line= 6
     3255206.212    13884544.188     3246057.691    13882651.128
     3245766.414     13882275.74     3245381.968    13882165.223
     3240743.572    13881215.843     3237108.805    13878557.581
#Sta/Elev= 30
-4601.24   37.69-4536.18   41.09-4462.59   32.27 -2655.7    32.9-1877.49   31.53
2791.81528.08011 3048.65   28.74 3179.04    23.8  3211.9   27.573375.47527.45001
4542.79528.08045  4892.5      334931.90530.22268  4932.5    30.2  4967.5    13.9
  4972.5     6.9  4987.5     3.7  5002.5     4.7  5002.5     8.9  5007.5    12.5
  5042.5    17.3  5067.5    29.410227.33   33.6310443.82   27.4610473.74   32.13
10963.08   33.4911157.63   33.4212519.51   35.1812908.62   35.7714854.15   36.83
#Mann= 12 ,-1 , 0
-4601.24    .068       0 -2655.7    .118       0-1877.49    .068       0
2791.815    .118       03375.475    .068       04542.795    .118       0
4931.905     .04       0  5067.5    .068       010963.08    .118       0
11157.63    .068       012519.51    .118       012908.62    .068       0
#XS Ineff= 2 , 0
         4401.36   35.38 5597.94           36.05
Permanent Ineff=
       F       F
#Block Obstruct= 2 , 0
                        14110.77              38
Bank Sta=4932.5,5067.5
XS Rating Curve= 0
Exp/Cntr=.3,.1

Type RM Length L Ch R = 1 ,117911.4,451.47,416.23,648.01
BEGIN DESCRIPTION:
Agricultural Channel
END DESCRIPTION:
XS GIS Cut Line= 6
     3255206.212    13883826.711     3246534.989    13882084.267
     3245881.295    13881799.069      3245407.49    13881907.614
     3241225.658    13881079.799     3237740.769    13878578.878
#Sta/Elev= 30
-4457.29   37.45-4375.66   42.08-4264.52    32.4-3705.15   32.21-3577.11   42.67
-3452.84   37.56-2642.43   36.79 4521.85   38.81 4641.83      16 4675.83     3.2
 4687.83     3.7 4690.83    11.8 4765.83      26 4797.47   37.92 4814.33   38.99
 4831.01   33.02 5020.69   32.58 9735.34   32.08 10134.8   32.4310206.94   39.35
10421.44 29.590610421.44   29.5910498.75   33.7411165.3833.9095411723.3333.63152
 12095.334.4318213551.76   32.9413807.65   34.0913829.15   38.9514141.12   37.24
#Mann= 7 ,-1 , 0
-4457.29    .068       0 4521.85     .04       0 4797.47    .068       0
10421.44    .118       011165.38    .068       011723.33    .118       0
 12095.3    .068       0
#Block Obstruct= 4 ,-1
-4347.32-3578.09   36.66 4812.1510204.99   36.8910291.3813321.68   36.07
13481.0213923.31   36.41
Bank Sta=4521.85,4797.47
XS Rating Curve= 0
Exp/Cntr=.3,.1

Type RM Length L Ch R = 1 ,117495.2,495.81,920.52,908.92
XS GIS Cut Line= 6
     3255545.438    13883777.851     3251924.391    13882970.987
     3246687.432    13881921.502     3246547.274     13881520.92
     3244957.811    13880688.153     3240352.783    13879271.222
#Sta/Elev= 30
-4242.62   33.48-3988.68   27.37-3905.07   42.01-3788.83    37.4-3702.52   42.77
-3512.75   33.28-3331.38   35.88-3230.15   43.42-3116.47   37.13-2986.23    42.9
-2889.26   32.11-2677.73   24.76-1950.76    19.53801.43518.97998 3884.98   27.22
    4930    24.1    4980    16.7    4995    11.8    4998     3.7    5010     3.2
    5070    23.2 5163.34   28.616697.29531.2399310910.88   31.0210951.23   38.65
10998.31   32.1911078.95    38.811153.76   29.3511257.86   34.2811845.49   34.69
#Mann= 5 ,-1 , 0
-4242.62    .068       03801.435    .118       0    4930     .04       0
    5070    .118       06697.295    .068       0
#XS Ineff= 2 , 0
          3349.8   36.97 6656.76           36.97
Permanent Ineff=
       F       F
#Block Obstruct= 3 ,-1
-4242.62-3272.73   36.07-2892.54 4324.24   29.1610163.9711509.33   33.87
Bank Sta=4930,5070
XS Rating Curve= 0
Exp/Cntr=.3,.1

Type RM Length L Ch R = 1 ,116574.6,715.17,890.36,966.83
XS GIS Cut Line= 6
     3255919.351    13883699.133     3247791.674    13881927.968
     3247552.483    13881729.253     3247443.108    13881244.878
     3246236.985    13880294.561     3240785.735    13878464.358
#Sta/Elev= 30
-3895.18   33.83-3246.58   33.45-3122.79    27.2-3005.01   42.28-2836.96   37.13
-2575.89   42.72-2158.15   18.44-1839.58   26.18  763.88   22.09  2969.5   29.17
 4167.13   25.64 4238.06   13.36 4272.72   24.65 4474.82    25.9    4875    27.3
    4891    32.4    4908    26.5    4922    19.4    5006     2.1    5046    17.7
    5100    26.5 6772.47   31.3911845.05   32.0311881.82   38.7811933.15   32.11
11981.08   32.1812009.54   38.9912084.54   29.4612173.17   35.1412516.59   35.44
#Mann= 5 ,-1 , 0
-3895.18    .068       0 4474.82    .118       0    4908     .04       0
    5100    .118       0 6772.47    .068       0
#XS Ineff= 2 ,-1
10320.8512516.59    36.2-3895.18 -350.97   35.98
Permanent Ineff=
       F       F
#Block Obstruct= 4 ,-1
-3895.18-2930.07   35.34-2362.45  2425.9    29.3 4114.75 4557.38   24.81
11038.3412516.59    34.4
Bank Sta=4908,5100
XS Rating Curve= 0
Exp/Cntr=.3,.1