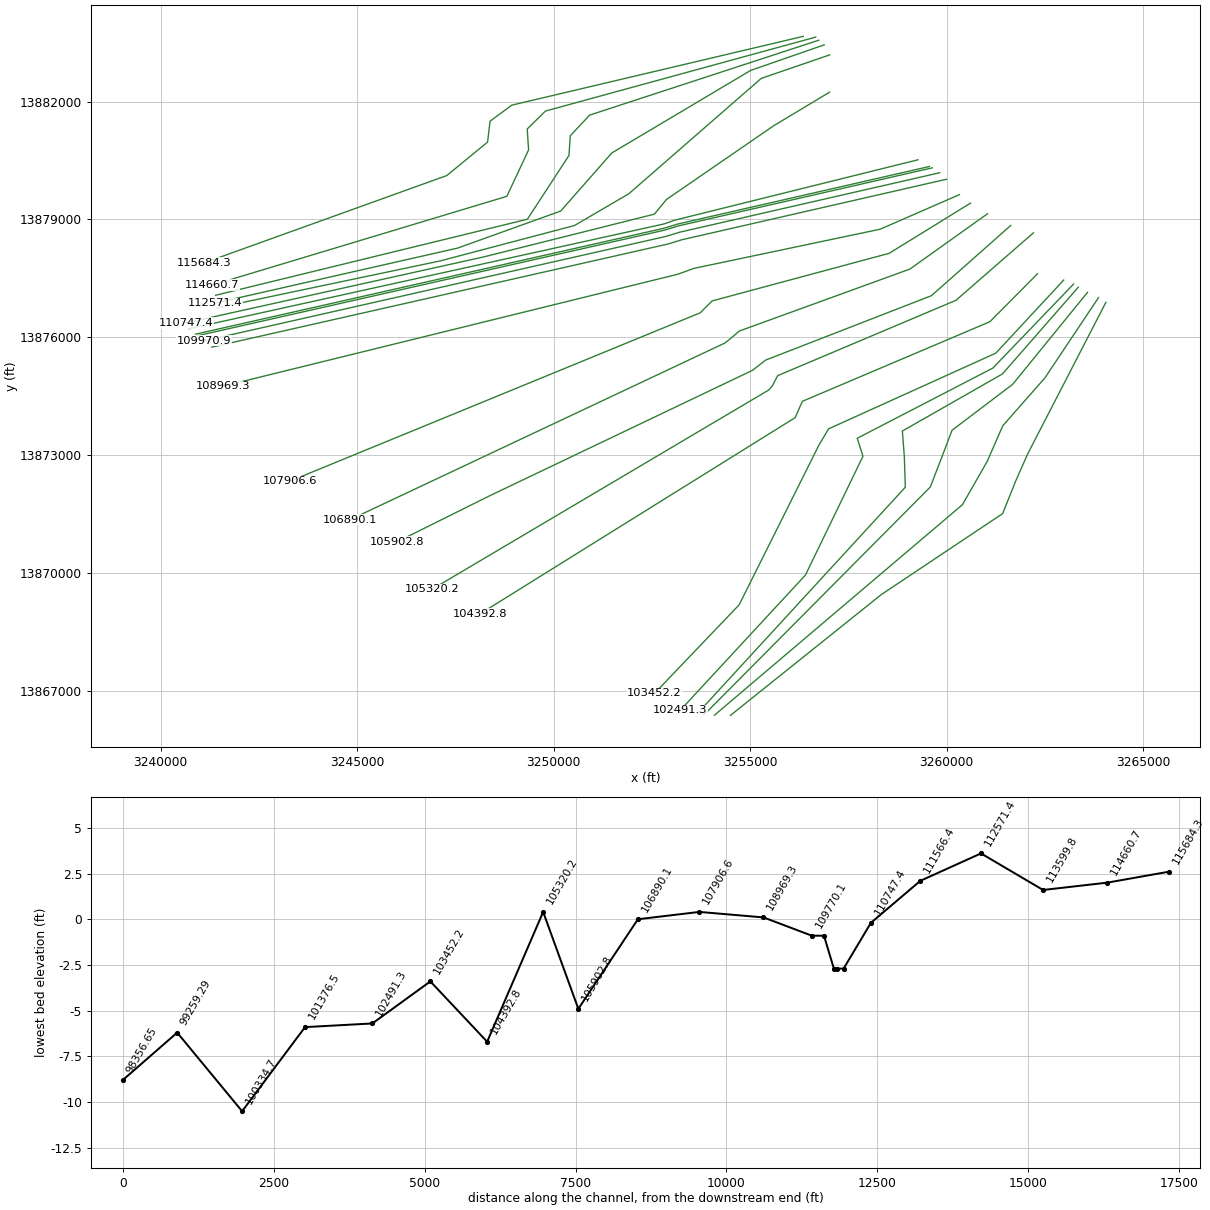
HEC-RAS study Q100-00-00.prj: Q100-00-00

--- Q100-00-00.g01 (geometry) --- (continued)

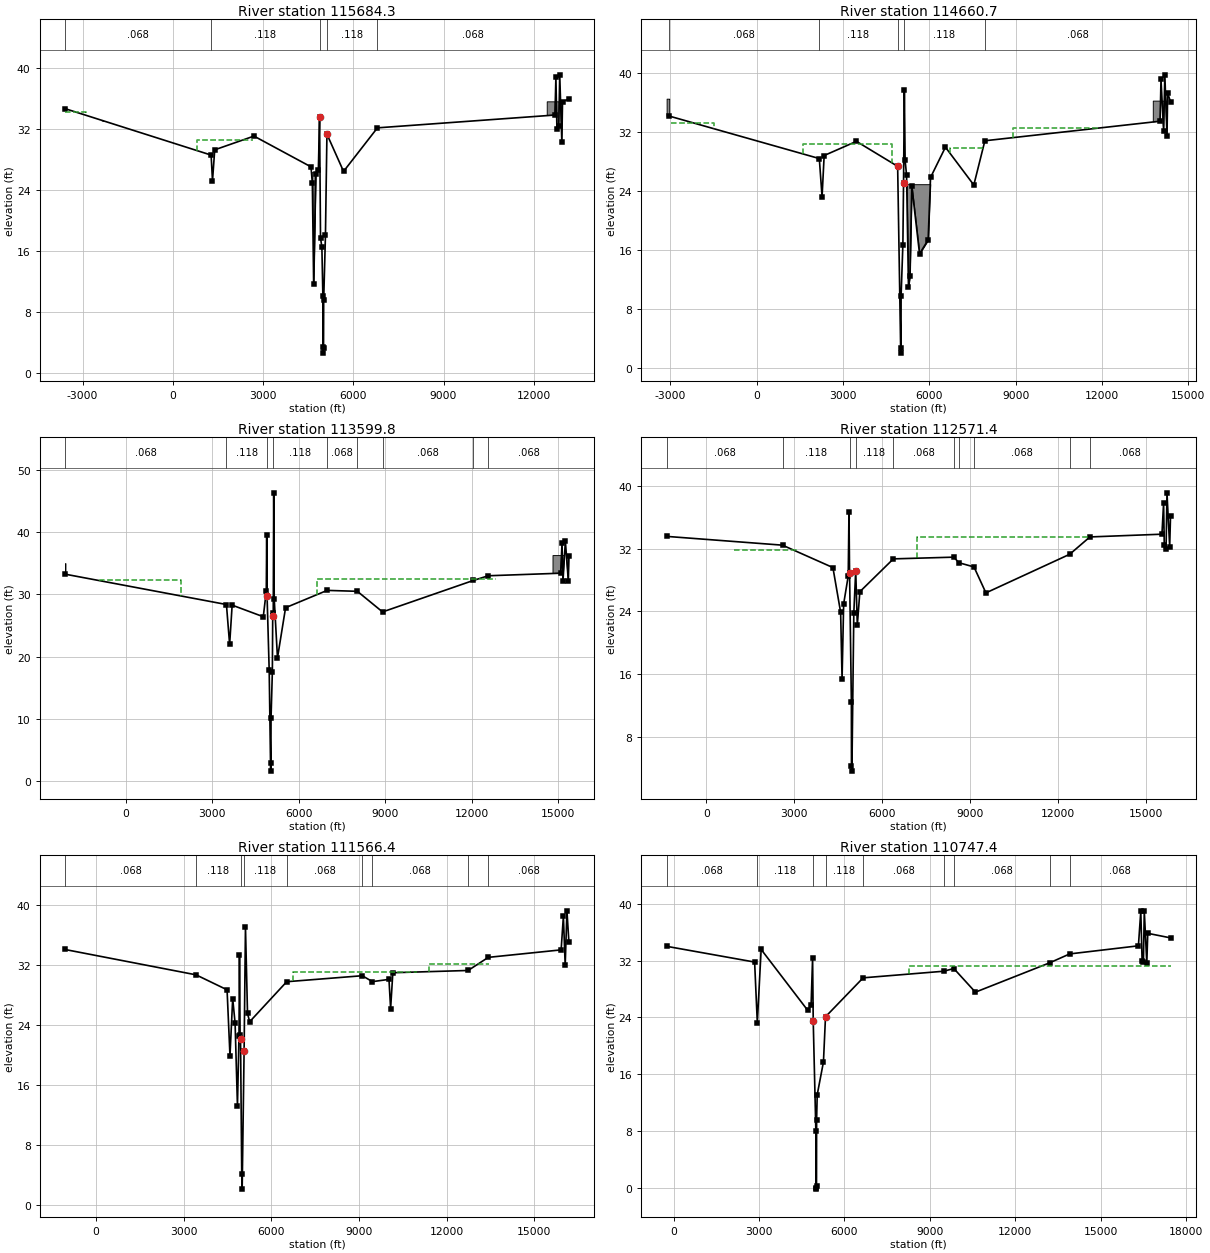
Type RM Length L Ch R = 1 ,115684.3,885.52,1023.62,1174.84
XS GIS Cut Line= 6
     3256352.302    13883659.773     3248933.091    13881908.289
     3248380.608    13881500.086     3248318.108    13880968.836
     3247280.004    13880117.445     3241100.608    13877893.649
#Sta/Elev= 30
-3586.93   34.65 1272.02   28.56 1317.74   25.19 1391.44   29.25 2696.91   31.05
 4591.83   27.02 4637.83   24.91 4680.74    11.7 4750.79   26.07  4837.5    26.6
  4877.5    33.5  4909.5    17.7  4954.5    16.5  4987.5    10.1  4989.5     3.4
  4999.5     2.6  5009.5     3.3  5014.5     9.5  5073.5    18.1  5122.5    31.3
 5675.34   26.42 6801.16   32.1312703.73   33.8112735.61   38.7512769.64   31.99
12831.26   32.3512863.15   39.0812932.68   30.2712955.63   35.5513168.05   35.92
#Mann= 5 ,-1 , 0
-3586.93    .068       0 1272.02    .118       0  4877.5     .04       0
  5122.5    .118       0 6801.16    .068       0
#XS Ineff= 2 ,-1
-3586.93-2893.83   34.21  805.62 2660.42   30.54
Permanent Ineff=
       F       F
#Block Obstruct= 3 ,-1
-3586.93-2308.96   33.14 4451.99  4810.3   26.3212447.5513168.05   35.54
Bank Sta=4877.5,5122.5
XS Rating Curve= 0
Exp/Cntr=.3,.1

Type RM Length L Ch R = 1 ,114660.7,1071.17,1060.85,964.42
XS GIS Cut Line= 6
     3256667.176    13883640.094     3249791.108    13881758.864
     3249326.503    13881301.586     3249361.927     13880770.23
      3248808.44    13879589.218      3241315.17    13877331.659
#Sta/Elev= 30
-3059.09   34.122174.085   28.35 2269.48   23.17 2342.32   28.76 3464.85   30.68
  4897.5    27.3  5004.5       2  5014.5     2.7  5017.5     9.8  5079.5    16.7
  5102.5    25.1  5130.5    37.7  5157.5    28.1  5207.5    26.1 5274.17    10.9
 5323.86   12.46 5388.74   24.61 5658.51   15.46 5957.73   17.33 6041.41   25.79
 6558.86   29.89 7545.74   24.777930.575   30.76   14023   33.41 14053.3   39.08
14145.07   32.1114186.89   39.6914262.29   31.4314285.23   37.2214384.82   36.03
#Mann= 5 ,-1 , 0
-3059.09    .068       02174.085    .118       0  4897.5     .04       0
  5102.5    .118       07930.575    .068       0
#XS Ineff= 4 ,-1
-2992.26-1503.52   33.23 8903.9811901.64   32.49 1608.49 4699.82   30.31
 6702.58 7873.54   29.82
Permanent Ineff=
       F       F       F       F
#Block Obstruct= 3 ,-1
-3135.38-3044.37   36.46 5180.33  6117.1   24.8813785.5514384.82   36.13
Bank Sta=4897.5,5102.5
XS Rating Curve= 0
Exp/Cntr=.3,.1

Type RM Length L Ch R = 1 ,113599.8,1286.07,1028.39,776.57
XS GIS Cut Line= 6
     3256745.894    13883561.375     3250916.658    13881656.282
     3250422.274    13881130.295     3250389.216    13880628.535
     3249331.348    13879005.974     3241398.131    13877070.923
#Sta/Elev= 30
-2097.56   33.23  3489.7   28.36 3600.56   21.94 3687.56   28.26 4766.88    26.4
    4871    30.5    4886    39.5    4898    29.8    4972    17.8    5022     1.6
    5032     2.9    5036    10.1    5082    17.6    5094    26.5    5113      27
    5129    46.3    5146    29.3 5259.36   19.79 5540.05   27.85 6981.73   30.63
 8029.34   30.48 8902.35   27.1712045.18   32.2212568.99   32.98 15078.4   33.39
15123.96   38.25 15157.4   32.1615240.42   38.5115342.68   32.1515362.62   36.19
#Mann= 9 ,-1 , 0
-2097.56    .068       0  3489.7    .118       0    4898     .04       0
    5094    .118       0 6981.73    .068       0 8029.34    .118       0
 8902.35    .068       012045.18    .118       012568.99    .068       0
#XS Ineff= 4 ,-1
 6632.3212838.41   32.39 -885.25 1901.64   32.26 5137.53 5883.45   27.57
 2433.57 3972.03   27.27
Permanent Ineff=
       F       F       F       F
#Block Obstruct= 2 ,-1
 -2107.4-2090.94      3514811.1915362.62   36.22
Bank Sta=4898,5094
XS Rating Curve= 0
Exp/Cntr=.3,.1

Type RM Length L Ch R = 1 ,112571.4,945.12,1005.01,871.04
XS GIS Cut Line= 6
     3256883.651    13883443.298     3255014.089    13882793.871
     3251479.566    13880692.795     3250180.043    13879215.018
     3247555.255    13878271.734     3241374.428    13876869.445
#Sta/Elev= 30
-1359.36   33.562593.75532.44001 4313.14   29.58 4576.51   23.87 4625.23   15.32
 4679.36   24.94    4835    28.5    4861    36.7    4881    28.9    4943    12.4
    4946     4.2    4961     3.6    5026    23.8    5091    29.2    5145    22.2
 5231.84    26.56374.995   30.698437.49530.910038609.36530.200029124.98529.65999
 9531.42   26.3512390.61   31.2813078.11   33.4915535.56   33.8415592.23   37.86
15614.74   32.4215676.27   31.9615707.03   39.1215799.31   32.25 15828.1   36.15
#Mann= 10 ,-1 , 0
-1359.36    .068       02593.755    .118       0    4881     .04       0
    5091    .118       06374.995    .068       08437.495    .068       0
8609.365    .118       09124.985    .068       012390.61    .118       0
13078.11    .068       0
#XS Ineff= 4 ,-1
 7168.6213007.03   33.52  950.82 3037.47   31.88 4252.99 4840.51   28.76
    5089 6305.79   28.48
Permanent Ineff=
       F       F       F       F
#Block Obstruct= 2 , 0
                        15139.86           36.48
Bank Sta=4881,5091
XS Rating Curve= 0
Exp/Cntr=.3,.1

Type RM Length L Ch R = 1 ,111566.4,836.4,819.03,675.27
XS GIS Cut Line= 6
     3257021.409    13883187.463     3255281.016    13882589.642
     3251912.438    13879654.381     3250528.648    13878845.907
     3247104.119    13877943.636     3241433.686    13876750.929
#Sta/Elev= 30
-1063.27   34.083421.65530.70002 4484.94    28.7 4584.79   19.88 4677.39   27.52
 4759.42   24.28 4840.44   13.21    4893    22.5    4910    33.4    4931    22.7
    4946    22.1    4987     4.1    5002     2.1    5068    20.6  5114.8   37.12
 5184.81   25.54 5258.67   24.446526.60529.779979114.05530.580069459.04529.79003
10027.32   30.0910083.36   26.1810159.33   30.98 12736.5   31.2813426.48   33.03
15920.56   34.0315997.67   38.5216059.35   31.9616119.25   39.2416186.44   35.07
#Mann= 9 ,-1 , 0
-1063.27    .068       03421.655    .118       0    4946     .04       0
    5068    .118       06526.605    .068       09114.055    .118       0
9459.045    .068       0 12736.5    .118       013426.48    .068       0
#XS Ineff= 4 ,-1
11380.6213441.51   32.17  903.98 2660.42   31.16 6735.3610974.24   31.05
 4498.69 4903.92    22.2
Permanent Ineff=
       F       F       F       F
#Block Obstruct= 2 , 0
          110.01   33.2415701.71           36.15
Bank Sta=4946,5068
XS Rating Curve= 0
Exp/Cntr=.3,.1

Type RM Length L Ch R = 1 ,110747.4,773.03,451.34,321.97
XS GIS Cut Line= 6
     3257018.603    13882238.241     3255594.084    13881381.831
     3252869.176    13879508.163     3252562.948    13879135.489
     3248226.324    13878048.743     3240638.217    13876366.843
#Sta/Elev= 30
 -246.42   34.01 2844.14   31.79 2938.59   23.24 3073.01   33.57 4706.45      25
    4827    25.7    4880    32.4    4902    23.5    4994       8    4997       0
    5007     -.2    5017      .2    5021     9.6    5042    13.1 5261.03   17.72
 5333.14   24.08 6654.44   29.57 9485.56    30.5 9839.45   30.8810596.47   27.55
13201.41   31.6813909.19   32.9416320.41   34.0816404.08   38.9516450.17   31.97
16496.26   31.8516526.99   39.01   16615   31.6316648.72   35.84 17448.1    35.2
#Mann= 9 ,-1 , 0
 -246.42    .068       0 2938.59    .118       0    4902     .04       0
 5333.14    .118       0 6654.44    .068       0 9485.56    .118       0
 9839.45    .068       013201.41    .118       013909.19    .068       0
#XS Ineff= 2 , 0
         3072.43   33.21 8261.12           31.26
Permanent Ineff=
       F       F
#Block Obstruct= 2 , 0
                        16232.91           35.84
Bank Sta=4902,5333.14
XS Rating Curve= 0
Exp/Cntr=.3,.1

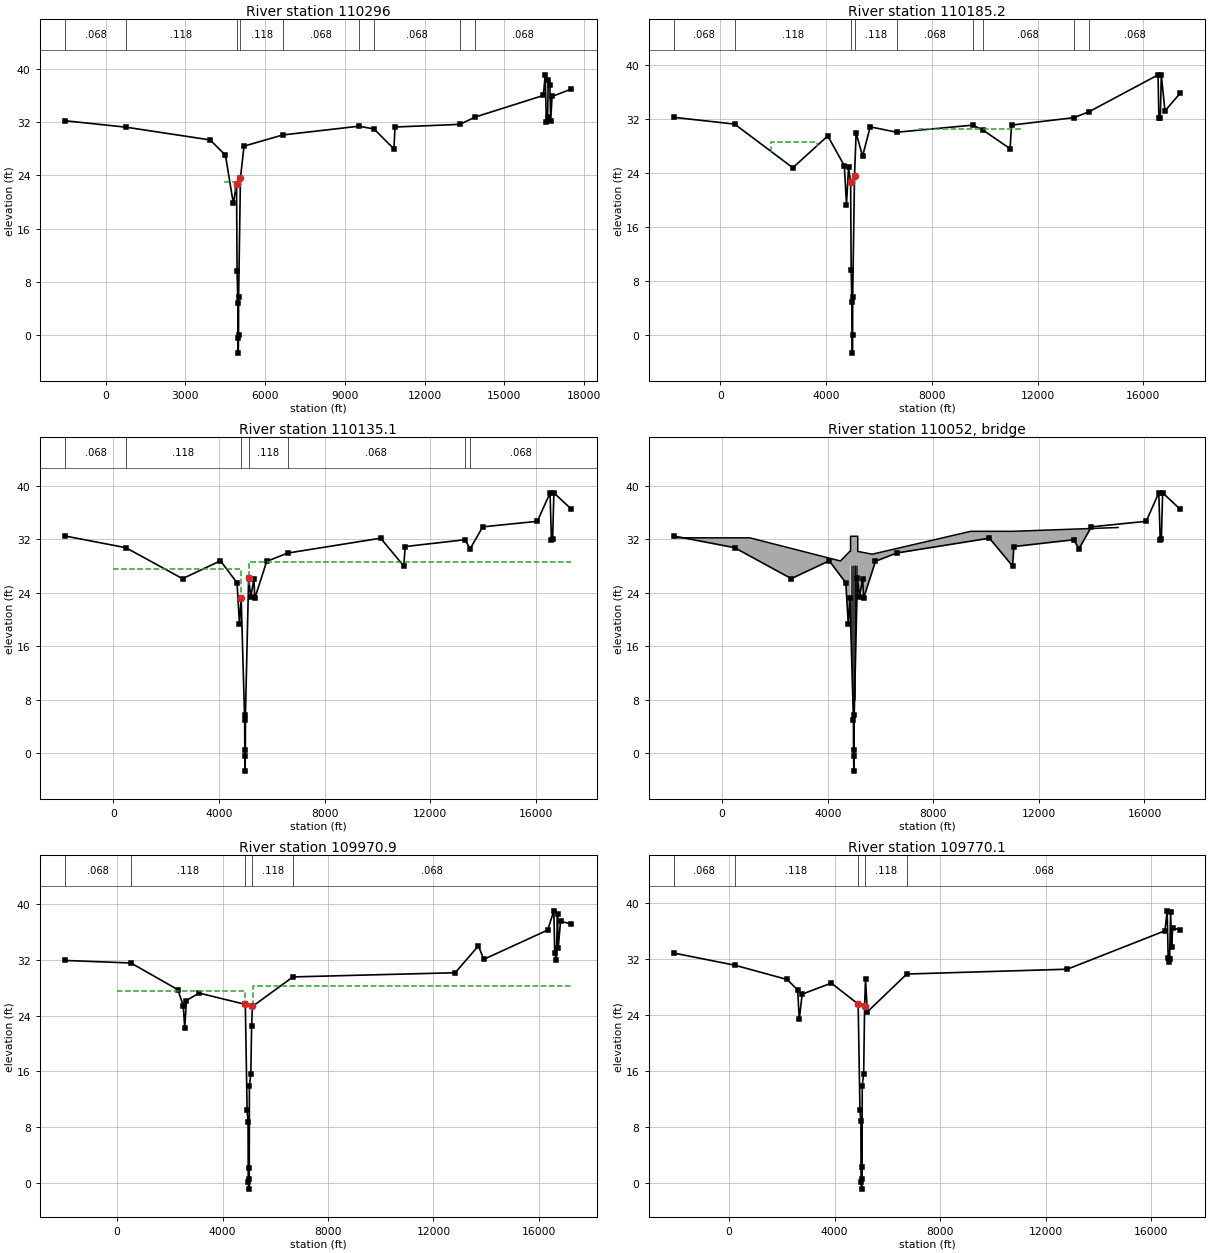
Type RM Length L Ch R = 1 ,110296  ,125.92,110.86,111.74
XS GIS Cut Line= 6
     3259271.326    13880519.372     3253069.642    13878979.331
     3253013.259    13878957.972     3252874.268    13878910.113
     3252791.278    13878882.449     3240720.857    13876219.066
#Sta/Elev= 30
-1523.11    32.2  762.36   31.24 3935.37   29.32 4509.64   27.02 4806.05   19.79
  4926.5    22.7  4946.5     9.7  4975.5     4.9  4979.5     -.4  4991.5    -2.7
  5001.5       0  5004.5     5.7  5073.5    23.6 5208.17   28.39 6666.49   30.07
 9523.32   31.3810094.69   30.9810848.87   27.9710887.93   31.2613332.44   31.66
13903.81   32.7616468.98      3616540.49    39.116582.17   31.9716631.05   32.75
 16653.2   38.3516714.65   37.5616745.37   32.1716796.51   35.8517522.47   36.96
#Mann= 9 ,-1 , 0
-1523.11    .068       0  762.36    .118       0  4926.5     .04       0
  5073.5    .118       0 6666.49    .068       0 9523.32    .118       0
10094.69    .068       013332.44    .118       013903.81    .068       0
#XS Ineff= 2 ,-1
 8600.2411350.86   30.84 4440.56 4877.62   22.99
Permanent Ineff=
       F       F
#Block Obstruct= 2 , 0
         -1136.1   32.5216363.08           35.96
Bank Sta=4926.5,5073.5
XS Rating Curve= 0
Exp/Cntr=.3,.1

Type RM Length L Ch R = 1 ,110185.2,50.99,50.09,50.96
XS GIS Cut Line= 6
     3259561.093    13880348.076      3253151.59    13878882.815
     3253090.256     13878863.17     3252836.942    13878785.724
     3252775.096    13878769.165     3240890.709    13876082.356
#Sta/Elev= 30
-1760.83   32.29 537.47531.28999 2739.57   24.81  4060.9   29.53 4687.73   25.12
 4769.81   19.32 4846.68   24.86  4926.5    22.7  4946.5     9.7  4975.5     4.9
  4991.5    -2.7  5001.5       0  5004.5     5.7  5073.5    23.6 5134.07   29.97
  5377.4   26.52 5668.52   30.886666.265   30.089539.135 31.13019922.19530.43001
10959.53   27.6411012.92   31.1413369.64   32.2413944.22   33.1216557.18   38.59
16587.89   32.1716642.54   32.1216680.16    38.616818.56   33.2417391.66   35.86
#Mann= 9 ,-1 , 0
-1760.83    .068       0 537.475    .118       0  4926.5     .04       0
  5073.5    .118       06666.265    .068       09539.135    .118       0
9922.195    .068       013369.64    .118       013944.22    .068       0
#XS Ineff= 3 ,-1
 7528.7211393.93   30.56  1931.3 3654.97   28.69  4469.7 4848.48   24.31
Permanent Ineff=
       F       F       F
#Block Obstruct= 2 , 0
                        13729.71           32.59
Bank Sta=4926.5,5073.5
XS Rating Curve= 0
Exp/Cntr=.5,.3

Type RM Length L Ch R = 1 ,110135.1,166.6,164.18,166.51
XS GIS Cut Line= 6
     3259632.983    13880313.221     3253164.811    13878834.548
     3253105.192    13878815.451     3252850.721    13878737.652
      3252787.08    13878720.612     3240940.432    13876042.335
#Sta/Elev= 30
-1826.39   32.48  474.64   30.73  2621.7    26.1 4059.02   28.77 4685.84   25.48
 4777.98   19.35 4842.42   23.14  4975.5     4.9  4979.5     -.4  4991.5    -2.7
  5001.5      .4  5004.5     5.7 5125.76   26.25 5205.22   23.35 5326.18   26.11
 5357.21   23.13 5810.42   28.69 6610.72   29.9310125.38   32.1511003.06   27.99
11054.48    30.913322.06   31.9213513.81   30.5513991.62   33.8516062.29   34.68
16541.85   38.9316596.06   31.8416640.29      3216686.93   38.9417348.86    36.5
#Mann= 7 ,-1 , 0
-1826.39    .068       0  474.64    .118       0 4842.42     .04       0
 5125.76    .118       0 6610.72    .068       013322.06    .118       0
13513.81    .068       0
#XS Ineff= 2 , 0
       0    4844   27.57    5156       0   28.59
Permanent Ineff=
       F       F
#Block Obstruct= 2 , 0
                        16393.64           35.34
Bank Sta=4842.42,5125.76
XS Rating Curve= 0
Exp/Cntr=.5,.3

Type RM Length L Ch R = 3 ,110052  ,,,
BEGIN DESCRIPTION:
FM 1942 - Crosby Barbers Hill Road
END DESCRIPTION:
Bridge Culvert--1,0,-1,-1, 0
Deck Dist Width WeirC Skew NumUp NumDn MinLoCord MaxHiCord MaxSubmerge Is_Ogee
60,45,2.6,0, 22, 22, , , .95, 0, 0,0,,
   -1825     250    1048    4483    4836 4865.99    4866    4896  4926.4  4956.8
  4987.2  5017.6    5048  5078.4  5108.8  5138.8 5138.81    5166    5689    9416
   11000   15000
   32.21   32.21   32.21   28.74   30.18   30.18   32.44   32.44   32.44   32.44
   32.44   32.44   32.44   32.44   32.44   32.44   30.15   30.15   29.76   33.18
   33.18   33.75
       0       0       0       0       0       0   28.09   28.09   28.09   28.09
   28.09   28.09   28.09   28.09   28.09   28.09       0       0       0       0
       0       0
    -400     250    1048    4483    4836 4865.99    4866    4896  4926.4  4956.8
  4987.2  5017.6    5048  5078.4  5108.8  5138.8 5138.81    5166    5689    9416
   11000   15000
   32.21   32.21   32.21   28.74   30.18   30.18   32.44   32.44   32.44   32.44
   32.44   32.44   32.44   32.44   32.44   32.44   30.15   30.15   29.76   33.18
   33.18   33.75
       0       0       0       0       0       0   28.09   28.09   28.09   28.09
   28.09   28.09   28.09   28.09   28.09   28.09       0       0       0       0
       0       0
Pier Skew, UpSta & Num, DnSta & Num=  ,4896, 2 ,4896, 2 , 0 , 0 , 0 ,,
    1.35    1.35
       0   30.19
    1.35    1.35
       0   30.19
Pier Skew, UpSta & Num, DnSta & Num=  ,4926.4, 2 ,4926.4, 2 , 0 , 0 , 0 ,,
    1.35    1.35
       0   30.19
    1.35    1.35
       0   30.19
Pier Skew, UpSta & Num, DnSta & Num=  ,4956.8, 2 ,4956.8, 2 , 0 , 0 , 0 ,,
    1.35    1.35
       0   30.19
    1.35    1.35
       0   30.19
Pier Skew, UpSta & Num, DnSta & Num=  ,4987.2, 2 ,4987.2, 2 , 0 , 0 , 0 ,,
    1.35    1.35
       0   30.19
    1.35    1.35
       0   30.19
Pier Skew, UpSta & Num, DnSta & Num=  ,5017.6, 2 ,5017.6, 2 , 0 , 0 , 0 ,,
    1.35    1.35
       0   30.19
    1.35    1.35
       0   30.19
Pier Skew, UpSta & Num, DnSta & Num=  ,5048, 2 ,5048, 2 , 0 , 0 , 0 ,,
    1.35    1.35
       0   30.19
    1.35    1.35
       0   30.19
Pier Skew, UpSta & Num, DnSta & Num=  ,5078.4, 2 ,5078.4, 2 , 0 , 0 , 0 ,,
    1.35    1.35
       0   30.19
    1.35    1.35
       0   30.19
Pier Skew, UpSta & Num, DnSta & Num=  ,5108.8, 2 ,5108.8, 2 , 0 , 0 , 0 ,,
    1.35    1.35
       0   30.19
    1.35    1.35
       0   30.19
BR Coef=-1 , 1 , 1 ,.9, 0 ,,,.8,0,2,0,
WSPro=,,,, 1 ,,,, 0 ,,,, 0 ,,,,-1 ,-1 ,-1 , 0 , 0 , 0 , 0 , 0
BC Design=,, 0 ,, 0 ,,,,,,
BC HTab HWMax=32.15

Type RM Length L Ch R = 1 ,109970.9,203.96,200.82,203.85
XS GIS Cut Line= 6
     3259821.911    13880188.832     3253206.095    13878676.406
     3253150.589    13878658.627     3252893.343    13878579.979
     3252825.391    13878561.785     3241102.891    13875911.575
#Sta/Elev= 30
 -1970.5    31.9 525.82531.54003 2304.83   27.71 2511.41   25.43 2566.65   22.16
 2630.88   26.14 3104.34   27.23  4865.5    25.6  4933.5    10.4  4968.5     8.8
  4976.5      .1  4995.5     -.9  5013.5      .5  5015.5     2.2  5019.5    13.9
  5073.5    15.6  5104.5    22.5  5134.5    25.36670.61529.53996 12825.3   30.14
13709.28      3413908.35   32.0616335.18   36.2616568.84   39.0216602.02   32.95
16661.11   31.9816707.25   38.6316736.24   33.6916821.17   37.5117231.97   37.15
#Mann= 5 ,-1 , 0
 -1970.5    .068       0 525.825    .118       0  4865.5     .04       0
  5134.5    .118       06670.615    .068       0
#XS Ineff= 2 , 0
       0    4844    27.5    5162       0   28.25
Permanent Ineff=
       F       F
#Block Obstruct= 2 , 0
         -504.46   32.38
Bank Sta=4865.5,5134.5
XS Rating Curve= 0
Exp/Cntr=.5,.3

Type RM Length L Ch R = 1 ,109770.1,797.76,800.75,820.2
XS GIS Cut Line= 6
     3259995.433     13880023.34      3253258.98    13878483.336
     3253210.333    13878467.754     3252948.461    13878387.692
     3252873.325    13878367.575     3241301.781    13875751.493
#Sta/Elev= 30
-2085.73    32.9 215.45531.16996 2203.72   29.12 2603.39   27.63 2664.96   23.41
 2774.37   27.02 3878.99    28.6  4895.5    25.6  4963.5    10.4  4998.5     8.8
  5006.5      .1  5025.5     -.9  5043.5      .5  5045.5     2.2  5049.5    13.9
  5103.5    15.6    5140    25.3 5174.04   29.14 5243.59   24.486735.47529.89999
 12816.2   30.59 16516.5   36.0916600.82   38.9516638.48   32.1816668.42   31.68
16693.09   32.0816731.39   38.7316767.85   33.8416809.46   36.5217090.81   36.19
#Mann= 5 ,-1 , 0
-2085.73    .068       0 215.455    .118       0  4895.5     .04       0
    5140    .118       06735.475    .068       0
#Block Obstruct= 2 , 0
        -1575.78   33.0116585.76           36.77
Bank Sta=4895.5,5140
XS Rating Curve= 0
Exp/Cntr=.3,.1

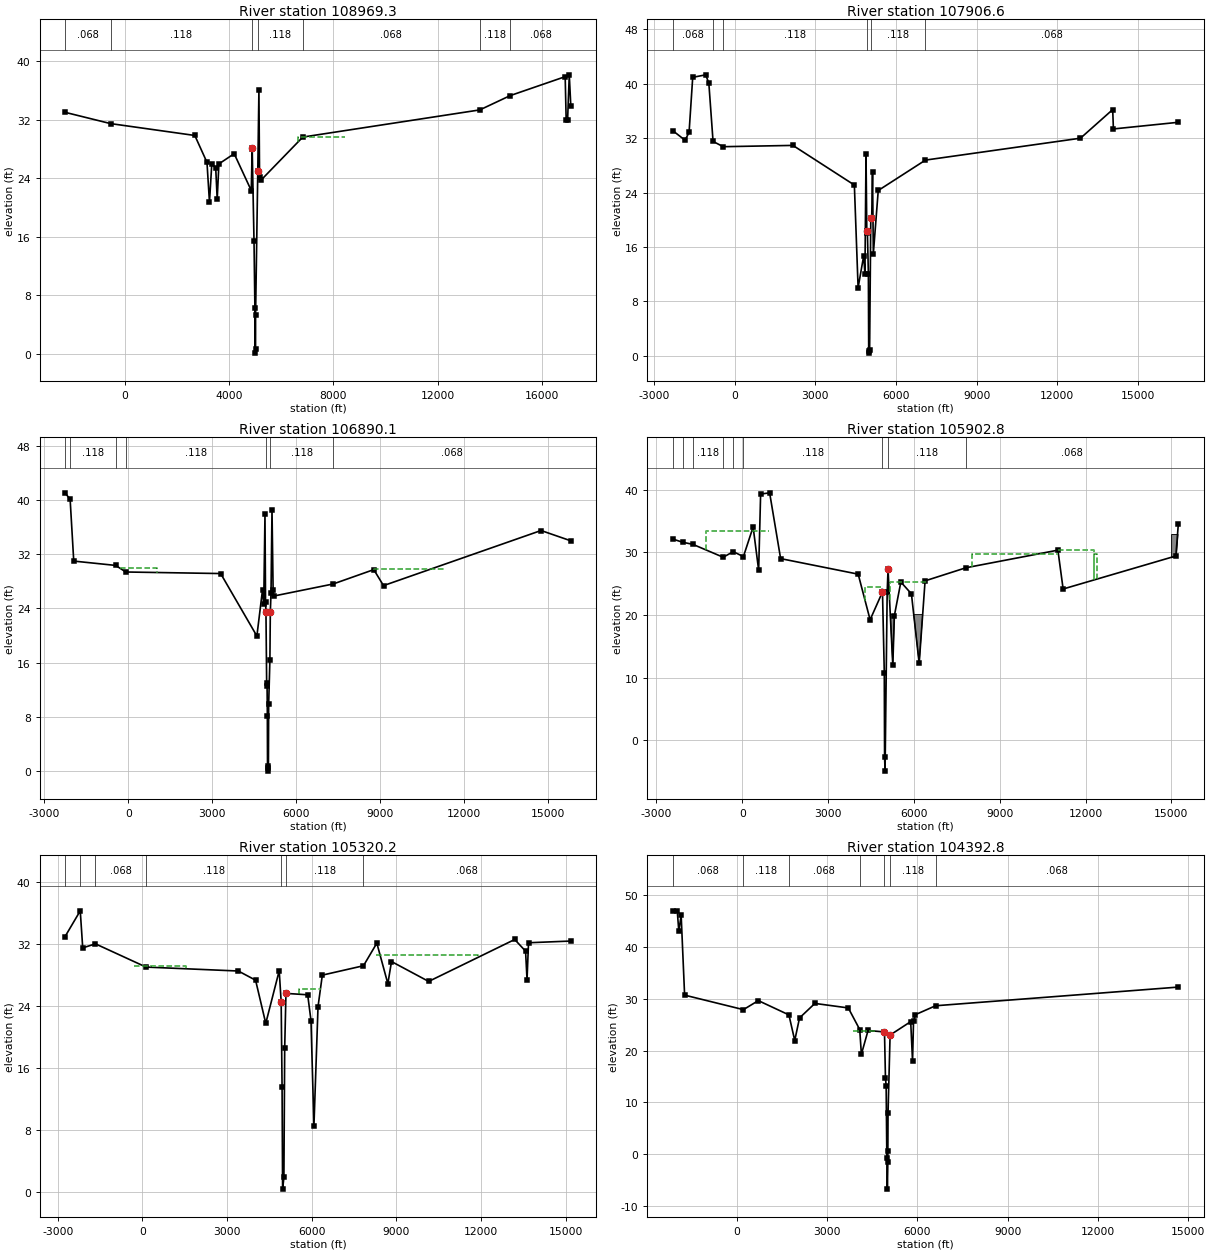
Type RM Length L Ch R = 1 ,108969.3,948.77,1062.75,1197.85
XS GIS Cut Line= 6
     3260325.325    13879632.124     3258306.352    13878751.874
     3253568.108    13877755.295     3253244.956     13877637.53
     3253113.327    13877595.551     3241594.033    13874758.968
#Sta/Elev= 30
-2280.93   32.98-535.82531.43992 2692.58   29.82 3159.12   26.15 3254.68    20.7
 3343.43   25.91 3494.24   25.39 3550.96   21.11 3616.69   25.94 4202.55   27.33
  4857.5    22.3  4892.5    28.14893.35527.92687  4962.5    15.4  4996.5     6.3
  5001.5      .1  5021.5      .7  5022.5     5.3  5107.5      25  5150.5      36
  5175.5    24.2  5225.5    23.76832.34529.5999913618.83   33.3114782.23   35.26
16892.14   37.8516930.35    31.916983.97   31.8717049.21    38.117109.03   33.78
#Mann= 7 ,-1 , 0
-2280.93    .068       0-535.825    .118       04893.355     .04       0
  5107.5    .118       06832.345    .068       013618.83    .118       0
14782.23    .068       0
#XS Ineff= 2 ,-1
 6645.98 8460.97   29.66 2519.98 4197.25    27.3
Permanent Ineff=
       F       F
#Block Obstruct= 2 , 0
                        10337.74           31.94
Bank Sta=4892.5,5107.5
XS Rating Curve= 0
Exp/Cntr=.3,.1

Type RM Length L Ch R = 1 ,107906.6,980.53,1016.53,1018.12
XS GIS Cut Line= 6
     3260604.604    13879414.907     3258538.725    13878139.446
     3254031.649     13876927.17     3253925.145    13876820.355
     3253729.566    13876625.086     3243291.153    13872341.051
#Sta/Elev= 30
-2306.01   33.14-1843.07   31.71-1693.12   32.87-1558.03   40.96-1075.95   41.33
 -958.41   40.11 -801.55   31.54 -425.44   30.76 2168.45   30.95  4452.8   25.12
 4591.99   10.02 4799.92   14.72    4846      12    4886    29.7    4916      18
    4936    18.4    4974    12.1    4986      .7    5006      .4    5020      .9
    5064    20.3    5098    20.3    5128    27.1    5158      15 5340.52   24.32
 7096.84   28.7912860.95   32.0114058.64   36.2214084.68   33.3716499.68   34.35
#Mann= 6 ,-1 , 0
-2306.01    .068       0 -801.55    .068       0 -425.44    .118       0
    4936     .04       0    5064    .118       0 7096.84    .068       0
#Block Obstruct= 2 , 0
         4886.08   17.74 5124.04           17.86
Bank Sta=4936,5064
XS Rating Curve= 0
Exp/Cntr=.3,.1

Type RM Length L Ch R = 1 ,106890.1,984.65,987.26,970.66
XS GIS Cut Line= 6
     3261039.038    13879145.972     3259063.969    13877737.658
     3254724.358    13876161.545     3254500.258    13875969.719
     3254363.327     13875859.44     3244807.756    13871355.908
#Sta/Elev= 30
-2257.99   41.06-2077.22   40.09-1948.35   30.99 -450.27   30.35  -88.73   29.38
 3302.44   29.15 4597.54   19.93 4799.79   26.78    4842    24.6    4887    37.9
    4907      25    4922    23.5    4947      13    4962    12.5    4972     8.2
    4978      .4    4994       0    5010      .8    5019     9.9    5063    16.4
    5078    23.5    5103    26.3    5138    38.6    5178    26.7 5209.03   25.84
 7322.92   27.61 8775.73   29.73 9124.17   27.3714754.43    35.515819.19   33.98
#Mann= 7 ,-1 , 0
-2257.99    .068       0-2077.22    .118       0 -450.27    .068       0
  -88.73    .118       0    4922     .04       0    5078    .118       0
 7322.92    .068       0
#XS Ineff= 3 ,-1
 -250.14 1033.23   30.03 8788.0611305.62   29.82 3974.36 4848.48   23.75
Permanent Ineff=
       F       F       F
#Block Obstruct= 2 , 0
        -1682.98   31.72
Bank Sta=4922,5078
XS Rating Curve= 0
Exp/Cntr=.3,.1

Type RM Length L Ch R = 1 ,105902.8,486.85,582.59,704.89
XS GIS Cut Line= 6
     3261629.999    13878847.503     3259611.736    13877060.434
     3255393.766    13875421.703     3255059.567    13875161.771
     3248373.744    13871970.551     3246021.137    13870800.406
#Sta/Elev= 30
-2434.51   32.15-2080.91   31.63 -1727.3    31.3 -666.49   29.24 -312.89   30.13
   40.71   29.34  380.73   34.07  573.83   27.18  642.88   39.32  957.82   39.52
 1341.98   29.02 4053.45   26.54 4470.13   19.26    4903    23.7    4966    10.8
    4976    -2.6    4993    -4.9    5067    23.7    5097    27.3 5263.61   11.99
 5318.18   19.91 5544.84   25.28 5914.42    23.4 6185.25    12.3 6392.06   25.47
 7819.99   27.5611035.01   30.3711217.96   24.1715157.91   29.4415245.66   34.58
#Mann= 9 ,-1 , 0
-2434.51    .118       0-2080.91    .068       0 -1727.3    .118       0
 -666.49    .118       0 -312.89    .068       0   40.71    .118       0
    4903     .04       0    5097    .118       0 7819.99    .068       0
#XS Ineff= 6 ,-1
-1279.15  951.97   33.4411035.0812282.53   30.36 8026.9311035.08   29.72
12282.5312388.76   29.72 5150.93 6444.12   25.28 4294.87 4889.85   24.54
Permanent Ineff=
       F       F       F       F       F       F
#Block Obstruct= 3 ,-1
-2434.51    3.86   20.78 5158.08 6387.59   20.0814992.1815245.66   32.94
Bank Sta=4903,5097
XS Rating Curve= 0
Exp/Cntr=.3,.1

Type RM Length L Ch R = 1 ,105320.2,885.38,927.42,983.44
XS GIS Cut Line= 6
     3262207.969    13878660.513     3260238.454     13876944.19
     3255700.133    13875026.106      3255565.44    13874767.265
     3255474.438    13874661.523     3246908.831    13869592.561
#Sta/Elev= 30
-2743.26   32.92-2205.53   36.23 -2118.1   31.46-1667.81   31.98  124.61   28.99
  3397.4   28.48 4008.13    27.3 4368.92   21.74 4845.78   28.52    4915    24.5
    4947    13.5    4966      .4    5012     1.9    5040    18.6    5085    25.6
 5855.02   25.42 5971.78   22.11 6076.18    8.52 6221.05   23.89 6373.62   27.95
 7832.02   29.16 8305.66   32.07 8696.07   26.85    8825    29.710142.74   27.14
13191.66   32.54 13576.4   31.0413628.69   27.3713680.98   32.1215180.95   32.34
#Mann= 7 ,-1 , 0
-2743.26    .068       0-2205.53    .118       0-1667.81    .068       0
  124.61    .118       0    4915     .04       0    5085    .118       0
 7832.02    .068       0
#XS Ineff= 3 ,-1
 8286.3611892.72   30.57  -293.4 1540.34   29.07 5534.64 6341.22   26.15
Permanent Ineff=
       F       F       F
#Block Obstruct= 2 , 0
                         11847.7           30.69
Bank Sta=4915,5085
XS Rating Curve= 0
Exp/Cntr=.3,.1

Type RM Length L Ch R = 1 ,104392.8,999.21,940.58,1168.95
XS GIS Cut Line= 6
     3262312.238     13877618.61     3261099.036    13876397.958
     3256333.733    13874375.086     3256273.283    13874251.536
     3256146.233     13873958.42     3248121.226      13868961.4
#Sta/Elev= 30
-2135.23   46.95-1979.16   46.86-1928.21   42.99-1850.93   46.14   -1736    30.7
 217.96527.90001  714.18   29.641730.73526.88998 1924.28   21.95 2083.12    26.3
 2594.03    29.1 3703.85   28.234083.93524.07054 4139.07    19.3 4360.93   23.88
    4907    23.6    4939    14.8    4962    13.2    4985     -.7    5002    -6.7
    5019    -1.4    5019      .7    5025       8    5093      23 5778.01   25.59
  5839.6   17.94 5872.27   25.68 5937.61   26.946605.21528.6499514673.32   32.25
#Mann= 7 ,-1 , 0
-2135.23    .068       0 217.965    .118       01730.735    .068       0
4083.935    .118       0    4907     .04       0    5093    .118       0
6605.215    .068       0
#XS Ineff= 2 ,-1
 -303.82 2603.01   28.49 3855.48 4578.09   23.78
Permanent Ineff=
       F       F
#Block Obstruct= 2 , 0
                        13202.25           32.31
Bank Sta=4907,5093
XS Rating Curve= 0
Exp/Cntr=.3,.1

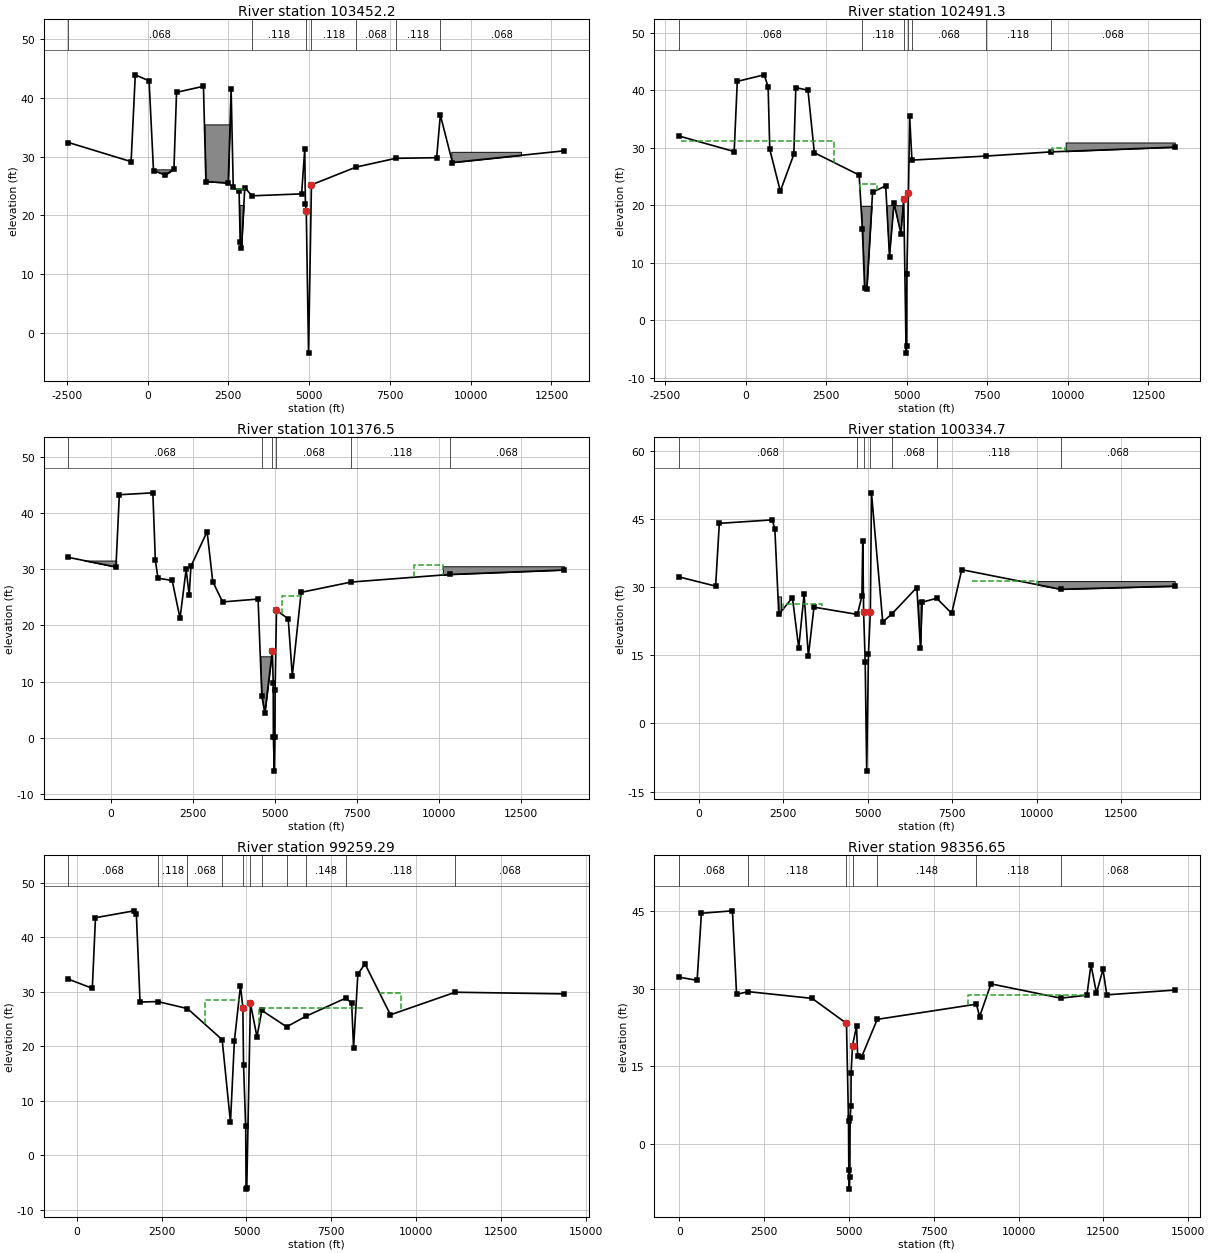
Type RM Length L Ch R = 1 ,103452.2,859.75,960.86,1176.28
XS GIS Cut Line= 6
     3262977.554    13877458.006     3261251.892    13875599.049
     3256995.191    13873671.961     3256750.399    13873260.503
     3254718.437    13869193.373     3252566.525    13866942.143
#Sta/Elev= 30
-2451.76   32.39 -512.44   29.14 -383.14   43.89   44.18   42.86  180.79   27.63
  546.47   26.87   813.1   27.86  894.11   40.92 1727.47   41.94 1802.05   25.76
  2494.1   25.51 2583.68    41.4 2649.54   24.76 2830.67   24.14  2863.6   15.49
  2901.9   14.41 3006.66   24.743227.235   23.33 4765.92   23.66    4863    31.3
    4883    21.9    4910    20.8    4980    -3.4    5070    25.26450.44528.21003
7678.335    29.7 8946.29   29.819059.71537.05993 9435.53   28.9912896.87   30.98
#Mann= 7 ,-1 , 0
-2451.76    .068       03227.235    .118       0    4910     .04       0
    5070    .118       06450.445    .068       07678.335    .118       0
9059.715    .068       0
#XS Ineff= 2 ,-1
-2451.76 1171.15   31.93 2727.64 3008.04   24.52
Permanent Ineff=
       F       F
#Block Obstruct= 4 ,-1
   69.93  930.07   27.83 1655.26 2579.46   35.47 2660.42 3060.89   21.77
 9399.8111557.35   30.81
Bank Sta=4910,5070
XS Rating Curve= 0
Exp/Cntr=.3,.1

Type RM Length L Ch R = 1 ,102491.3,704.38,1114.88,1261.49
XS GIS Cut Line= 6
     3263230.804    13877358.039     3261174.825    13875218.499
     3257724.358    13873432.378     3257870.191    13872974.045
     3256407.282    13869953.208     3253220.177    13866509.002
#Sta/Elev= 30
 -2068.3   32.08 -352.95   29.37 -257.12   41.58  577.97   42.72     700   40.62
  751.16   29.75 1078.29   22.47 1497.04   28.87  1559.2    40.5 1935.97   40.04
 2134.01   29.17 3523.55   25.29 3623.26   15.87 3693.21     5.6 3760.46    5.48
 3940.52   22.28 4347.47   23.42 4466.07   11.11 4605.82   20.39 4821.47   15.07
  4906.5    21.1  4981.5    -5.7  5000.5    -4.5  5004.5     8.1  5053.5    22.2
  5090.5    35.5 5161.52 27.8827  7468.9   28.59 9468.64   29.3113314.29   30.14
#Mann= 7 ,-1 , 0
 -2068.3    .068       0 3623.26    .118       0  4906.5     .04       0
  5053.5    .118       0 5161.52    .068       0  7468.9    .118       0
 9468.64    .068       0
#XS Ineff= 3 ,-1
-1994.11 2758.95   31.26 9505.57 9914.65   29.99 3552.01 4070.76   23.76
Permanent Ineff=
       F       F       F
#Block Obstruct= 3 ,-1
 3503.51 4030.45   19.92 4335.34 4883.36   19.95 9929.3913314.29   30.95
Bank Sta=4906.5,5053.5
XS Rating Curve= 0
Exp/Cntr=.3,.1

Type RM Length L Ch R = 1 ,101376.5,1006.03,1041.81,711.51
XS GIS Cut Line= 6
     3263350.765    13877278.065     3261418.904    13875069.015
      3258872.56    13873616.403     3258922.274    13872974.045
     3258948.316    13872187.586     3253653.184    13866424.807
#Sta/Elev= 30
 -1291.5   32.11  157.47   30.41  260.35   43.25 1282.71   43.59  1358.9   31.62
  1438.3   28.42 1872.06      28 2111.44   21.28 2297.69   29.97 2390.72   25.38
 2444.43   30.53 2937.67   36.69 3109.73    27.8 3409.56   24.19 4492.38    24.7
4606.7857.430201  4697.7    4.39  4926.5    15.5  4954.5     9.8  4958.5      .1
  4988.5    -5.9  5007.5      .1  5012.5     8.6  5053.5    22.7 5411.49   21.19
  5536.4   11.06  5805.7   25.897329.065   27.7210353.83   29.08 13832.3   29.87
#Mann= 6 ,-1 , 0
 -1291.5    .068       04606.785    .118       0  4926.5     .04       0
  5053.5    .068       07329.065    .118       010353.83    .068       0
#XS Ineff= 3 ,-1
  444.99 2909.54   35.28 9255.2610130.63   30.75 5223.26 5812.95   25.17
Permanent Ineff=
       F       F       F
#Block Obstruct= 3 ,-1
 -1291.5  249.39   31.55 4501.17 4894.61   14.5210130.63 13832.3   30.53
Bank Sta=4926.5,5053.5
XS Rating Curve= 0
Exp/Cntr=.3,.1

Type RM Length L Ch R = 1 ,100334.7,1146.64,1075.41,975.37
XS GIS Cut Line= 6
     3263584.021    13877144.776     3261678.628    13874804.697
     3260135.816    13873635.503      3259949.14    13873141.699
     3259584.365    13872192.792     3253821.555    13866392.068
#Sta/Elev= 30
 -591.07   32.22  495.83   30.18  605.42   43.99 2174.28   44.75 2249.62   42.64
 2365.68   23.97 2769.98   27.65 2955.09   16.58  3114.3   28.37  3240.7   14.84
 3407.11   25.564691.83523.95961  4825.5      28  4850.5      40  4876.5    24.4
  4922.5    13.5  4967.5   -10.5  5019.5    15.3  5075.5    24.6  5108.5    50.7
 5442.22    22.35719.055   24.12 6451.56   29.88 6558.23    16.6 6600.51   26.64
7039.78527.50999 7482.99   24.19 7780.19    33.810708.46   29.4914083.65   30.19
#Mann= 7 ,-1 , 0
 -591.07    .068       04691.835    .118       0  4876.5     .04       0
  5075.5    .118       05719.055    .068       07039.785    .118       0
10708.46    .068       0
#XS Ineff= 3 ,-1
    5200 8060.33   31.42 8081.4310017.95   31.32  2503.4 3649.27   26.31
Permanent Ineff=
       F       F       F
#Block Obstruct= 3 ,-1
 -591.07 2432.88   27.92 6483.01 6641.89   27.0610023.9114083.65   31.29
Bank Sta=4876.5,5075.5
XS Rating Curve= 0
Exp/Cntr=.3,.1

Type RM Length L Ch R = 1 ,99259.29,868.21,902.64,995.77
XS GIS Cut Line= 6
     3263863.929    13877011.487     3262501.032    13874970.569
     3261427.483    13873750.086     3261031.649    13872843.836
     3260400.338    13871741.403     3254092.594    13866387.155
#Sta/Elev= 30
 -246.71   32.32  456.46   30.65  549.88   43.61 1686.41   44.87 1754.84   44.28
 1863.06   28.132383.95528.220013260.84526.929994283.87521.23009 4528.73    6.07
 4643.81   20.96 4824.05   31.15    4894    27.1    4914    16.6    4977     5.3
    4989    -6.2    5009      -6    5116    27.9 5309.61   21.755453.05526.59003
6183.79523.590056768.38525.569717937.57528.88001 8101.16   27.87 8156.74   19.71
 8283.95   33.28 8494.32   35.13 9244.49   25.7911152.83   29.9314368.08   29.63
#Mann= 11 ,-1 , 0
 -246.71    .068       02383.955    .118       03260.845    .068       0
4283.875    .118       0    4894     .04       0    5116    .118       0
5453.055    .068       06183.795    .118       06768.385    .148       0
7937.575    .118       011152.83    .068       0
#XS Ineff= 3 ,-1
    8937 9545.49   29.84 3767.81  4815.5   28.46 5383.22 8460.81   27.02
Permanent Ineff=
       F       F       F
#Block Obstruct= 2 , 0
                         9533.79           30.26
Bank Sta=4894,5116
XS Rating Curve= 0
Exp/Cntr=.3,.1

Type RM Length L Ch R = 1 ,98356.65,899.04,974.93,961.84
XS GIS Cut Line= 6
     3264051.112    13876891.348     3262062.899    13873036.545
     3261760.897    13872355.363     3261424.643    13871515.708
     3258336.719    13869455.119     3254498.737     13866381.74
#Sta/Elev= 30
  -13.35   32.26  523.85   31.64  651.03   44.63 1565.29    45.1 1687.05   28.93
 2032.92   29.45 3915.73   28.14  4926.5    23.3  4986.5     4.3  4995.5    -5.1
  5010.5    -8.8  5025.5    -6.4  5034.5       5  5058.5     7.3  5063.5    13.7
  5104.5      19 5222.17   22.73 5256.78   17.04 5376.58   16.85 5833.12   24.08
 8756.36   27.02 8851.76   24.62  9185.7   30.9511241.11   28.1912013.43   28.75
12134.12   34.6612296.56   29.1612487.76   33.7712600.36   28.8314602.83   29.75
#Mann= 7 ,-1 , 0
  -13.35    .068       0 2032.92    .118       0  4926.5     .04       0
  5104.5    .118       0 5833.12    .148       0 8756.36    .118       0
11241.11    .068       0
#XS Ineff= 1 ,-1
 8517.4311984.11   28.77
Permanent Ineff=
       F
#Block Obstruct= 2 , 0
                         8468.53           27.13
Bank Sta=4926.5,5104.5
XS Rating Curve= 0
Exp/Cntr=.3,.1