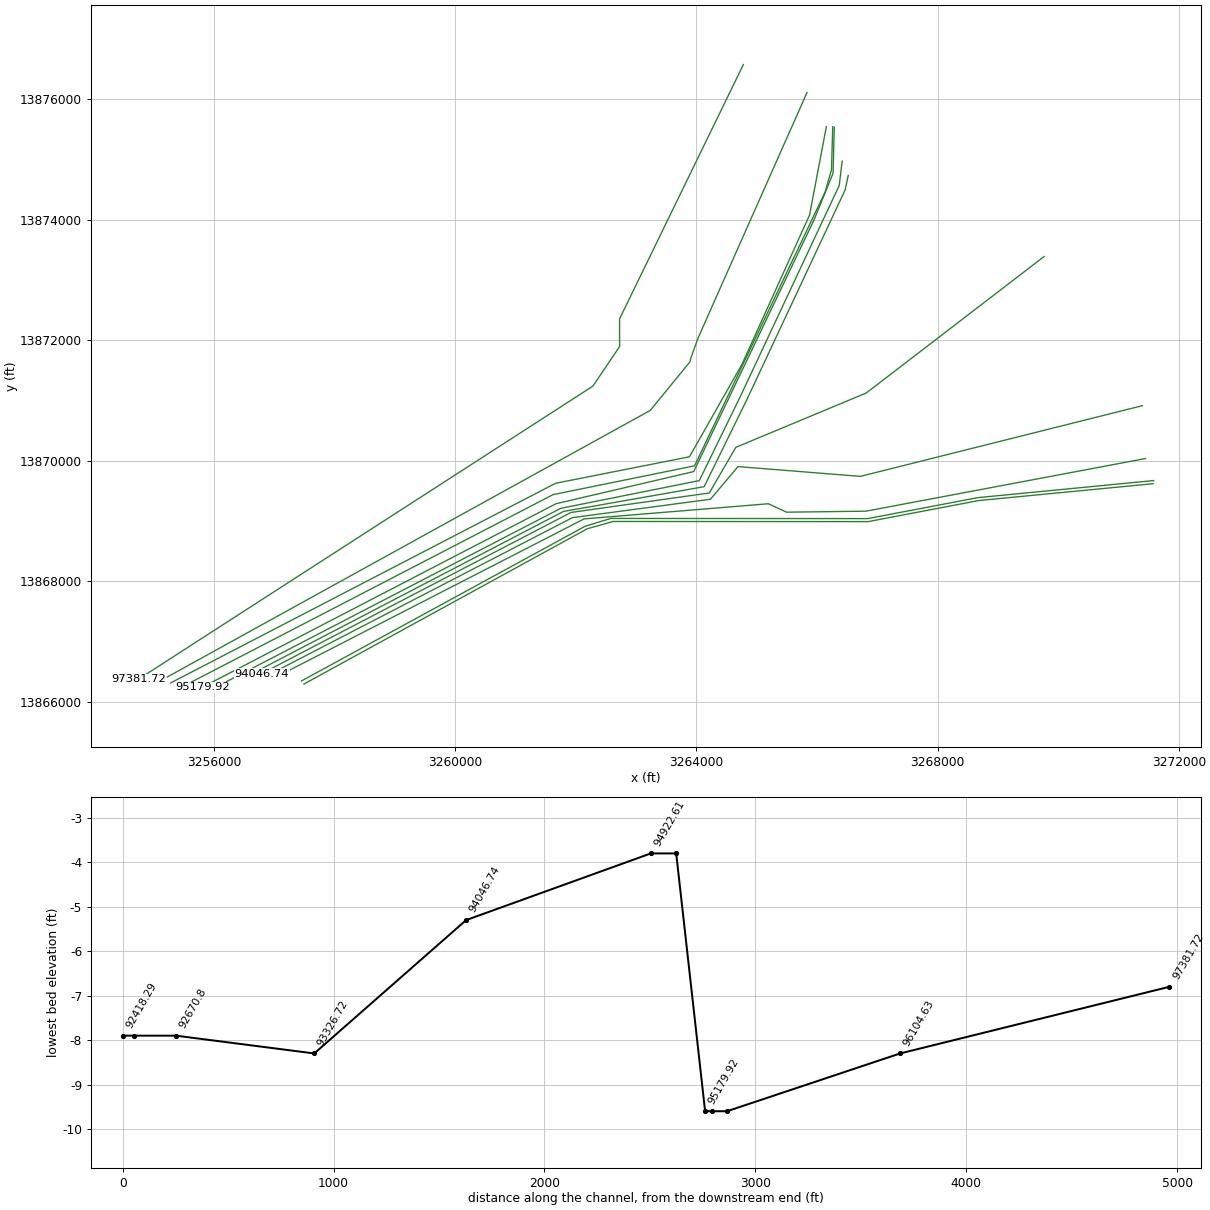
HEC-RAS study Q100-00-00.prj: Q100-00-00

--- Q100-00-00.g01 (geometry) --- (continued)

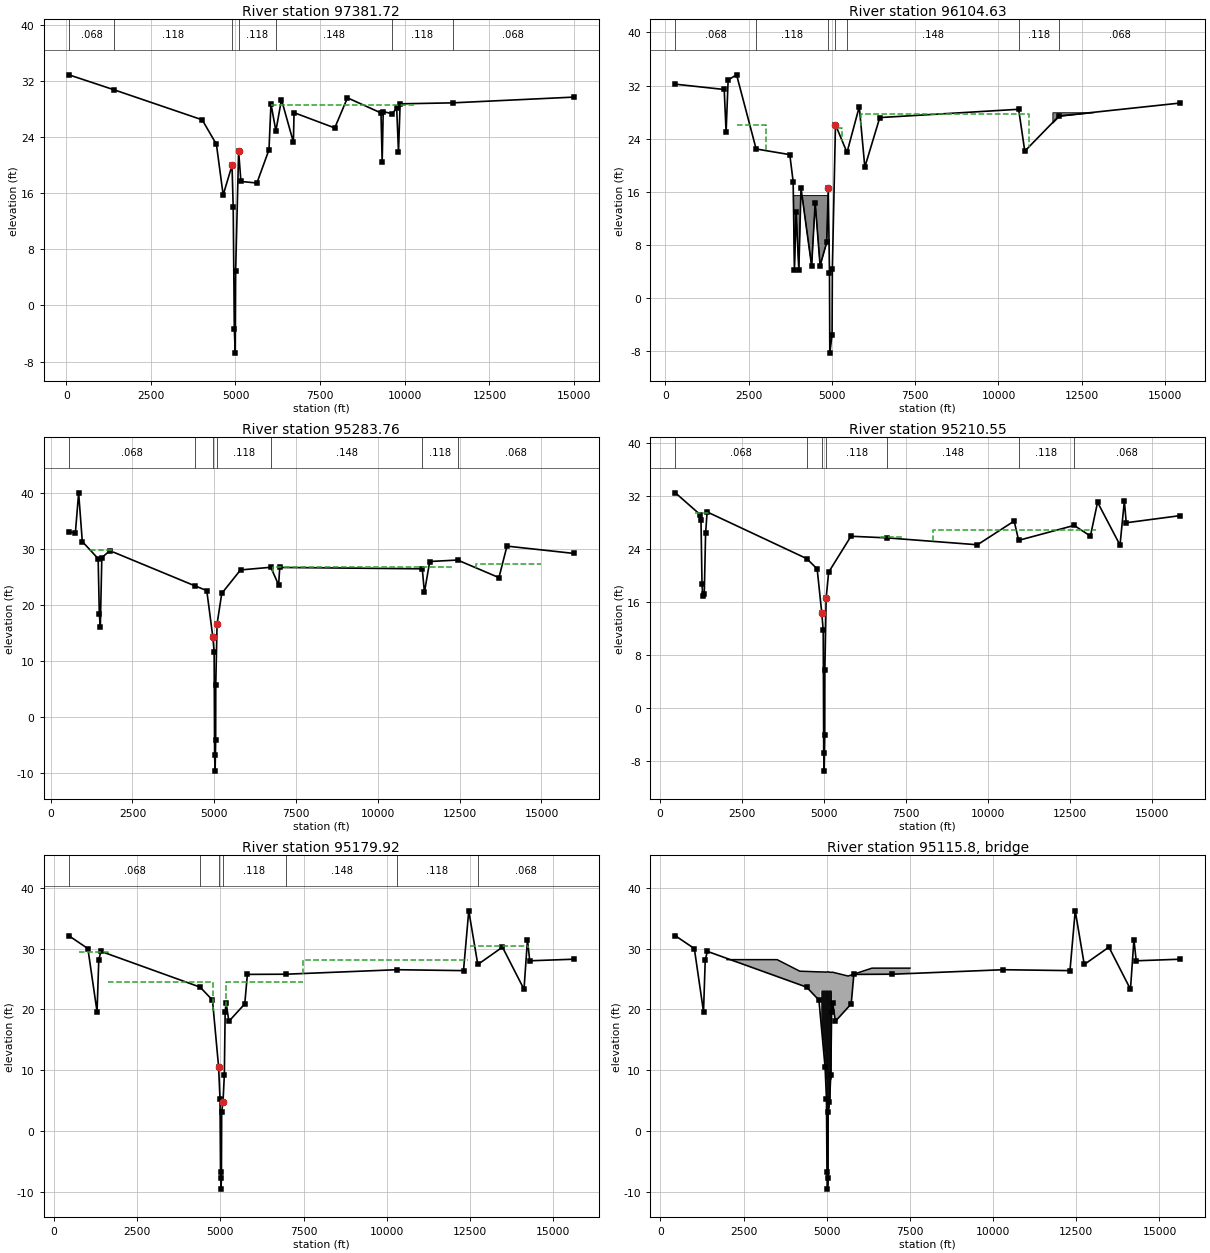
Type RM Length L Ch R = 1 ,97381.72,1312.69,1277.09,1104.84
XS GIS Cut Line= 6
     3264777.509    13876571.998     3262724.358    13872354.253
      3262724.19     13872027.65     3262726.726    13871897.653
     3262282.032    13871238.973     3254746.597    13866378.435
#Sta/Elev= 30
  79.925   32.921421.76530.77003 4015.45    26.5 4436.35   23.01 4636.17   15.77
  4897.5      20  4932.5      14  4965.5    -3.4  4993.5    -6.8  5004.5     4.9
  5092.5      22  5160.7    17.7 5632.47   17.48 5989.28   22.23 6048.02   28.77
6192.74524.91003    6358   29.39 6709.75   23.32 6729.69   27.52 7931.33   25.34
 8306.86   29.64 9296.67   27.48 9332.37    20.5 9362.85   27.689621.88527.36985
 9761.26   28.12 9814.32   21.91 9862.24   28.78   1141128.9199314989.25   29.74
#Mann= 7 ,-1 , 0
  79.925    .068       01421.765    .118       0  4897.5     .04       0
  5092.5    .118       06192.745    .148       09621.885    .118       0
   11411    .068       0
#XS Ineff= 1 ,-1
 6046.5210268.12   28.68
Permanent Ineff=
       F
#Block Obstruct= 2 , 0
                        13836.83           28.86
Bank Sta=4897.5,5092.5
XS Rating Curve= 0
Exp/Cntr=.3,.1

Type RM Length L Ch R = 1 ,96104.63,857.88,820.86,881.27
XS GIS Cut Line= 6
      3265833.25    13876107.857     3264026.441    13872036.545
     3263908.366    13871709.109     3263891.024    13871640.711
     3263232.552    13870835.327     3255148.017    13866373.083
#Sta/Elev= 30
   304.3   32.21 1769.66   31.41 1826.49   25.01 1887.61   32.85 2141.04   33.62
 2727.89   22.45    3738    21.6 3838.35   17.53 3877.36    4.28 3926.59   13.02
 4008.96    4.16 4074.29   16.56 4393.45     4.8 4498.98   14.35 4647.28    4.87
  4846.5     8.4  4891.5    16.5  4928.5     3.8  4938.5    -8.3  5006.5    -5.5
  5014.5     4.3  5108.5    26.1 5454.42   21.93 5822.78   28.82 5989.31   19.72
 6437.82   27.1810604.54   28.4310788.83   22.1211816.33   27.4215451.71   29.37
#Mann= 7 ,-1 , 0
   304.3    .068       0 2727.89    .118       0  4891.5     .04       0
  5108.5    .118       0 5454.42    .148       010604.54    .118       0
11816.33    .068       0
#XS Ineff= 4 ,-1
 1701.71 1995.11   30.06 5875.8810905.34   27.76 2151.59 3031.78   26.03
 5148.85 5317.57   25.55
Permanent Ineff=
       F       F       F       F
#Block Obstruct= 2 ,-1
 3838.29 4883.17   15.4311617.7215451.71   27.98
Bank Sta=4891.5,5108.5
XS Rating Curve= 0
Exp/Cntr=.3,.1

Type RM Length L Ch R = 1 ,95283.76,40.11,73.21,116.7
XS GIS Cut Line= 6
     3266153.679    13875540.255     3265875.782    13874077.514
      3264755.99    13871603.556     3263883.594    13870067.098
     3261663.896    13869627.732     3255278.683    13866316.253
#Sta/Elev= 30
  556.76      33  754.26    32.8  853.89   39.96  966.41   31.28 1450.37   28.24
 1486.39   18.32 1516.92   16.05 1562.73   28.42 1809.08   29.66 4413.74   23.38
 4770.37   22.55    4955    14.3    4995    11.7    5010    -6.8    5025    -9.6
    5042    -4.1    5045     5.7    5085    16.6 5227.61   22.04 5801.76   26.23
 6727.93    26.7 6965.73   23.55 7000.82   26.6711356.31   26.4311421.75   22.24
11584.66   27.7312436.26   27.9913699.97   24.8613944.75   30.4715984.68   29.17
#Mann= 7 ,-1 , 0
  556.76    .068       0 4413.74    .118       0    4955     .04       0
    5085    .118       0 6727.93    .148       011356.31    .118       0
12436.26    .068       0
#XS Ineff= 3 ,-1
 1193.15 1897.31   29.7512995.2514970.63   27.37 6788.8312285.21   26.84
Permanent Ineff=
       F       F       F
Bank Sta=4955,5085
XS Rating Curve= 0
Exp/Cntr=.3,.1

Type RM Length L Ch R = 1 ,95210.55,30.54,30.63,30.97
XS GIS Cut Line= 6
     3266259.705    13875540.255     3266239.509    13874828.368
     3266133.099    13874457.303     3263968.246    13869917.115
      3261621.67    13869439.207     3255519.292    13866277.082
#Sta/Elev= 30
 465.835   32.51  1217.5   29.23 1247.15   28.33  1278.3   18.69 1301.94   16.89
 1347.21   17.23 1387.54   26.37 1434.35   29.624468.83522.56001    4790      21
4930.71514.33428    4975    11.7    4990    -6.8    5005    -9.6    5022    -4.1
    5025     5.7    5065    16.6    5140    20.5  5821.1   25.946932.21525.68995
 9679.04   24.6510799.15   28.2410935.22   25.3212628.79   27.5813123.81   25.97
13342.72   31.0814027.09    24.6 14159.4   31.2814216.42   27.9815861.98   29.06
#Mann= 7 ,-1 , 0
 465.835    .068       04468.835    .118       04930.715     .04       0
    5065    .118       06932.215    .148       010935.22    .118       0
12628.79    .068       0
#XS Ineff= 4 ,-1
13339.8514141.81    29.6 1056.23 1525.67   29.44 8308.3513306.02   26.95
 6748.17 7374.08   25.87
Permanent Ineff=
       F       F       F       F
#Block Obstruct= 2 , 0
                        14154.36           29.42
Bank Sta=4930.715,5065
XS Rating Curve= 0
Exp/Cntr=.5,.3

Type RM Length L Ch R = 1 ,95179.92,138.43,137.12,140.39
XS GIS Cut Line= 6
     3266284.949    13875530.157     3266264.753    13874767.782
      3265947.97    13873992.047     3263954.108    13869821.565
     3261669.545    13869288.157      3255806.58    13866246.302
#Sta/Elev= 30
 447.625   32.13 1018.04   30.02 1293.71   19.62 1345.66   28.19 1410.99   29.56
4393.01523.66988 4763.38   21.53    4948    10.5    4990     5.2    5005    -6.8
    5020    -9.6    5032    -7.8    5040     3.1    5080     4.8    5120     9.2
 5144.67   19.58 5172.44   21.12 5257.03   18.04 5733.71   20.91 5812.74   25.77
6972.69525.79998 10311.1   26.5412309.37   26.3912467.55   36.2412739.04    27.4
13480.61   30.2614128.04   23.3214232.26   31.5114299.86   28.0115622.21   28.27
#Mann= 7 ,-1 , 0
 447.625    .068       04393.015    .118       0    4948     .04       0
    5080    .118       06972.695    .148       0 10311.1    .118       0
12739.04    .068       0
#XS Ineff= 5 ,-1
12498.7814259.17   30.37  743.28 1623.47   29.44 7499.4312450.51   28.16
    5159 7499.43   24.44 1623.47    4793   24.44
Permanent Ineff=
       F       F       F       F       F
#Block Obstruct= 2 , 0
                        14251.49           30.42
Bank Sta=4948,5080
XS Rating Curve= 0
Exp/Cntr=.5,.3

Type RM Length L Ch R = 3 ,95115.8 ,,,
BEGIN DESCRIPTION:
Southern Pacific RR (Just North of I-10)
END DESCRIPTION:
Bridge Culvert--1,0,-1,-1, 0
Deck Dist Width WeirC Skew NumUp NumDn MinLoCord MaxHiCord MaxSubmerge Is_Ogee
60.1,8,2.6,0, 21, 21, , , .95, 0, 0,0,,
    2000    3507    4186    4789    4814    4844    4874    4904    4934    4964
    4994    5024    5054    5084    5114    5144    5174    5640    6357    6450
    7500
    28.2    28.2    26.3   26.18   26.19   26.17   26.17   26.17   26.15   26.17
   26.15   26.18   26.19   26.12   26.12   26.11   26.13    25.5    26.8    26.8
    26.8
       0       0       0       0   23.19   23.17   23.17   23.17   23.15   23.17
   23.15   23.18   23.19   23.12   23.12   23.11       0       0       0       0
       0
    2000    3507    4186    4789    4814    4844    4874    4904    4934    4964
    4994    5024    5054    5084    5114    5144    5174    5640    6357    6450
    7500
    28.2    28.2    26.3   26.18   26.19   26.17   26.17   26.17   26.15   26.17
   26.15   26.18   26.19   26.12   26.12   26.11   26.13    25.5    26.8    26.8
    26.8
       0       0       0       0   23.19   23.17   23.17   23.17   23.15   23.17
   23.15   23.18   23.19   23.12   23.12   23.11       0       0       0       0
       0
Pier Skew, UpSta & Num, DnSta & Num=  ,4829, 2 ,4829, 2 , 0 , 0 , 0 ,,
       1       1
       0   26.19
       1       1
       0   26.19
Pier Skew, UpSta & Num, DnSta & Num=  ,4844, 2 ,4844, 2 , 0 , 0 , 0 ,,
       1       1
       0   26.19
       1       1
       0   26.19
Pier Skew, UpSta & Num, DnSta & Num=  ,4859, 2 ,4859, 2 , 0 , 0 , 0 ,,
       1       1
       0   26.19
       1       1
       0   26.19
Pier Skew, UpSta & Num, DnSta & Num=  ,4874, 2 ,4874, 2 , 0 , 0 , 0 ,,
       1       1
       0   26.19
       1       1
       0   26.19
Pier Skew, UpSta & Num, DnSta & Num=  ,4889, 2 ,4889, 2 , 0 , 0 , 0 ,,
       1       1
       0   26.19
       1       1
       0   26.19
Pier Skew, UpSta & Num, DnSta & Num=  ,4904, 2 ,4904, 2 , 0 , 0 , 0 ,,
       1       1
       0   26.19
       1       1
       0   26.19
Pier Skew, UpSta & Num, DnSta & Num=  ,4919, 2 ,4919, 2 , 0 , 0 , 0 ,,
       1       1
       0   26.19
       1       1
       0   26.19
Pier Skew, UpSta & Num, DnSta & Num=  ,4934, 2 ,4934, 2 , 0 , 0 , 0 ,,
       1       1
       0   26.19
       1       1
       0   26.19
Pier Skew, UpSta & Num, DnSta & Num=  ,4949, 2 ,4949, 2 , 0 , 0 , 0 ,,
       1       1
       0   26.19
       1       1
       0   26.19
Pier Skew, UpSta & Num, DnSta & Num=  ,4964, 2 ,4964, 2 , 0 , 0 , 0 ,,
       1       1
       0   26.19
       1       1
       0   26.19
Pier Skew, UpSta & Num, DnSta & Num=  ,4979, 2 ,4979, 2 , 0 , 0 , 0 ,,
       1       1
       0   26.19
       1       1
       0   26.19
Pier Skew, UpSta & Num, DnSta & Num=  ,4994, 2 ,4994, 2 , 0 , 0 , 0 ,,
       1       1
       0   26.19
       1       1
       0   26.19
Pier Skew, UpSta & Num, DnSta & Num=  ,5009, 2 ,5009, 2 , 0 , 0 , 0 ,,
       1       1
       0   26.19
       1       1
       0   26.19
Pier Skew, UpSta & Num, DnSta & Num=  ,5024, 2 ,5024, 2 , 0 , 0 , 0 ,,
       1       1
       0   26.19
       1       1
       0   26.19
Pier Skew, UpSta & Num, DnSta & Num=  ,5039, 2 ,5039, 2 , 0 , 0 , 0 ,,
       1       1
       0   26.19
       1       1
       0   26.19
Pier Skew, UpSta & Num, DnSta & Num=  ,5054, 2 ,5054, 2 , 0 , 0 , 0 ,,
       1       1
       0   26.19
       1       1
       0   26.19
Pier Skew, UpSta & Num, DnSta & Num=  ,5069, 2 ,5069, 2 , 0 , 0 , 0 ,,
       1       1
       0   26.19
       1       1
       0   26.19
Pier Skew, UpSta & Num, DnSta & Num=  ,5084, 2 ,5084, 2 , 0 , 0 , 0 ,,
       1       1
       0   26.19
       1       1
       0   26.19
Pier Skew, UpSta & Num, DnSta & Num=  ,5099, 2 ,5099, 2 , 0 , 0 , 0 ,,
       1       1
       0   26.19
       1       1
       0   26.19
Pier Skew, UpSta & Num, DnSta & Num=  ,5114, 2 ,5114, 2 , 0 , 0 , 0 ,,
       1       1
       0   26.19
       1       1
       0   26.19
Pier Skew, UpSta & Num, DnSta & Num=  ,5129, 2 ,5129, 2 , 0 , 0 , 0 ,,
       1       1
       0   26.19
       1       1
       0   26.19
BR Coef=-1 , 1 , 1 ,.9, 0 ,,,.8,0,2,0,
WSPro=,,,, 1 ,,,, 0 ,,,, 0 ,,,,-1 ,-1 ,-1 , 0 , 0 , 0 , 0 , 0
BC Design=,, 0 ,, 0 ,,,,,,
BC HTab HWMax=28.44

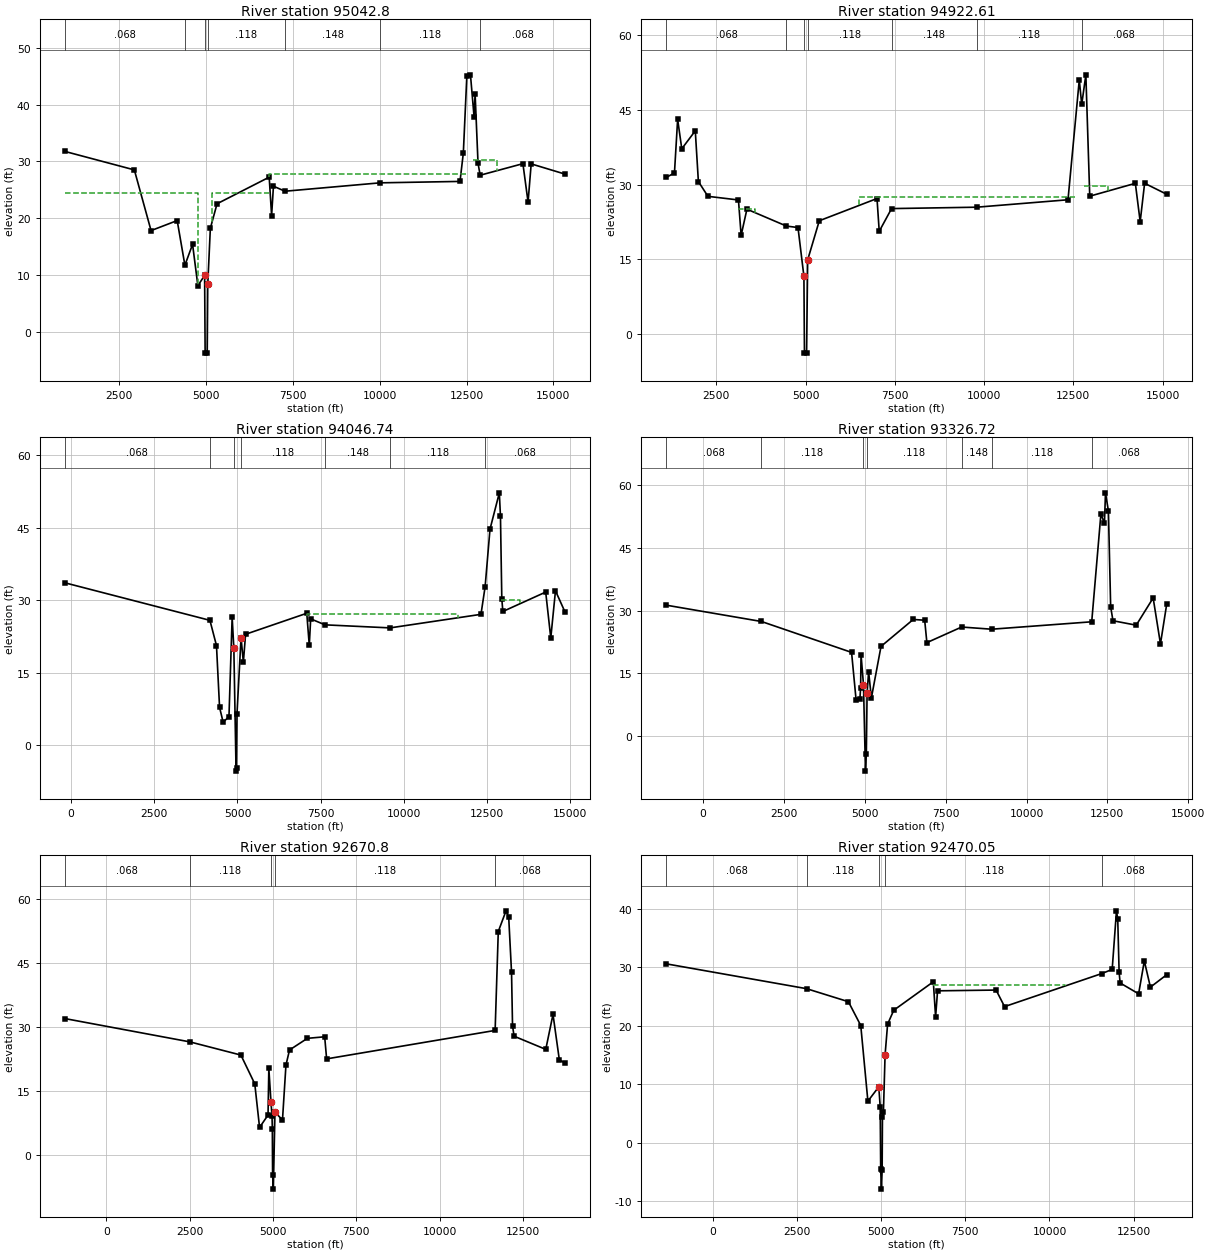
Type RM Length L Ch R = 1 ,95042.8 ,122.15,120.19,123.87
XS GIS Cut Line= 6
     3266416.219    13874969.736     3266367.986    13874567.138
     3264727.034    13871066.348     3264046.323    13869671.951
     3261747.281    13869211.522     3256206.731    13866338.644
#Sta/Elev= 30
 929.335   31.76 2931.83    28.5 3412.99    17.8 4165.66   19.574387.59511.69008
 4608.54   15.38 4761.01    8.09  4955.5     9.9  4970.5    -3.8  5030.5    -3.7
  5045.5     8.3  5120.5    18.2 5313.13   22.53 6815.17   27.22 6884.43   20.44
 6937.56   25.637269.48524.7400510007.28   26.2212310.11   26.4712405.95   31.49
12507.33   45.1212611.21   45.2612715.23   37.8412744.74   41.9412828.37   29.73
12889.16   27.5614121.52    29.614269.85   22.8214359.56   29.5615338.76   27.75
#Mann= 7 ,-1 , 0
 929.335    .068       04387.595    .118       0  4955.5     .04       0
  5045.5    .118       07269.485    .148       010007.28    .118       0
12889.16    .068       0
#XS Ineff= 4 ,-1
12674.8213378.97   30.25 6815.1712474.76   27.83    5167 6815.17   24.44
 929.335    4757   24.44
Permanent Ineff=
       F       F       F       F
#Block Obstruct= 2 , 0
                        13378.97           30.81
Bank Sta=4955.5,5045.5
XS Rating Curve= 0
Exp/Cntr=.5,.3

Type RM Length L Ch R = 1 ,94922.61,1298.46,875.88,309.96
XS GIS Cut Line= 6
     3266517.195     13874732.44      3266465.72    13874492.927
      3264834.96    13871013.874     3264126.986     13869570.95
     3261794.887    13869160.709     3256514.539    13866410.466
#Sta/Elev= 30
  1103.5   31.47 1329.32   32.36 1418.39   43.11 1534.24    37.2 1912.45   40.81
 1999.31   30.63 2266.38   27.66 3121.78   26.93 3196.73   19.83 3359.08   25.08
 4467.38   21.69  4789.5    21.4  4955.5    11.6  4970.5    -3.8  5030.5    -3.7
  5060.5    14.9 5386.22   22.76 7002.86   27.22 7064.92   20.64 7410.78    25.2
 9793.53   25.4812352.66   26.97 12668.9   51.0212736.93   46.0912853.08   52.04
12961.95   27.6914239.31   30.2714374.61   22.5814498.92   30.2815119.68   28.07
#Mann= 7 ,-1 , 0
  1103.5    .068       0 4467.38    .118       0  4955.5     .04       0
  5060.5    .118       0 7410.78    .148       0 9793.53    .118       0
12736.93    .068       0
#XS Ineff= 3 ,-1
12792.1813476.77   29.78  6511.712555.71   27.53 3110.79 3587.11   25.16
Permanent Ineff=
       F       F       F
#Block Obstruct= 2 , 0
                        13476.77           30.87
Bank Sta=4955.5,5060.5
XS Rating Curve= 0
Exp/Cntr=.3,.1

Type RM Length L Ch R = 1 ,94046.74,1023.22,720.01,348.67
XS GIS Cut Line= 6
     3269765.363    13873388.195     3266816.694    13871125.279
     3264651.823    13870223.348     3264212.319    13869466.537
     3261918.293    13869143.411     3256791.567    13866472.028
#Sta/Elev= 30
 -187.08   33.624173.07525.85987 4370.22   20.65 4462.83    7.88  4570.2    4.81
 4745.61    5.96    4841    26.5    4892    20.1    4959    -5.3    4972    -4.6
    4987     6.6    5108    22.3    5178    17.2  5244.2   22.98 7083.15   27.32
 7158.63   20.69 7200.79   26.177631.12524.929999585.66524.3001312317.75    27.1
12442.32   32.8212588.43   44.6812869.13   52.2112903.39   47.3412943.66    30.3
12975.12   27.6914262.35    31.714415.17   22.2114556.14   31.9714847.92    27.5
#Mann= 7 ,-1 , 0
 -187.08    .068       04173.075    .118       0    4892     .04       0
    5108    .118       07631.125    .148       09585.665    .118       0
12442.32    .068       0
#XS Ineff= 3 ,-1
12905.6813503.36   29.99 7088.7111622.57   27.18 4209.79 4860.14   19.97
Permanent Ineff=
       F       F       F
#Block Obstruct= 2 , 0
                        13507.69           29.94
Bank Sta=4892,5108
XS Rating Curve= 0
Exp/Cntr=.3,.1

Type RM Length L Ch R = 1 ,93326.72,649.37,655.93,670.01
XS GIS Cut Line= 6
     3271393.668    13870914.425     3266718.054    13869742.072
     3264687.966    13869904.039     3264231.582    13869362.709
     3261942.227    13869057.618     3256986.512    13866492.548
#Sta/Elev= 30
-1134.36   31.29 1805.18    27.4 4590.88   20.03 4732.05    8.59 4848.43    8.88
 4870.83   11.64  4883.5    19.5  4959.5    12.3  5020.5    -8.3  5047.5    -4.1
  5070.5    10.3  5118.5    15.4 5203.49    9.16 5501.38   21.46 6498.64   27.89
 6851.78    27.7 6919.38   22.36 7993.69   26.08 8921.96   25.5612016.22   27.33
12300.13   53.0412410.05   50.8712441.84    58.112532.55   53.76   12602   30.91
12673.37   27.5813392.33   26.5213915.82   33.0214141.76   22.0614336.91   31.64
#Mann= 7 ,-1 , 0
-1134.36    .068       0 1805.18    .118       0  4959.5     .04       0
  5070.5    .118       0 7993.69    .148       0 8921.96    .118       0
12016.22    .068       0
#XS Ineff= 2 ,-1
 12391.213821.52   29.78  6496.511468.53   26.95
Permanent Ineff=
       F       F
#Block Obstruct= 2 , 0
                        13865.53           31.52
Bank Sta=4959.5,5070.5
XS Rating Curve= 0
Exp/Cntr=.3,.1

Type RM Length L Ch R = 1 ,92670.8 ,113.61,200.75,218.56
XS GIS Cut Line= 6
     3271445.857    13870037.645     3266811.136    13869164.875
     3265495.052    13869148.163     3265192.253    13869287.916
     3262137.172    13869037.098     3257181.457    13866492.548
#Sta/Elev= 30
-1242.61   31.95 2508.96    26.5 4038.19   23.42 4454.44    16.7 4597.97    6.52
    4852     9.4    4876    20.3    4941    12.4    4971     9.3    4981     6.2
    4989    -4.5    5011    -7.9 5060.0310.06293 5285.52    8.27  5389.4   21.08
 5496.56   24.61 6032.43   27.33 6550.92   27.69 6609.19   22.5311662.79   29.18
11757.21   52.2811989.31   57.1212069.94   55.6312154.68   42.7812184.67   30.27
12230.62   27.8313181.22   24.7513398.34   32.9213588.29   22.3113763.66    21.5
#Mann= 5 ,-1 , 0
-1242.61    .068       0 2508.96    .118       0    4941     .04       0
 5060.03    .118       011662.79    .068       0
#XS Ineff= 2 ,-1
12004.8913393.64   28.48 6130.5410829.84   27.36
Permanent Ineff=
       F       F
#Block Obstruct= 2 , 0
                        13432.76           30.43
Bank Sta=4941,5060.03
XS Rating Curve= 0
Exp/Cntr=.3,.1

Type RM Length L Ch R = 1 ,92470.05,50.42,51.76,51
XS GIS Cut Line= 6
     3271581.549     13869672.32     3268667.564    13869389.639
     3266840.157    13869041.435      3262578.36     13869044.43
     3262150.767    13868913.652     3257448.224    13866348.904
#Sta/Elev= 30
-1373.24   30.622786.45526.37998 4030.31   24.15 4397.19   20.08 4608.87    7.14
    4933     9.6    4974     6.2    4989    -4.5    5011    -7.9    5032    -4.6
    5041     4.4    5070     5.3 5119.17   15.05 5194.19   20.31 5376.81   22.69
 6551.83   27.56 6619.27   21.54 6677.45   26.01 8415.47   26.14 8666.69   23.31
11551.52   28.9611861.83   29.6711989.34   39.6912026.96   38.2612067.95   29.17
12098.63   27.3512646.78    25.512816.33   31.1212996.56   26.64 13482.8   28.77
#Mann= 5 ,-1 , 0
-1373.24    .068       02786.455    .118       0    4933     .04       0
 5119.17    .118       011551.52    .068       0
#XS Ineff= 2 ,-1
11809.2912787.29   29.29 6542.2310469.61   27.01
Permanent Ineff=
       F       F
#Block Obstruct= 2 , 0
         1584.29   28.5812826.41           29.91
Bank Sta=4933,5119.17
XS Rating Curve= 0
Exp/Cntr=.5,.3

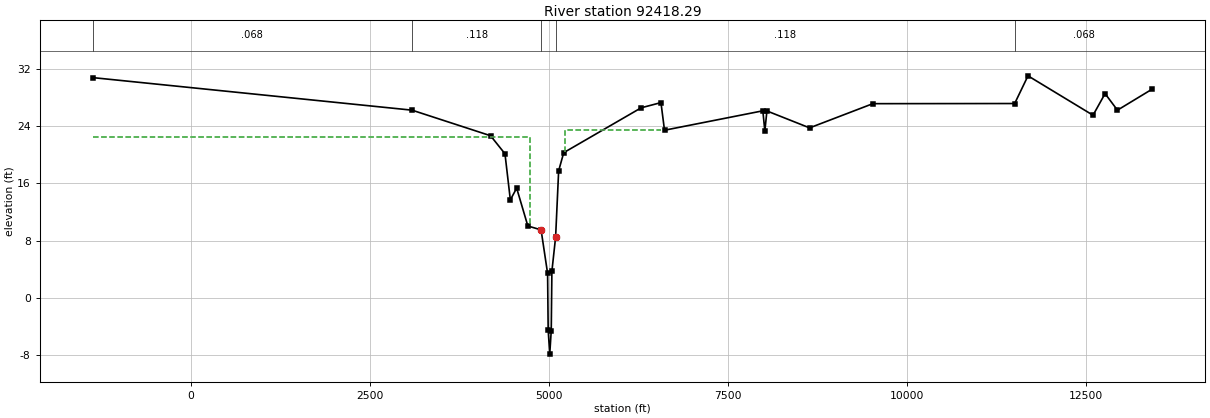
Type RM Length L Ch R = 1 ,92418.29,383.16,391.72,386.76
XS GIS Cut Line= 6
     3271571.112    13869620.131     3268681.306    13869340.984
     3266846.569    13868991.438     3262619.418    13868994.367
     3262188.473    13868872.933     3257489.266    13866297.603
#Sta/Elev= 30
 -1374.5   30.83  3087.2   26.27 4183.93   22.69  4385.4   20.16  4460.4   13.71
 4548.76   15.35 4704.94   10.05    4890     9.5    4981     3.4    4989    -4.5
    5011    -7.9    5032    -4.6    5041     3.7    5093     8.5  5135.4   17.78
 5206.44   20.32 6288.12    26.6 6565.02   27.33 6614.57   23.46  7988.7   26.18
 8016.67   23.35 8045.68   26.16 8642.09   23.79 9525.73   27.1811507.76    27.2
11693.92   31.0812602.52   25.5612770.78   28.5912943.81   26.2713432.69   29.24
#Mann= 5 ,-1 , 0
 -1374.5    .068       0  3087.2    .118       0    4890     .04       0
    5093    .118       011507.76    .068       0
#XS Ineff= 4 ,-1
 6565.8811694.08    27.2 5222.63 6565.88   23.4311694.0813432.69   23.43
 -1374.5 4729.68   22.58
Permanent Ineff=
       F       F       F       F
#Block Obstruct= 2 , 0
                        11926.65           28.51
Bank Sta=4890,5093
XS Rating Curve= 0
Exp/Cntr=.5,.3