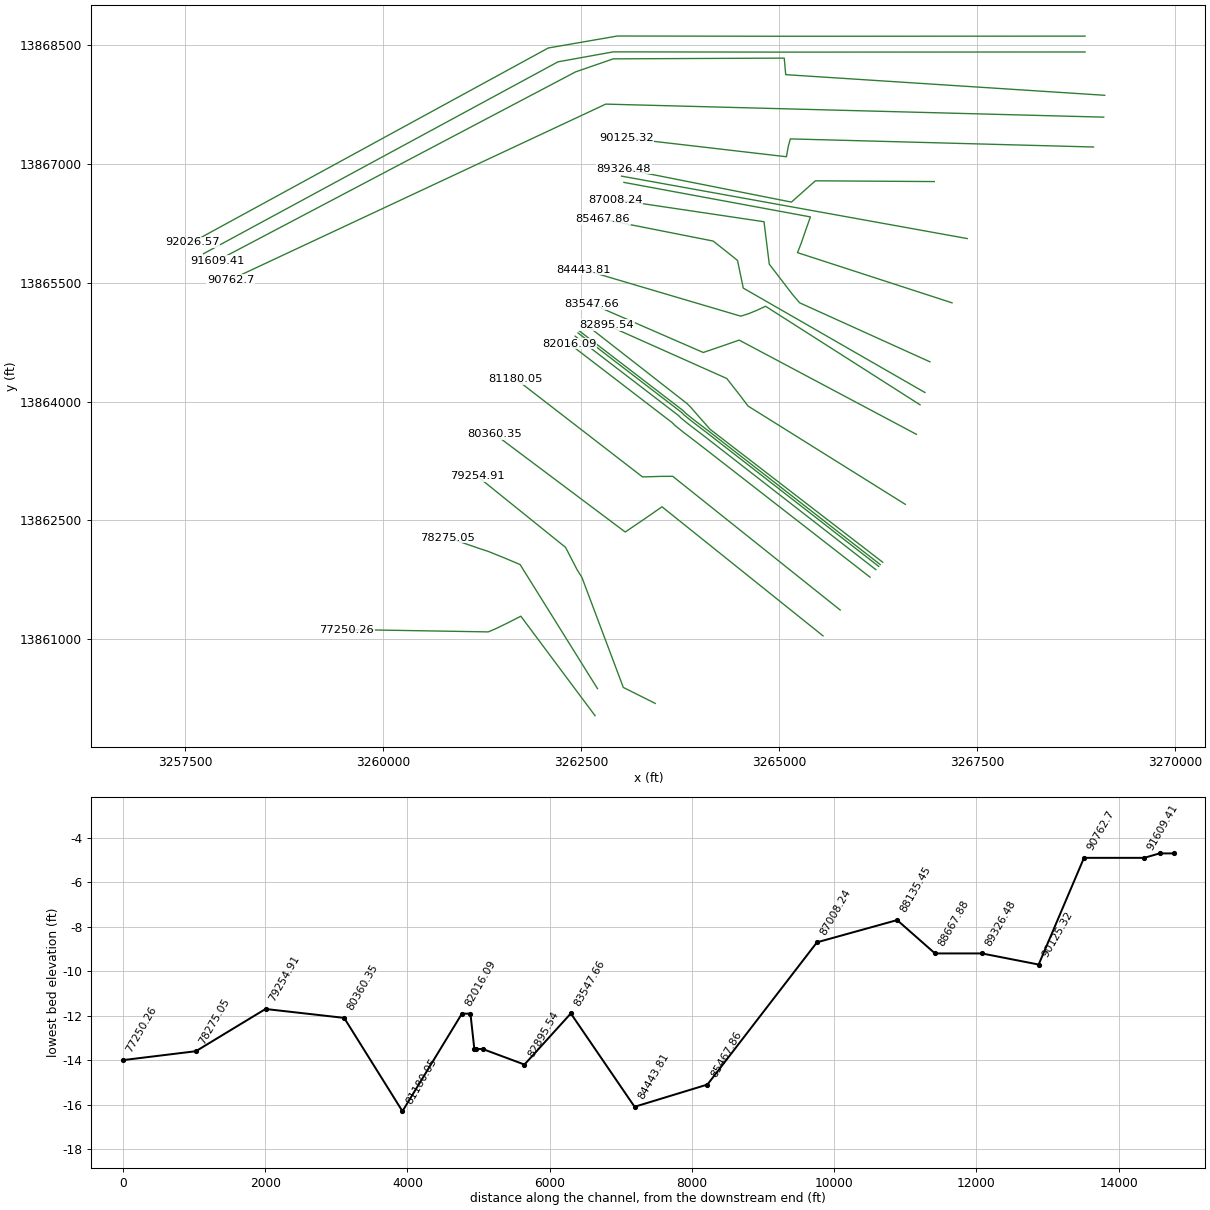
HEC-RAS study Q100-00-00.prj: Q100-00-00

--- Q100-00-00.g01 (geometry) --- (continued)

Type RM Length L Ch R = 3 ,92216.8 ,,,
BEGIN DESCRIPTION:
Interstate 10
END DESCRIPTION:
Bridge Culvert--1,0,-1,-1, 0
Deck Dist Width WeirC Skew NumUp NumDn MinLoCord MaxHiCord MaxSubmerge Is_Ogee
67.24,268.43,2.6,0, 31, 31, , , .95, 0, 0,0,,
   -3043   -2030   -1332    -205    -113     118     192    1200  2818.4  3909.4
    4606    4636    4834    4860    5016    5170    5196    5226  5354.6  6267.7
  6391.7  6461.3  6620.9  6770.9  6926.9  7046.9  7446.9    8022    9207   11946
   13227
    33.5    31.6    32.3    49.2    29.4    31.7    48.9    31.8    31.8    27.4
      23   25.72   25.72   25.72   26.54   27.07   27.07   24.34    32.9    55.7
    57.2    32.2      27      28    55.4    54.9    46.8      34    29.5   31.64
   30.13
       0       0       0       0       0       0       0       0       0       0
       0       0       0   18.45   19.85   19.88       0       0       0       0
       0       0       0       0       0       0       0       0       0       0
       0
   -3043   -2030   -1332    -205    -113     118     192    1200  2818.4  3909.4
    4606    4636    4834    4860    5016    5170    5196    5226  5354.6  6267.7
  6391.7  6461.3  6620.9  6770.9  6926.9  7046.9  7446.9    8022    9207   11946
   13227
    33.5    31.6    32.3    49.2    29.4    31.7    48.9    31.8    31.8    27.4
      23   25.72   25.72   25.72   26.54   27.07   27.07   24.34    32.9    55.7
    57.2    32.2      27      28    55.4    54.9    46.8      34    29.5   31.64
   30.13
       0       0       0       0       0       0       0       0       0       0
       0       0       0   18.45   19.85   19.88       0       0       0       0
       0       0       0       0       0       0       0       0       0       0
       0
Pier Skew, UpSta & Num, DnSta & Num=  ,4915, 2 ,4915, 2 , 0 , 0 , 0 ,,
    1.78    1.78
       0      21
    1.78    1.78
       0      21
Pier Skew, UpSta & Num, DnSta & Num=  ,4970, 2 ,4970, 2 , 0 , 0 , 0 ,,
    1.78    1.78
       0      21
    1.78    1.78
       0      21
Pier Skew, UpSta & Num, DnSta & Num=  ,5060, 2 ,5060, 2 , 0 , 0 , 0 ,,
    1.78    1.78
       0      21
    1.78    1.78
       0      21
Pier Skew, UpSta & Num, DnSta & Num=  ,5115, 2 ,5115, 2 , 0 , 0 , 0 ,,
    1.78    1.78
       0      21
    1.78    1.78
       0      21
BR Coef=-1 , 1 , 1 ,.9, 0 ,,,.8,0,1.2,0,
WSPro=,,,, 1 ,,,, 0 ,,,, 0 ,,,,-1 ,-1 ,-1 , 0 , 0 , 0 , 0 , 0
BC Design=,, 0 ,, 0 ,,,,,,
BC HTab HWMax=28.48

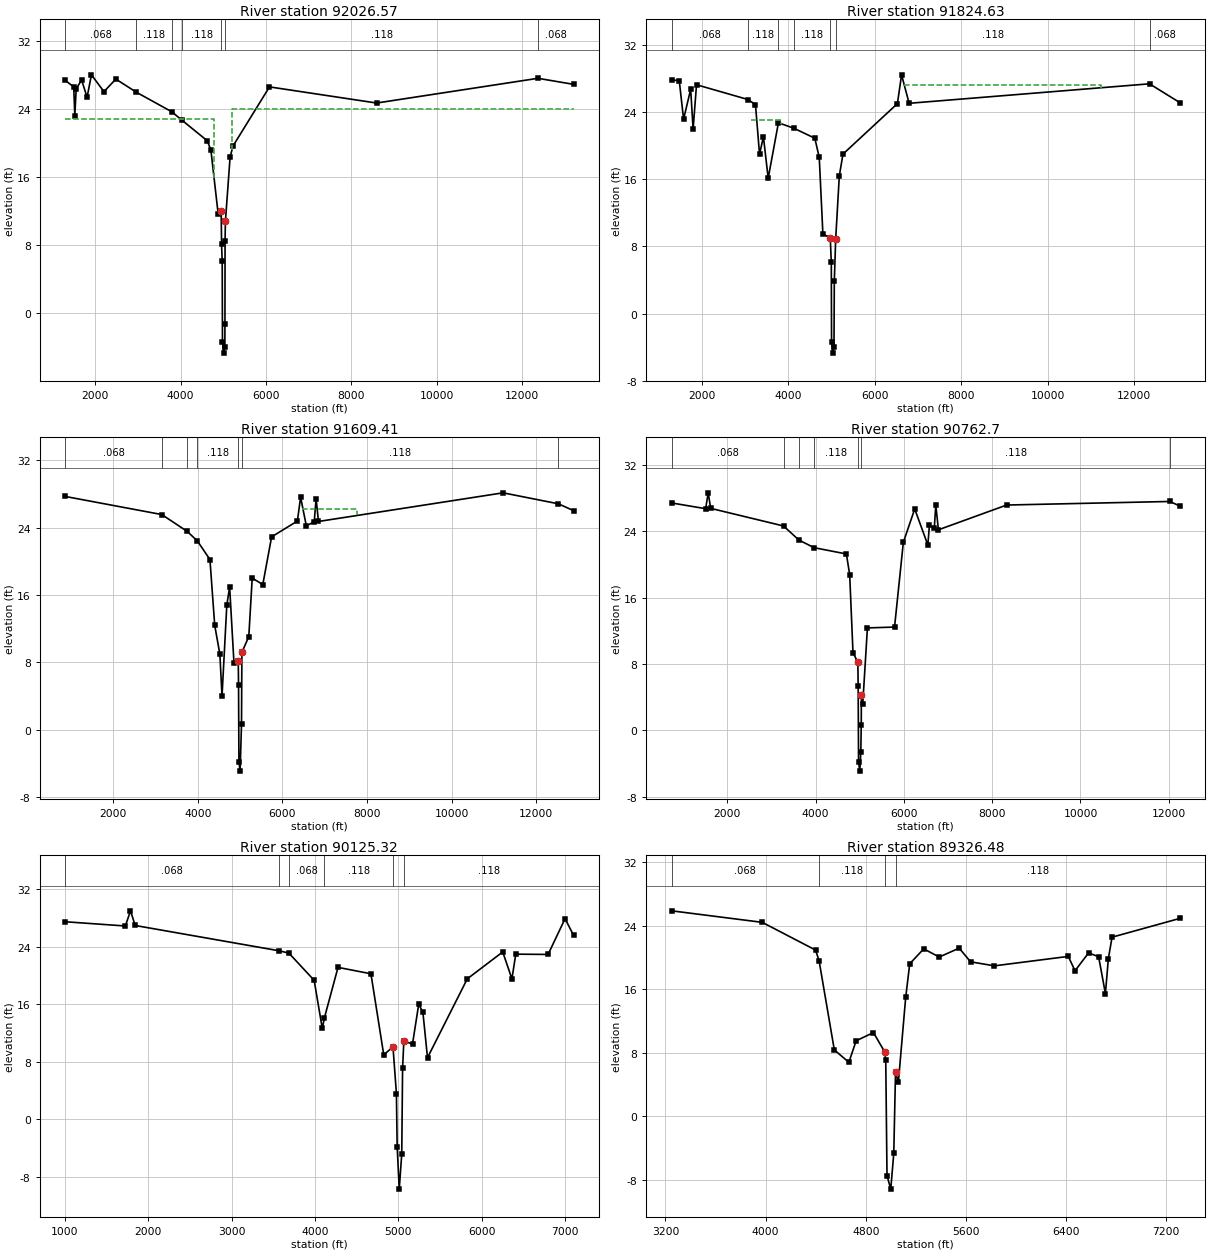
Type RM Length L Ch R = 1 ,92026.57,201.66,201.94,202.96
XS GIS Cut Line= 6
     3268860.782    13868612.441     3265563.792      13868610.8
     3264926.167      13868610.8     3262958.006    13868613.843
     3262085.871    13868462.522     3257591.868    13866010.315
#Sta/Elev= 30
 1296.78   27.41 1496.06   26.64 1522.09   23.27 1554.26   26.42  1680.7   27.45
 1809.52   25.42 1910.91   28.06 2204.73   26.08 2482.21   27.56 2963.82   26.01
 3797.35    23.7 4035.49    22.7  4624.5    20.3  4709.5    19.2  4879.5    11.7
  4950.5      12  4959.5     8.1  4974.5     6.1  4980.5    -3.4  5008.5    -4.7
  5036.5      -4  5038.5    -1.3  5041.5     8.5  5049.5    10.8  5159.5    18.4
  5229.5    19.7 6081.61   26.64  8591.1   24.7412370.71   27.6513204.23   26.94
#Mann= 7 ,-1 , 0
 1296.78    .068       0 2963.82    .118       0 3797.35    .068       0
 4035.49    .118       0  4950.5     .04       0  5049.5    .118       0
12370.71    .068       0
#XS Ineff= 2 , 0
       0 4787.21   22.82  5200.7       0   24.07
Permanent Ineff=
       F       F
#Block Obstruct= 2 , 0
         1615.38    26.3
Bank Sta=4950.5,5049.5
XS Rating Curve= 0
Exp/Cntr=.5,.3

Type RM Length L Ch R = 1 ,91824.63,333.65,215.22,80.56
XS GIS Cut Line= 6
     3268860.881    13868412.441     3265563.781      13868410.8
     3264926.128      13868410.8     3262906.729    13868413.922
     3262208.994    13868288.097     3257735.512    13865866.671
#Sta/Elev= 30
1304.645   27.82  1479.7   27.76 1579.84   23.16 1743.74   26.71 1800.18   21.97
 1878.77   27.263067.13525.50004 3241.47   24.89 3335.72   18.99 3425.33   21.06
  3535.5   16.133772.12522.729914124.62522.09003  4613.6   20.89    4716    18.6
    4800     9.5  4970.5       9  4994.5     6.1  5000.5    -3.4  5028.5    -4.7
  5056.5      -4    5064     3.9    5096     8.9  5179.5    16.4    5264      19
  6522.4   25.01 6618.84   28.44 6792.94   25.0512349.58   27.3713054.58   25.12
#Mann= 7 ,-1 , 0
1304.645    .068       03067.135    .118       03772.125    .068       0
4124.625    .118       0  4970.5     .04       0    5096    .118       0
12349.58    .068       0
#XS Ineff= 2 ,-1
 6673.6611226.11   27.23 3144.51 3829.82   23.05
Permanent Ineff=
       F       F
#Block Obstruct= 2 , 0
         1892.77   26.6312185.82            27.5
Bank Sta=4970.5,5096
XS Rating Curve= 0
Exp/Cntr=.3,.1

Type RM Length L Ch R = 1 ,91609.41,403.41,846.71,629.47
XS GIS Cut Line= 6
     3269108.122    13867865.758     3265082.632    13868126.181
      3265064.22    13868334.847     3262906.812    13868325.634
     3262430.733     13868161.17     3257912.306    13865780.773
#Sta/Elev= 30
 867.955   27.713150.185   25.563750.77523.560023991.00522.43001 4288.07   20.22
 4400.81   12.41  4522.3    8.99 4573.46    4.01 4686.69   14.81 4753.48   16.96
 4855.93    7.91    4957     8.2    4964     5.3    4973    -3.8    5001    -4.9
    5034      .7    5043     9.2 5206.16   11.07 5286.91   18.02 5537.15   17.25
 5745.02   22.91 6354.29   24.79 6430.25   27.62 6565.43   24.23 6752.09   24.69
 6796.53   27.44 6852.98   24.7411215.35   28.1412519.36   26.8412879.71   26.03
#Mann= 7 ,-1 , 0
 867.955    .068       03150.185    .118       03750.775    .068       0
3991.005    .118       0    4957     .04       0    5043    .118       0
12519.36    .068       0
#XS Ineff= 2 ,-1
 6461.23 7761.99   26.26 4150.29 4754.02   16.86
Permanent Ineff=
       F       F
Bank Sta=4957,5043
XS Rating Curve= 0
Exp/Cntr=.3,.1

Type RM Length L Ch R = 1 ,90762.7 ,378.79,637.38,541.97
XS GIS Cut Line= 3
     3269095.845    13867589.875     3262811.596    13867754.339
      3258076.77    13865538.406
#Sta/Elev= 30
  739.78   27.38 1509.37   26.69  1567.3    28.6 1623.57   26.73 3272.88   24.61
 3618.31   22.93 3963.73      22 4697.22   21.24 4771.66   18.76 4846.86    9.36
    4957     8.2    4964     5.3    4973    -3.8    5001    -4.9    5024    -2.6
    5034      .7    5037     4.3    5068     3.2 5173.51   12.34    5788   12.44
 5987.27   22.64 6245.07   26.66  6542.8   22.31 6577.07   24.67 6688.76   24.37
 6722.32   27.13 6781.61   24.15  8327.1   27.13 12023.6   27.5612253.89      27
#Mann= 7 ,-1 , 0
  739.78    .068       0 3272.88    .118       0 3618.31    .068       0
 3963.73    .118       0    4957     .04       0    5037    .118       0
 12023.6    .068       0
#XS Ineff= 1 ,-1
 6281.17 7770.17   25.87
Permanent Ineff=
       F
Bank Sta=4957,5037
XS Rating Curve= 0
Exp/Cntr=.3,.1

Type RM Length L Ch R = 1 ,90125.32,518.8,798.84,497.33
XS GIS Cut Line= 5
     3268967.352    13867213.098     3265140.969    13867315.476
     3265114.326    13867218.302     3265091.752    13867090.277
     3263071.921    13867324.675
#Sta/Elev= 30
1006.765   27.51 1727.87   26.92 1789.05   29.03  1845.7   26.993565.36523.48001
3687.20523.15001 3990.19   19.36 4087.52   12.674113.63514.15969 4276.08   21.16
 4670.67   20.27 4824.26    8.99    4935    10.1    4976     3.6    4985    -3.8
    5010    -9.7    5040    -4.8    5050     7.1    5065    10.9 5168.87   10.49
 5243.11   16.01 5293.29   14.93 5348.58    8.59 5825.74   19.57 6250.11   23.31
 6360.32   19.56 6406.33      23 6793.68   22.96 6997.13   27.94 7098.67   25.63
#Mann= 6 ,-1 , 0
1006.765    .068       03565.365    .118       03687.205    .068       0
4113.635    .118       0    4935     .04       0    5065    .118       0
#XS Ineff= 1 ,-1
 3721.27 4286.06   21.06
Permanent Ineff=
       F
#Block Obstruct= 2 , 0
                         7007.33           27.39
Bank Sta=4935,5065
XS Rating Curve= 0
Exp/Cntr=.3,.1

Type RM Length L Ch R = 1 ,89326.48,482.88,658.59,78.03
XS GIS Cut Line= 4
     3266957.988    13866776.877     3265456.798    13866786.469
     3265154.642    13866517.886     3263040.906    13866936.988
#Sta/Elev= 30
3249.975   25.85 3973.25    24.4 4399.15   20.914427.48519.56066 4549.07    8.34
 4665.29    6.77 4723.52    9.48 4861.67   10.52    4951     8.1    4960       7
    4970    -7.5    5000    -9.2    5024    -4.7    5038     5.5    5061     4.3
 5119.23   14.94 5151.56   19.18 5263.37   21.06  5387.2   20.03 5546.58   21.15
 5637.32   19.43  5827.6   18.92 6418.08   20.11 6471.65    18.3 6580.08   20.55
  6660.3   20.07 6714.54   15.43 6738.12   19.83 6767.62   22.53 7310.36    24.9
#Mann= 4 ,-1 , 0
3249.975    .068       04427.485    .118       0    4951     .04       0
    5038    .118       0
#XS Ineff= 1 ,-1
 6585.02 6841.78   20.02
Permanent Ineff=
       F
Bank Sta=4951,5038
XS Rating Curve= 0
Exp/Cntr=.3,.1

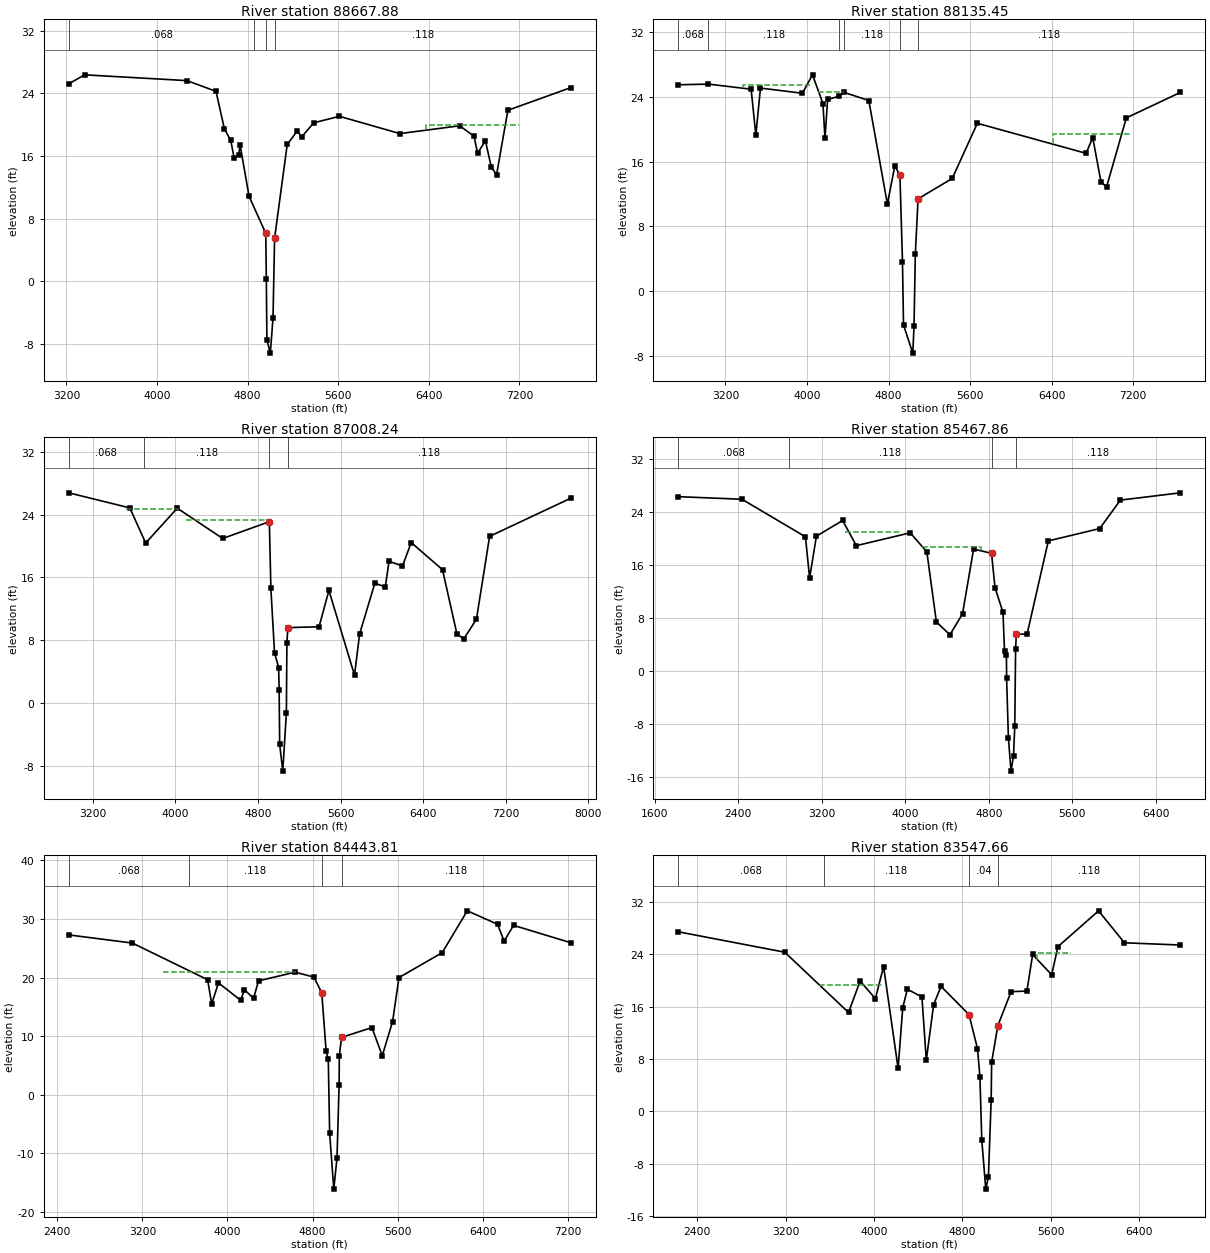
Type RM Length L Ch R = 1 ,88667.88,636.21,532.43,81.26
XS GIS Cut Line= 2
     3267373.303    13866057.765     3263010.684     13866845.46
#Sta/Elev= 30
 3220.09   25.21 3359.69   26.36 4263.62   25.62 4520.48   24.25 4594.45   19.46
 4650.81   17.97 4680.92   15.72 4721.85   16.13 4732.57   17.45 4812.04   10.86
    4960     6.1    4965      .3    4970    -7.5    5000    -9.2    5024    -4.7
    5038     5.5 5149.44   17.46 5239.04   19.21 5275.76   18.41 5383.73   20.23
 5610.79   21.06 6144.58   18.85 6672.14   19.85 6799.33   18.52 6830.49   16.33
 6899.66   17.94 6951.16   14.62 6998.16   13.57 7098.17   21.83 7653.25   24.72
#Mann= 4 ,-1 , 0
 3220.09    .068       04860.355    .118       0    4960     .04       0
    5038    .118       0
#XS Ineff= 1 ,-1
 6375.04 7200.22   19.96
Permanent Ineff=
       F
Bank Sta=4960,5038
XS Rating Curve= 0
Exp/Cntr=.3,.1

Type RM Length L Ch R = 1 ,88135.45,621.75,1127.21,201.4
XS GIS Cut Line= 6
     3267181.408     13865246.67      3265231.38       13865880.
     3265276.515    13865993.996     3265334.487    13866162.358
     3265394.448    13866330.836     3263040.906    13866766.405
#Sta/Elev= 30
 2737.74   25.52 3033.14    25.6 3451.46   24.97 3497.78   19.29 3543.01   25.11
 3953.98   24.47 4053.53   26.75 4155.79    23.2 4175.72   18.88 4201.84    23.7
  4313.2    24.1 4362.43   24.58 4605.81   23.57 4788.04   10.75 4860.95    15.5
 4910.97    14.3 4935.98     3.6 4945.98    -4.2 5037.01    -7.7 5049.02    -4.4
 5062.02     4.6 5089.03    11.4 5423.67   13.92  5670.2   20.75 6737.24   17.03
 6801.86   18.99 6883.62   13.44  6938.6   12.91 7131.41   21.42 7661.04   24.57
#Mann= 6 ,-1 , 0
 2737.74    .068       0 3033.14    .118       0  4313.2    .068       0
 4362.43    .118       0 4910.97     .04       0 5089.03    .118       0
#XS Ineff= 3 ,-1
 3370.73 4030.41   25.51 4108.02 4364.74   24.58 6408.31 7185.82   19.44
Permanent Ineff=
       F       F       F
Bank Sta=4910.97,5089.03
XS Rating Curve= 0
Exp/Cntr=.3,.1

Type RM Length L Ch R = 1 ,87008.24,195.54,1540.38,343.2
XS GIS Cut Line= 6
     3266902.273     13864502.31     3265258.478     13865246.67
     3265168.802    13865351.893     3264875.399    13865734.461
     3264808.761    13866270.165     3262932.353      13866549.3
#Sta/Elev= 30
 2967.76   26.78 3559.04   24.86 3712.76   20.38 4018.59   24.82 4458.65   20.96
  4910.5    23.1  4925.5    14.6  4960.5     6.4  5000.5     4.5  5005.5     1.7
  5010.5    -5.3  5040.5    -8.7  5075.5    -1.3  5080.5     7.6  5089.5     9.6
 5391.89     9.7  5487.6   14.33 5735.41    3.53 5784.85    8.79 5932.54   15.26
 6033.36   14.78 6069.84   18.05 6200.13   17.45 6284.74   20.44 6587.68   16.98
 6728.03    8.75 6795.34    8.18 6916.67   10.68 7043.92   21.23  7829.6   26.09
#Mann= 4 ,-1 , 0
 2967.76    .068       0 3697.04    .118       0  4910.5     .04       0
  5089.5    .118       0
#XS Ineff= 3 ,-1
 3518.34 4031.78   24.78 4105.13 4897.31   23.29 6284.09 7040.29   20.28
Permanent Ineff=
       F       F       F
#Block Obstruct= 2 , 0
                         7523.23           24.91
Bank Sta=4910.5,5089.5
XS Rating Curve= 0
Exp/Cntr=.3,.1

Type RM Length L Ch R = 1 ,85467.86,74.37,1024.06,790.41
XS GIS Cut Line= 6
     3266840.243    13864114.623     3264547.274    13865432.378
     3264474.358    13865781.336     3264388.617    13865850.744
     3264167.066    13866026.128     3262777.278     13866301.18
#Sta/Elev= 30
 1824.89   26.36 2434.07   25.97 3042.72    20.3 3082.76   14.07 3147.97   20.39
 3398.88   22.76 3530.79   18.96 4047.11    20.9 4206.55   18.01 4297.86    7.43
 4427.72     5.5 4548.13    8.66 4654.43   18.44 4826.04   17.81    4860    12.6
    4936     8.9    4951       3    4969     2.5    4971    -1.1    4988   -10.1
    5013   -15.1    5037   -12.8    5049    -8.3    5057     3.3    5064     5.6
 5167.02     5.6 5370.81   19.68 5862.89   21.54 6061.57   25.84 6635.67   26.94
#Mann= 4 ,-1 , 0
 1824.89    .068       0 2883.26    .118       0 4826.04     .04       0
    5064    .118       0
#XS Ineff= 3 ,-1
 2650.37 3383.86   22.39 3420.54 3941.32   20.99 4163.29 4724.31   18.83
Permanent Ineff=
       F       F       F
Bank Sta=4826.04,5064
XS Rating Curve= 0
Exp/Cntr=.3,.1

Type RM Length L Ch R = 1 ,84443.81,508.69,896.15,522.27
XS GIS Cut Line= 6
     3266778.213    13863959.548     3264828.524    13865203.211
     3264711.518    13865148.932     3264615.091    13865109.973
     3264516.024    13865078.211     3262529.158    13865665.373
#Sta/Elev= 30
 2507.11   27.29 3105.43    25.9 3813.08   19.64 3851.38   15.52 3915.24    19.1
  4123.6   16.14 4159.97   17.92 4245.27   16.46  4291.8   19.45 4637.39   20.93
 4812.57   20.09    4887    17.4    4928     7.4    4948     6.1    4961    -6.6
    5000   -16.1    5030   -10.8    5050     1.7    5052     6.7    5073     9.8
 5358.36   11.47  5455.9    6.68 5552.96   12.49 5613.04   20.01 6019.13   24.25
 6255.62    31.4 6540.01   29.11 6602.22   26.23 6690.78   28.92 7228.51   25.96
#Mann= 4 ,-1 , 0
 2507.11    .068       0 3640.25    .118       0    4887     .04       0
    5073    .118       0
#XS Ineff= 1 ,-1
 3393.64 4640.59   20.99
Permanent Ineff=
       F
Bank Sta=4887,5073
XS Rating Curve= 0
Exp/Cntr=.3,.1

Type RM Length L Ch R = 1 ,83547.66,710.29,652.11,184.53
XS GIS Cut Line= 6
      3266731.69    13863587.368     3264495.191    13864776.128
     3264330.913    13864718.805     3264209.887    13864677.132
     3264042.066    13864619.878     3262637.711    13865231.163
#Sta/Elev= 30
 2228.32   27.46 3191.47   24.34 3768.67   15.12 3873.66   19.92 4011.74   17.25
 4086.09   22.15  4217.5    6.58 4259.51   15.85 4301.23   18.67 4432.98   17.51
 4472.61    7.83 4539.16   16.31 4605.71   19.12    4859    14.8    4936     9.6
    4958     5.3    4975    -4.4    5011   -11.9    5035     -10    5060     1.8
    5064     7.5    5120    13.1 5240.43   18.31 5383.39   18.39 5435.14   23.99
 5607.42   20.89 5664.25   25.19 6031.85   30.67 6266.28   25.78 6772.06   25.44
#Mann= 4 ,-1 , 0
 2228.32    .068       0    3546    .118       0    4859     .04       0
    5120    .118       0
#XS Ineff= 3 ,-1
    5478 5783.62   24.16 3510.34 4073.51   19.27 4107.34 4592.71   17.41
Permanent Ineff=
       F       F       F
Bank Sta=4859,5120
XS Rating Curve= 0
Exp/Cntr=.3,.1

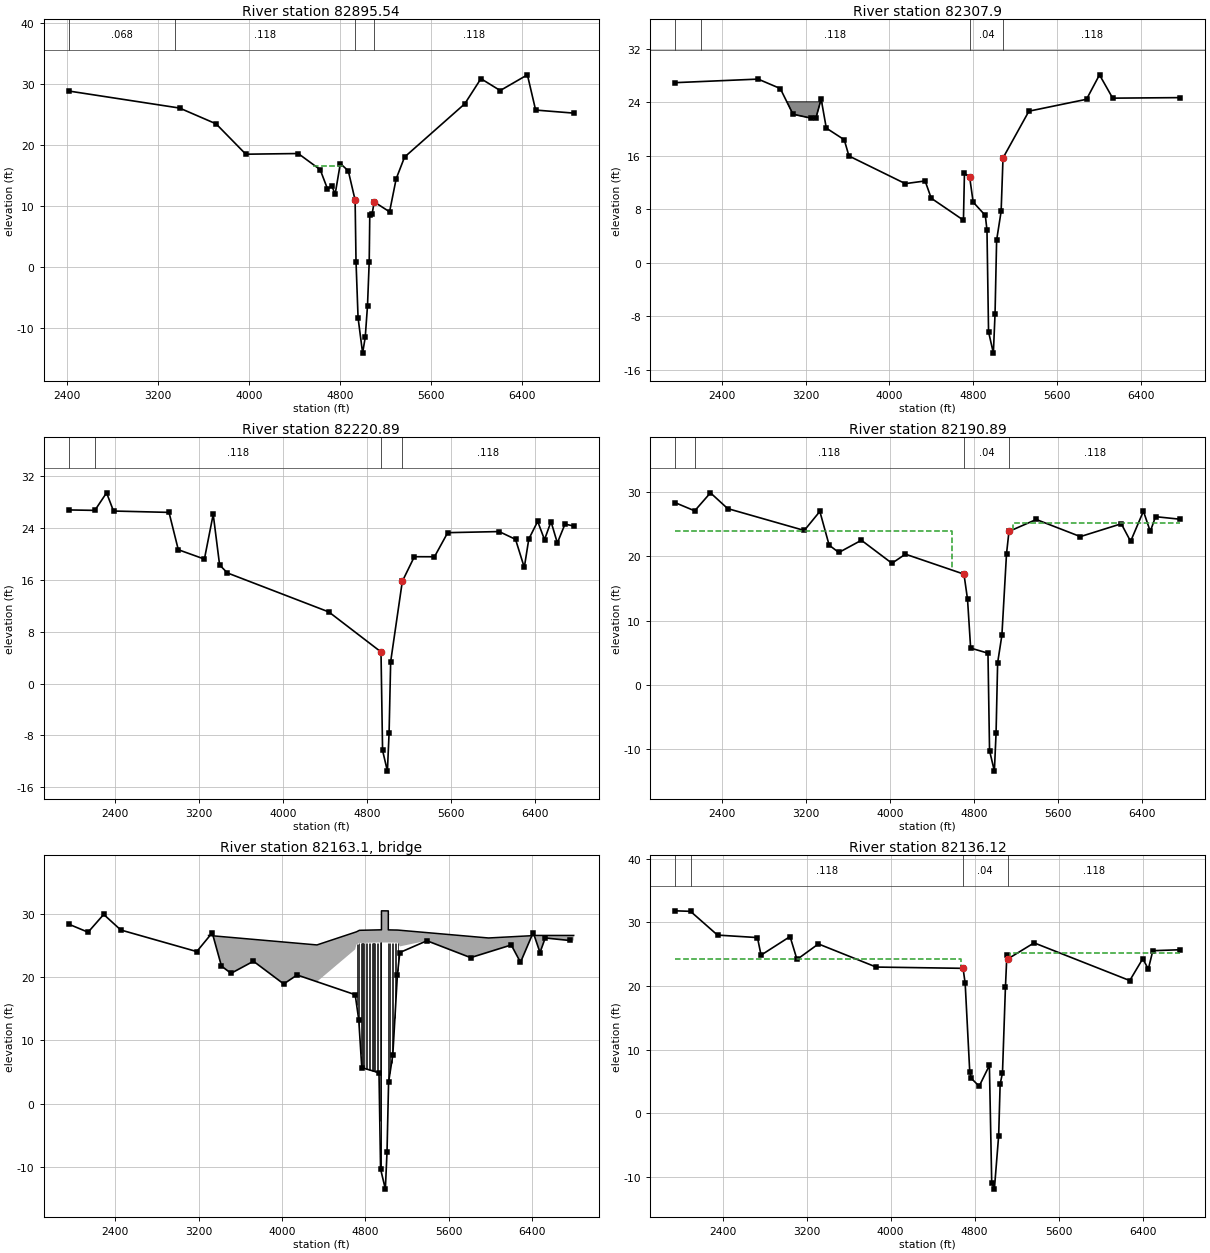
Type RM Length L Ch R = 1 ,82895.54,533.39,587.64,390.71
XS GIS Cut Line= 6
     3266592.123    13862703.441     3264607.163     13863944.04
     3264501.977    13864083.283     3264422.557    13864184.936
     3264338.941    13864291.753     3262823.801    13864967.535
#Sta/Elev= 30
 2418.77   28.79 3391.88      26 3712.93   23.41 3974.28   18.43 4435.21   18.54
  4628.2    15.9 4692.33   12.76 4732.17   13.19 4759.53   11.83  4805.5    16.9
  4875.5    15.7  4935.5    10.9  4943.5      .8  4961.5    -8.4  5001.5   -14.2
  5024.5   -11.6  5044.5    -6.4  5059.5      .8  5064.5     8.5  5084.5     8.6
  5103.5    10.6 5238.45    8.98 5296.59    14.4 5370.37   17.96 5899.91    26.7
 6041.77   30.82 6211.36   28.87 6450.42   31.45 6522.83   25.67  6857.7   25.17
#Mann= 4 ,-1 , 0
 2418.77    .068       0 3350.95    .118       0  4935.5     .04       0
  5103.5    .118       0
#XS Ineff= 1 ,-1
  4564.4 4827.87   16.56
Permanent Ineff=
       F
Bank Sta=4935.5,5103.5
XS Rating Curve= 0
Exp/Cntr=.3,.1

Type RM Length L Ch R = 1 ,82307.9 ,30.04,87.01,105.59
XS GIS Cut Line= 6
     3266306.927    13861972.909     3264128.742    13863649.978
     3263989.533    13863807.517     3263878.659    13863935.063
     3263834.754    13863977.374     3262551.897    13864979.606
#Sta/Elev= 30
 1957.97   26.97  2747.7    27.5 2958.98   26.09 3080.51   22.24 3253.41   21.66
 3298.54   21.63 3349.09   24.52 3398.19   20.17 3569.32   18.43 3614.26      16
 4151.94   11.86 4341.24   12.26 4399.44    9.68 4706.98    6.39  4716.5    13.4
  4766.5    12.8  4799.5     9.1  4915.5     7.1  4931.5     4.9  4946.5   -10.3
  4992.5   -13.5  5008.5    -7.6  5023.5     3.4  5066.5     7.7  5084.5    15.7
 5331.61    22.7 5881.26   24.48 6005.31   28.14 6131.19   24.65 6775.13   24.73
#Mann= 4 ,-1 , 0
 1957.97    .068       0 2198.83    .118       0  4766.5     .04       0
  5084.5    .118       0
#Block Obstruct= 1 ,-1
 3020.98 3356.64    24.1
Bank Sta=4766.5,5084.5
XS Rating Curve= 0
Exp/Cntr=.3,.1

Type RM Length L Ch R = 1 ,82220.89,30.14,30,30.18
XS GIS Cut Line= 6
     3266275.442     13861943.58     3264100.701    13863635.184
     3263920.638    13863772.319     3263822.869    13863851.261
      3263786.97    13863887.279     3262480.016    13864890.379
#Sta/Elev= 30
 1960.48   26.82  2207.3   26.75 2319.06   29.46 2385.06   26.65 2913.46   26.44
 3001.76   20.68 3250.36   19.23 3334.24   26.14 3394.96   18.34 3468.24    17.1
  4435.1   11.07  4931.5     4.9  4946.5   -10.3  4992.5   -13.5  5008.5    -7.6
  5023.5     3.4  5134.5    15.8  5248.9    19.6  5440.5   19.59 5566.54   23.31
 6056.16   23.48 6212.26   22.28 6295.62   17.94 6338.42   22.32    6423   25.05
 6488.18   22.23 6550.04   25.02 6610.34   21.72 6682.98   24.63 6766.04   24.34
#Mann= 4 ,-1 , 0
 1960.48    .068       0  2207.3    .118       0  4931.5     .04       0
  5134.5    .118       0
#XS Ineff= 1 ,-1
 5578.85 6390.63    23.3
Permanent Ineff=
       F
#Block Obstruct= 2 , 0
         3342.66   24.57 6426.57           25.03
Bank Sta=4931.5,5134.5
XS Rating Curve= 0
Exp/Cntr=.5,.3

Type RM Length L Ch R = 1 ,82190.89,54.94,54.76,54.98
XS GIS Cut Line= 6
     3266257.023      13861919.9     3264082.403     13863611.41
     3263902.123    13863748.711     3263802.763    13863828.937
     3263767.127    13863864.692      3262461.75    13864866.581
#Sta/Elev= 30
  1955.8   28.37 2139.88   27.11 2289.62   29.92  2453.7   27.46 3182.78   24.05
 3331.12   27.02 3419.56   21.76 3511.64   20.61 3726.66   22.52  4017.3   18.93
 4145.56   20.35 4703.06   17.23    4737    13.3  4766.5     5.7  4931.5     4.9
  4946.5   -10.3  4992.5   -13.5  5008.5    -7.6  5023.5     3.4    5064     7.7
    5108    20.4 5131.42    23.9 5391.18   25.76 5811.08   23.09 6200.52   25.09
 6289.34   22.35 6411.42   27.06 6476.56   23.89 6526.66    26.2 6761.16    25.8
#Mann= 4 ,-1 , 0
  1955.8    .068       0 2139.88    .118       0 4703.06     .04       0
 5131.42    .118       0
#XS Ineff= 2 , 0
       0    4590      24    5166       0    25.2
Permanent Ineff=
       F       F
#Block Obstruct= 2 , 0
                         6229.83           24.57
Bank Sta=4703.06,5131.42
XS Rating Curve= 0
Exp/Cntr=.5,.3

Type RM Length L Ch R = 3 ,82163.1 ,,,
BEGIN DESCRIPTION:
Southern Pacific RR (Just South of I-10)
Southern Pacific RR
END DESCRIPTION:
Bridge Culvert--1,0,-1,-1, 0
Deck Dist Width WeirC Skew NumUp NumDn MinLoCord MaxHiCord MaxSubmerge Is_Ogee
20.4,12,2.6,0, 12, 12, , , .95, 0, 0,0,,
    3296    4336  4714.7  4743.7  4955.1 4955.11 5020.99    5021  5111.4    5982
    6443    6800
    26.6    25.1   27.17   27.41   27.49   30.49   30.48   27.48   27.45    26.2
    26.6    26.6
       0       0   25.17   25.41   25.49   25.49   25.48   25.48   25.45       0
       0       0
    3296    4336  4714.7  4743.7  4955.1 4955.11 5020.99    5021  5111.4    5982
    6443    6800
    26.6    25.1   27.17   27.41   27.49   30.49   30.48   27.48   27.45    26.2
    26.6    26.6
       0       0   25.17   25.41   25.49   25.49   25.48   25.48   25.45       0
       0       0
Pier Skew, UpSta & Num, DnSta & Num=  ,4717.4, 2 ,4714.7, 2 , 0 , 0 , 0 ,,
       1       1
       0      28
       1       1
       0      28
Pier Skew, UpSta & Num, DnSta & Num=  ,4729, 2 ,4729, 2 , 0 , 0 , 0 ,,
       1       1
       0      28
       1       1
       0      28
Pier Skew, UpSta & Num, DnSta & Num=  ,4742.9, 2 ,4742.9, 2 , 0 , 0 , 0 ,,
       1       1
       0      28
       1       1
       0      28
Pier Skew, UpSta & Num, DnSta & Num=  ,4758.4, 2 ,4758.4, 2 , 0 , 0 , 0 ,,
       1       1
       0      28
       1       1
       0      28
Pier Skew, UpSta & Num, DnSta & Num=  ,4773.6, 2 ,4773.6, 2 , 0 , 0 , 0 ,,
       1       1
       0      28
       1       1
       0      28
Pier Skew, UpSta & Num, DnSta & Num=  ,4788.8, 2 ,4788.8, 2 , 0 , 0 , 0 ,,
       1       1
       0      28
       1       1
       0      28
Pier Skew, UpSta & Num, DnSta & Num=  ,4803.8, 2 ,4803.8, 2 , 0 , 0 , 0 ,,
       1       1
       0      28
       1       1
       0      28
Pier Skew, UpSta & Num, DnSta & Num=  ,4819.8, 2 ,4819.8, 2 , 0 , 0 , 0 ,,
       1       1
       0      28
       1       1
       0      28
Pier Skew, UpSta & Num, DnSta & Num=  ,4834.9, 2 ,4834.9, 2 , 0 , 0 , 0 ,,
       1       1
       0      28
       1       1
       0      28
Pier Skew, UpSta & Num, DnSta & Num=  ,4848.3, 2 ,4848.3, 2 , 0 , 0 , 0 ,,
       1       1
       0      28
       1       1
       0      28
Pier Skew, UpSta & Num, DnSta & Num=  ,4863.9, 2 ,4863.9, 2 , 0 , 0 , 0 ,,
       1       1
       0      28
       1       1
       0      28
Pier Skew, UpSta & Num, DnSta & Num=  ,4878.9, 2 ,4878.9, 2 , 0 , 0 , 0 ,,
       1       1
       0      28
       1       1
       0      28
Pier Skew, UpSta & Num, DnSta & Num=  ,4894.1, 2 ,4894.1, 2 , 0 , 0 , 0 ,,
       1       1
       0      28
       1       1
       0      28
Pier Skew, UpSta & Num, DnSta & Num=  ,4909.2, 2 ,4909.2, 2 , 0 , 0 , 0 ,,
       1       1
       0      28
       1       1
       0      28
Pier Skew, UpSta & Num, DnSta & Num=  ,4925.4, 2 ,4925.4, 2 , 0 , 0 , 0 ,,
       1       1
       0      28
       1       1
       0      28
Pier Skew, UpSta & Num, DnSta & Num=  ,4939, 2 ,4939, 2 , 0 , 0 , 0 ,,
       1       1
       0      28
       1       1
       0      28
Pier Skew, UpSta & Num, DnSta & Num=  ,4951, 2 ,4951, 2 , 0 , 0 , 0 ,,
       1       1
       0      28
       1       1
       0      28
Pier Skew, UpSta & Num, DnSta & Num=  ,4954, 2 ,4954, 2 , 0 , 0 , 0 ,,
       1       1
       0      28
       1       1
       0      28
Pier Skew, UpSta & Num, DnSta & Num=  ,5020, 2 ,5020, 2 , 0 , 0 , 0 ,,
       1       1
       0      28
       1       1
       0      28
Pier Skew, UpSta & Num, DnSta & Num=  ,5024.5, 2 ,5024.5, 2 , 0 , 0 , 0 ,,
       1       1
       0      28
       1       1
       0      28
Pier Skew, UpSta & Num, DnSta & Num=  ,5037, 2 ,5037, 2 , 0 , 0 , 0 ,,
       1       1
       0      28
       1       1
       0      28
Pier Skew, UpSta & Num, DnSta & Num=  ,5052.5, 2 ,5052.5, 2 , 0 , 0 , 0 ,,
       1       1
       0      28
       1       1
       0      28
Pier Skew, UpSta & Num, DnSta & Num=  ,5068.8, 2 ,5068.8, 2 , 0 , 0 , 0 ,,
       1       1
       0      28
       1       1
       0      28
Pier Skew, UpSta & Num, DnSta & Num=  ,5084.4, 2 ,5084.4, 2 , 0 , 0 , 0 ,,
       1       1
       0      28
       1       1
       0      28
Pier Skew, UpSta & Num, DnSta & Num=  ,5098.3, 2 ,5098.3, 2 , 0 , 0 , 0 ,,
       1       1
       0      28
       1       1
       0      28
Pier Skew, UpSta & Num, DnSta & Num=  ,5112.2, 2 ,5112.2, 2 , 0 , 0 , 0 ,,
       1       1
       0      28
       1       1
       0      28
BR Coef=-1 , 1 , 1 ,.9, 0 ,,,.8,0,1.2,0,
WSPro=,,,, 1 ,,,, 0 ,,,, 0 ,,,,-1 ,-1 ,-1 , 0 , 0 , 0 , 0 , 0
BC Design=,, 0 ,, 0 ,,,,,,
BC HTab HWMax=29.92

Type RM Length L Ch R = 1 ,82136.12,120.57,120.04,120.7
XS GIS Cut Line= 6
     3266220.066    13861879.368     3264045.567    13863570.784
      3263865.07     13863708.25      3263764.12     13863789.76
     3263728.745    13863825.253     3262424.947     13864825.93
#Sta/Elev= 30
 1951.12   31.79 2095.27   31.71 2352.14   27.98 2732.53   27.59 2766.58   24.83
  3042.8   27.75 3108.88   24.15 3312.56   26.59 3862.81   22.96 4688.57   22.76
 4689.57   22.78 4709.73   20.38 4753.33    6.48 4768.55    5.47 4843.05    4.25
 4940.24    7.52 4962.35  -10.87 4987.68  -11.91 5028.48    -3.5 5042.46    4.54
 5064.87    6.36 5092.86   19.77 5106.78   24.85 5113.01   24.21 5365.76   26.76
 6276.29   20.84 6400.49   24.28 6453.02   22.63 6495.82   25.53 6756.28   25.68
#Mann= 4 ,-1 , 0
 1951.12    .068       0 2095.27    .118       0 4689.57     .04       0
 5113.01    .118       0
#XS Ineff= 2 , 0
       0    4673   24.15    5137       0    25.2
Permanent Ineff=
       F       F
Bank Sta=4688.57,5113.01
XS Rating Curve= 0
Exp/Cntr=.5,.3

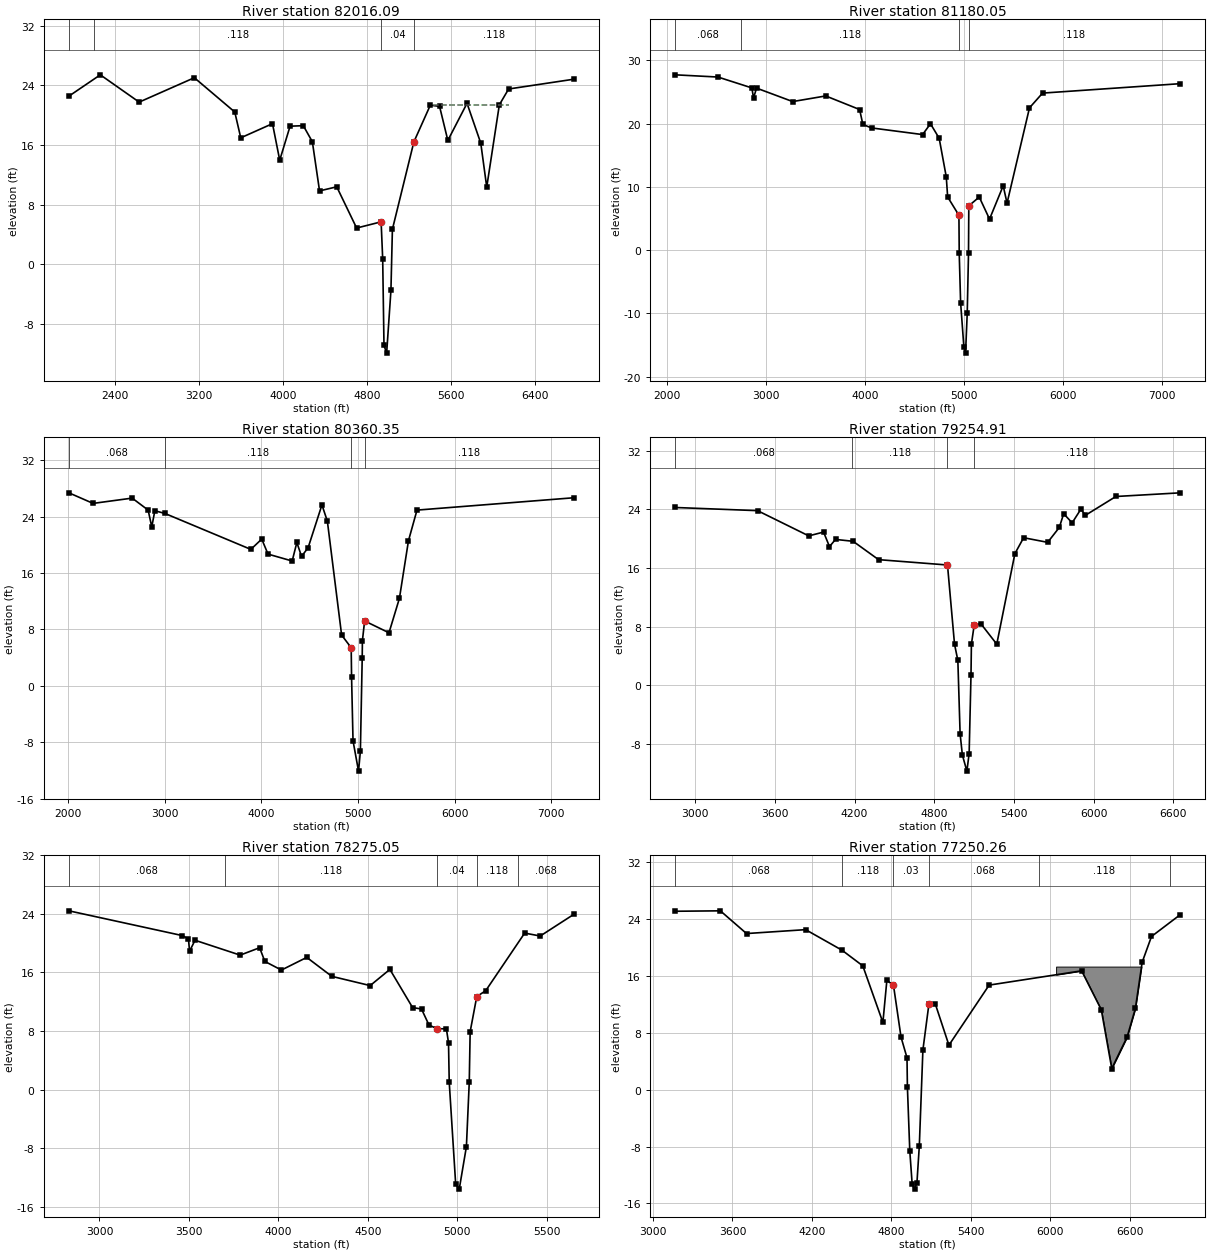
Type RM Length L Ch R = 1 ,82016.09,526.68,836.04,771.71
XS GIS Cut Line= 6
      3266146.39    13861784.648     3263972.373    13863475.689
     3263791.009    13863613.816     3263683.697    13863700.463
     3263649.369    13863734.904     3262351.885    13864730.736
#Sta/Elev= 30
 1963.64   22.56 2262.54   25.42 2632.38   21.76 3157.54   25.03 3542.24   20.43
 3599.14   16.97 3901.28   18.87 3970.02   13.97 4068.58   18.53 4194.44    18.6
 4280.66   16.44 4349.06    9.85  4512.7    10.4  4701.9    4.87 4935.13     5.7
 4950.04     .73 4962.35  -10.87 4987.68  -11.91 5028.48    -3.5 5042.46     4.7
 5246.78   16.42 5403.26   21.35 5491.26   21.19 5570.08   16.62 5752.66    21.6
 5883.52   16.25 5940.26   10.36 6060.28    21.4 6148.66   23.52 6768.02   24.83
#Mann= 4 ,-1 , 0
 1963.64    .068       0 2203.86    .118       0 4935.13     .04       0
 5246.78    .118       0
#XS Ineff= 2 ,-1
 5437.65 6149.14   21.34 3515.22 4196.72   18.43
Permanent Ineff=
       F       F
#Block Obstruct= 2 , 0
         3046.45   25.11
Bank Sta=4935.13,5246.78
XS Rating Curve= 0
Exp/Cntr=.3,.1

Type RM Length L Ch R = 1 ,81180.05,430.83,819.69,716.21
XS GIS Cut Line= 6
     3265770.225    13861369.796     3263656.649    13863057.378
     3263492.568    13863056.131     3263392.629    13863052.641
     3263275.144    13863049.861     3261676.246    13864285.205
#Sta/Elev= 30
 2081.48   27.72 2512.42   27.37  2855.2   25.65 2872.29   24.06 2902.63   25.62
 3268.12   23.49 3602.54   24.38 3945.55   22.23 3978.03   19.87 4065.98   19.32
 4582.44   18.27 4662.15   19.98 4750.14   17.69 4822.01   11.58    4836     8.4
    4950     5.5    4953     -.5    4967    -8.3    5000   -15.3    5017   -16.3
    5034     -10    5047     -.5    5050       7 5155.57    8.39 5259.68     4.9
 5397.93   10.17  5436.7    7.42 5663.84    22.5 5796.23   24.83 7188.27   26.32
#Mann= 4 ,-1 , 0
 2081.48    .068       0 2745.36    .118       0    4950     .04       0
    5050    .118       0
Bank Sta=4950,5050
XS Rating Curve= 0
Exp/Cntr=.3,.1

Type RM Length L Ch R = 1 ,80360.35,1690.72,1105.45,617.58
XS GIS Cut Line= 6
      3265553.12    13861044.138     3263521.638    13862672.426
     3263262.092     13862492.92     3263146.855    13862415.192
     3263057.691    13862354.253     3261412.618    13863587.368
#Sta/Elev= 30
  2010.4   27.37 2260.64   25.87 2664.91   26.62 2830.08   24.92 2867.44   22.54
 2899.45   24.83 3002.58   24.45 3892.48   19.35 4005.16   20.81 4070.05   18.68
 4319.98    17.7 4368.46   20.33 4416.71   18.36 4484.52   19.57 4627.97   25.66
 4684.04   23.35  4831.5     7.2  4930.5     5.4  4934.5     1.2  4949.5    -7.8
  5006.5   -12.1  5025.5    -9.3  5044.5     3.9  5046.5     6.4  5069.5     9.2
 5321.51    7.52 5429.49   12.41 5523.12   20.58 5611.17   24.92 7232.41   26.67
#Mann= 4 ,-1 , 0
  2010.4    .068       0 3002.58    .118       0  4930.5     .04       0
  5069.5    .118       0
Bank Sta=4930.5,5069.5
XS Rating Curve= 0
Exp/Cntr=.3,.1

Type RM Length L Ch R = 1 ,79254.91,527.95,979.86,761.33
XS GIS Cut Line= 6
     3263436.347    13860191.226     3263033.152    13860392.823
     3262510.816    13861781.336      3262450.46    13861877.536
     3262304.299    13862160.678      3261187.76    13863060.113
#Sta/Elev= 30
 2850.94   24.24 3469.72   23.81 3855.13   20.37  3966.6   20.89 4011.11   18.91
 4056.54   19.89 4189.17   19.63 4380.65   17.13  4899.5    16.4  4952.5     5.6
  4977.5     3.4  4994.5    -6.6  5011.5    -9.5  5045.5   -11.7  5062.5    -9.3
  5076.5     1.4  5079.5     5.6  5100.5     8.2  5150.5     8.4 5270.48    5.61
 5406.91   17.95 5472.68   20.12 5653.66   19.49 5741.29   21.52 5774.12   23.39
 5838.02   22.15 5903.35      24  5938.2   23.18 6167.24   25.74 6651.23   26.24
#Mann= 4 ,-1 , 0
 2850.94    .068       0 4181.04    .118       0  4899.5     .04       0
  5100.5    .118       0
Bank Sta=4899.5,5100.5
XS Rating Curve= 0
Exp/Cntr=.3,.1

Type RM Length L Ch R = 1 ,78275.05,373.05,1024.79,1138.28
XS GIS Cut Line= 6
     3262707.494    13860377.316     3261730.522    13861943.573
      3261533.11    13862027.056      3261329.13     13862109.47
     3261218.775    13862145.171      3260815.58    13862284.738
#Sta/Elev= 30
 2829.14   24.41  3463.2   21.03 3497.52   20.57 3503.99    18.9 3534.42   20.39
 3786.94   18.36 3895.73   19.37 3924.87    17.5 4017.55   16.32 4159.27   18.05
 4299.34   15.46 4513.86    14.2 4624.13   16.41    4751    11.2    4801      11
    4843     8.8    4890     8.3    4940     8.3    4952     6.4    4956       1
    4992   -12.9    5012   -13.6    5052    -7.8    5068       1    5073     7.9
    5110    12.7    5160    13.5 5377.88   21.37 5464.95   20.97 5652.11   23.92
#Mann= 5 ,-1 , 0
 2829.14    .068       0 3704.26    .118       0    4890     .04       0
    5110    .118       0 5341.58    .068       0
Bank Sta=4890,5110
XS Rating Curve= 0
Exp/Cntr=.3,.1

Type RM Length L Ch R = 1 ,77250.26,941.08,1215.02,1048.96
XS GIS Cut Line= 6
     3262676.479    13860036.151     3261739.983    13861291.753
     3261577.786    13861209.019     3261429.485    13861136.688
     3261328.524    13861093.836     3259541.676    13861123.744
#Sta/Elev= 30
 3169.18   25.13 3508.69   25.19 3706.17   21.99 4152.31   22.54 4426.56   19.65
 4583.95   17.44 4735.56    9.47  4765.5    15.4  4815.5    14.7  4872.5     7.4
  4917.5     4.5  4920.5      .4  4938.5    -8.6  4956.5   -13.3  4974.5     -14
  4992.5   -13.1  5010.5    -7.9  5037.5     5.6  5082.5      12  5132.5      12
 5233.91    6.27 5537.36   14.73  6235.6   16.74 6383.98   11.26 6463.02    2.98
 6578.64    7.41 6641.25   11.44 6692.52   17.95 6762.94   21.58 6979.42   24.64
#Mann= 6 ,-1 , 0
 3169.18    .068       0 4426.56    .118       0  4815.5     .03       0
  5082.5    .068       0 5912.55    .118       0 6903.21    .068       0
#Block Obstruct= 1 ,-1
  6042.9  6690.5   17.34
Bank Sta=4815.5,5082.5
XS Rating Curve= 0
Exp/Cntr=.3,.1