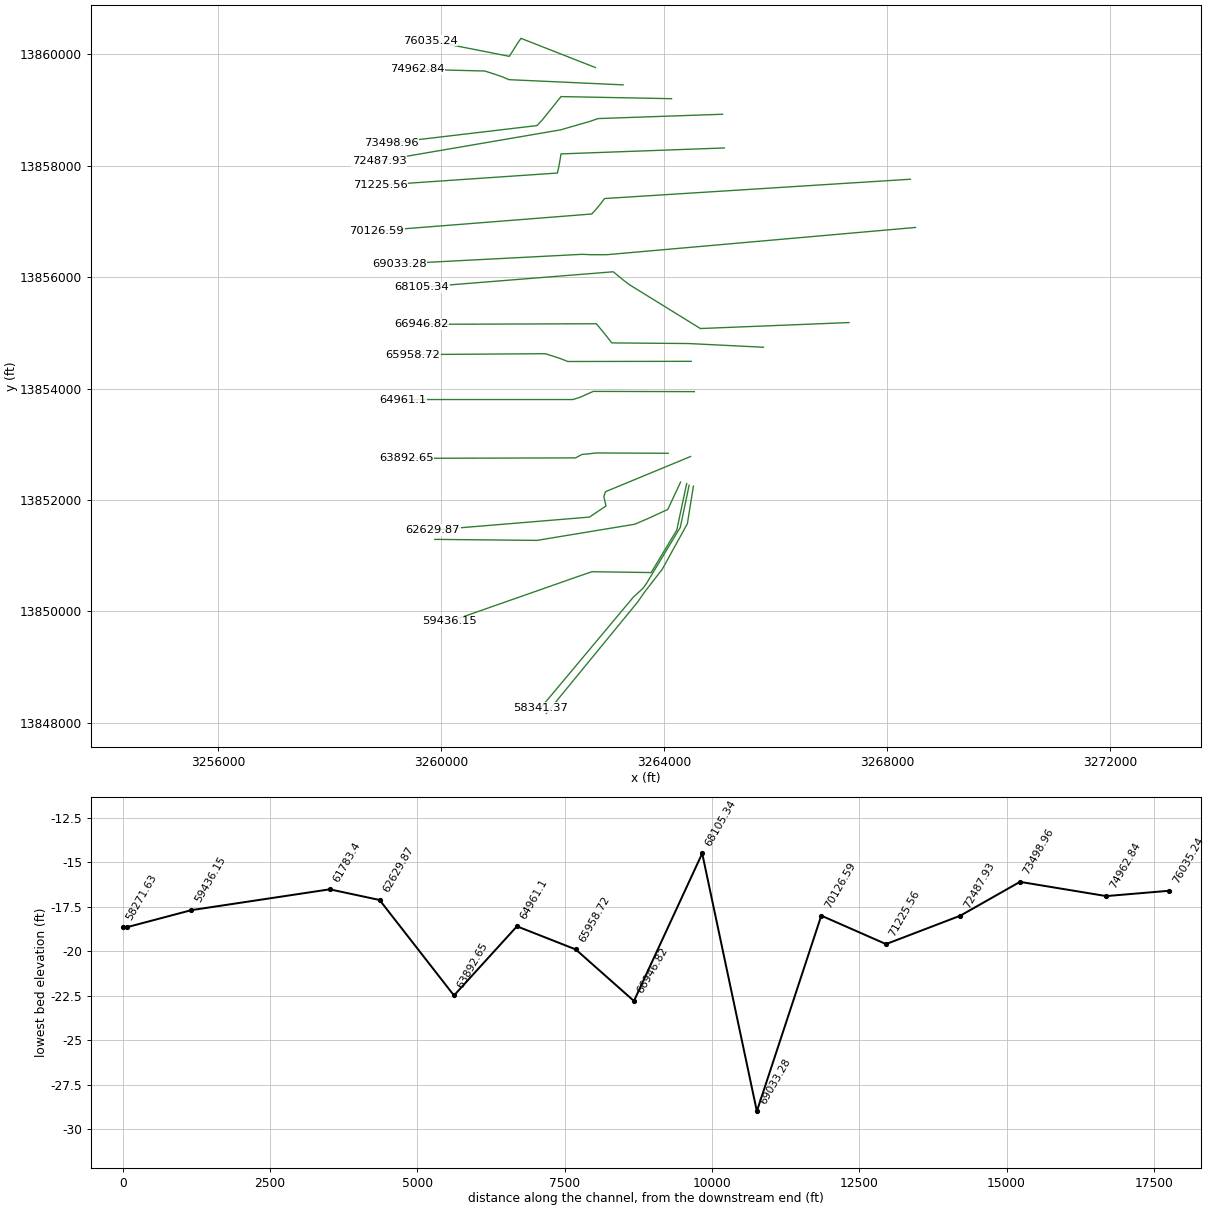
HEC-RAS study Q100-00-00.prj: Q100-00-00

--- Q100-00-00.g01 (geometry) --- (continued)

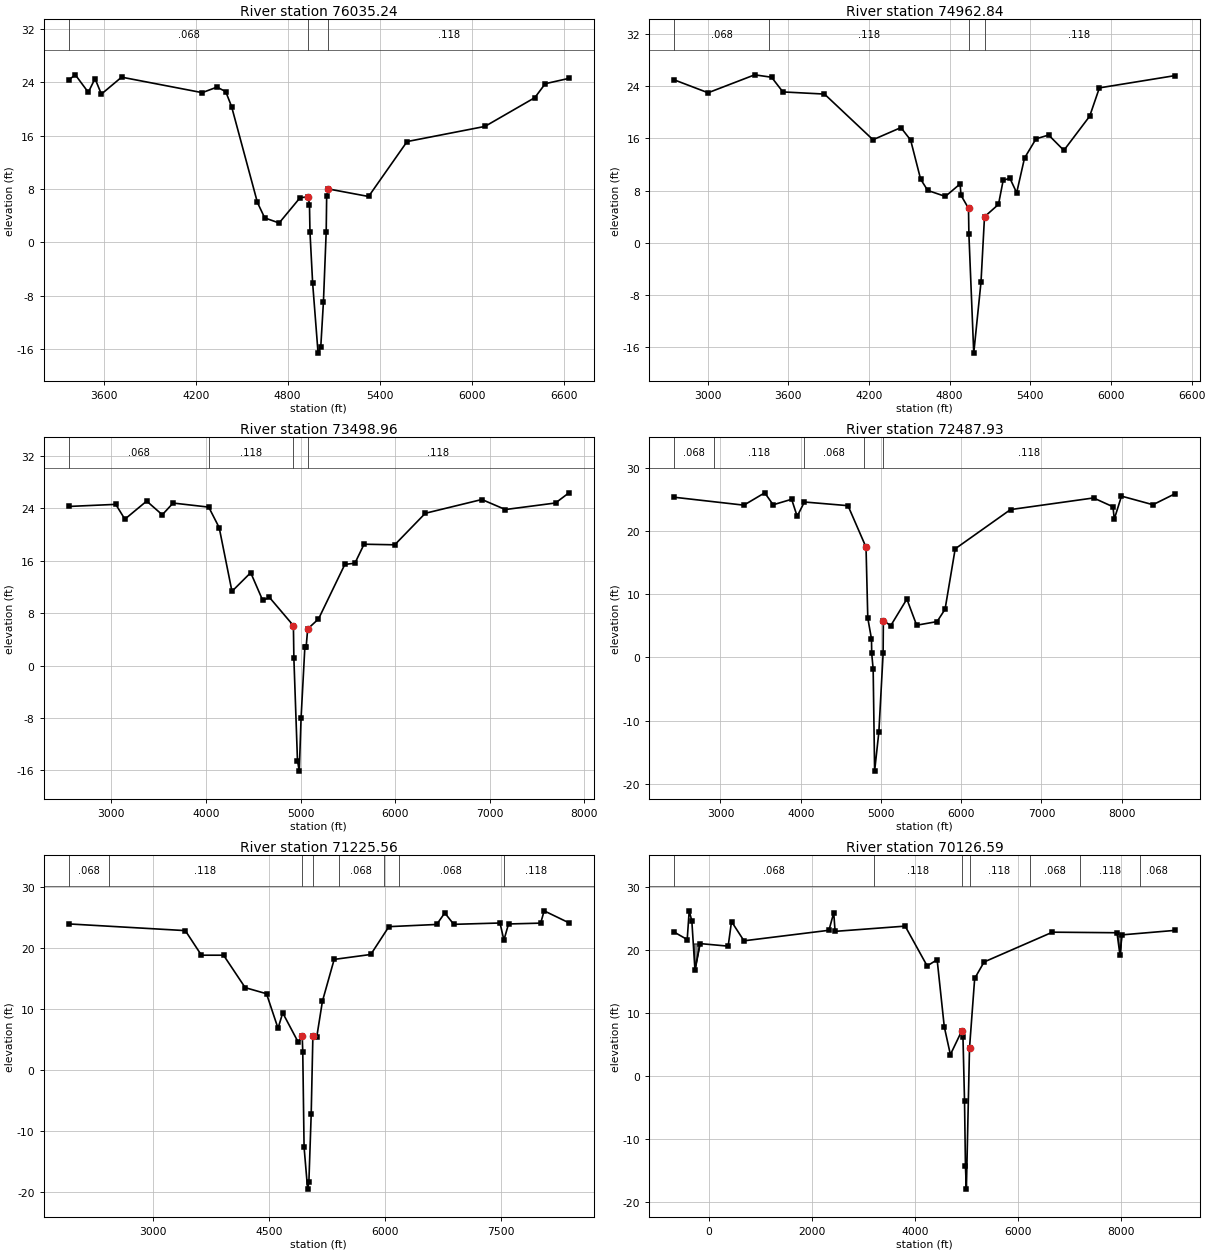
Type RM Length L Ch R = 1 ,76035.24,627.29,1072.4,382.77
XS GIS Cut Line= 6
     3262769.524    13859757.016     3261432.691    13860281.336
      3261361.53    13860176.326     3261292.111    13860065.232
     3261224.358     13859958.42     3259807.592    13860237.748
#Sta/Elev= 30
 3371.09   24.33  3414.5    25.1 3499.06   22.48 3542.99   24.53 3584.41   22.21
 3716.45   24.75 4242.55   22.43  4338.9   23.26 4395.93   22.58 4434.01   20.35
 4602.72    5.97  4650.3    3.66 4744.41     2.9  4881.5     6.7  4934.5     6.8
  4942.5     5.6  4945.5     1.6    4963    -6.1  4998.5   -16.6    5016   -15.7
  5033.5    -8.9  5051.5     1.6  5054.5     6.9  5065.5       8 5328.03    6.87
  5579.3    15.1 6087.28   17.37 6412.75   21.68 6480.89   23.77 6635.45   24.57
#Mann= 3 ,-1 , 0
 3371.09    .068       0  4934.5     .03       0  5065.5    .118       0
Bank Sta=4934.5,5065.5
XS Rating Curve= 0
Exp/Cntr=.3,.1

Type RM Length L Ch R = 1 ,74962.84,504.82,1463.88,1162.89
XS GIS Cut Line= 6
     3263265.764    13859446.866     3261218.775    13859539.911
     3261092.666    13859593.227      3260980.15     13859631.97
     3260784.565    13859694.986      3259574.98    13859726.001
#Sta/Elev= 30
 2752.83   24.98 3003.64   23.01 3350.37   25.76 3475.86   25.39 3560.18   23.14
  3869.3   22.81 4230.16   15.81 4437.73   17.67 4510.11   15.76  4584.3    9.77
 4637.09    8.04  4768.5    7.12  4878.4    9.04  4884.5     7.3  4940.5     5.3
  4943.5     1.3  4979.5   -16.9  5033.5      -6  5059.5       4  5163.5     5.9
  5198.5     9.6  5248.5     9.9 5298.77    7.68 5357.09      13 5442.85   15.95
 5536.55   16.53 5649.75   14.18  5841.8   19.42 5913.92   23.76 6473.32   25.63
#Mann= 4 ,-1 , 0
 2752.83    .068       0 3459.72    .118       0  4940.5     .04       0
  5059.5    .118       0
Bank Sta=4940.5,5059.5
XS Rating Curve= 0
Exp/Cntr=.3,.1

Type RM Length L Ch R = 1 ,73498.96,570.49,1011.03,215.65
XS GIS Cut Line= 6
     3264134.184    13859198.746     3262151.346    13859236.458
     3261906.306    13858929.659     3261811.279     13858812.31
     3261720.893    13858716.449     3259109.755    13858407.863
#Sta/Elev= 30
 2549.06   24.28 3046.45    24.6 3143.09   22.34 3373.54    25.1 3538.38   23.01
 3652.74    24.8 4029.42   24.18    4140   21.05 4275.02   11.33 4473.15   14.18
 4600.02    9.95  4671.5    10.4  4924.5     6.1  4929.5     1.1  4967.5   -14.5
  4986.5   -16.1  5005.5      -8  5045.5     2.8  5059.5     2.9  5075.5     5.6
 5189.65    7.11 5468.36   15.44 5574.59   15.62 5671.38   18.52 5995.46   18.43
 6318.69   23.24 6916.83   25.34 7164.72   23.81 7695.08   24.81 7836.96   26.36
#Mann= 4 ,-1 , 0
 2549.06    .068       0 4029.42    .118       0  4924.5     .04       0
  5075.5    .118       0
Bank Sta=4924.5,5075.5
XS Rating Curve= 0
Exp/Cntr=.3,.1

Type RM Length L Ch R = 1 ,72487.93,629.33,1262.37,747.13
XS GIS Cut Line= 6
     3265049.127    13858919.611     3262816.047    13858842.073
     3262670.629    13858791.534     3262313.039    13858688.997
     3262149.224    13858640.476      3258892.65    13858082.206
#Sta/Elev= 30
 2424.82    25.3 3291.48   24.05 3551.34      26 3656.68   24.11 3886.89   24.98
 3955.61   22.29    4046   24.55 4589.12   23.97    4814    17.4    4836     6.2
    4882     2.9    4885      .6    4903    -1.9    4921     -18    4974   -11.8
    5027      .6    5030     5.8    5122       5    5323     9.2 5444.94    5.07
 5699.34    5.64 5798.99    7.59 5925.37   17.15 6614.83   23.35 7649.71   25.19
 7891.39    23.8 7908.43   21.85 7997.91   25.48 8390.05   24.12 8660.12   25.82
#Mann= 5 ,-1 , 0
 2424.82    .068       0 2923.64    .118       0    4046    .068       0
 4794.24     .04       0    5027    .118       0
Bank Sta=4814,5030
XS Rating Curve= 0
Exp/Cntr=.3,.1

Type RM Length L Ch R = 1 ,71225.56,913.26,1098.97,893.9
XS GIS Cut Line= 6
     3265080.142    13858314.818     3262151.441     13858208.42
     3262137.481    13858120.114     3262113.518    13857984.211
     3262087.194    13857865.101     3258908.157    13857647.996
#Sta/Elev= 30
 1912.27   23.97 3419.68   22.87 3628.23   18.83  3914.3   18.83 4193.99    13.5
 4469.73    12.5 4618.39    6.82 4679.06    9.35    4881     4.5    4931     5.5
    4938       3    4955   -12.7    5001   -19.6    5017   -18.5    5047    -7.3
    5069     5.6    5119     5.4 5192.29   11.27 5344.14   18.14  5817.4   18.95
 6051.41   23.52 6669.12   23.88 6773.65   25.77 6890.21    23.9 7487.88   24.12
 7538.09    21.3 7597.69   23.96 8013.93    24.1 8057.89   26.12 8378.73   24.15
#Mann= 8 ,-1 , 0
 1912.27    .068       0 2429.59    .118       0    4931     .04       0
    5069    .118       0 5404.16    .068       0 5986.14    .118       0
 6180.13    .068       0 7538.09    .118       0
Bank Sta=4931,5069
XS Rating Curve= 0
Exp/Cntr=.3,.1

Type RM Length L Ch R = 1 ,70126.59,1068.93,1093.31,736.83
XS GIS Cut Line= 6
      3268418.01    13857753.948     3262933.761    13857407.683
     3262860.642    13857312.011     3262779.008    13857214.723
     3262703.524    13857130.295     3258846.127    13856826.098
#Sta/Elev= 30
 -674.66    22.8 -424.69   21.63 -385.79   26.19 -334.51   24.58 -274.39   16.84
 -177.71   20.99   371.9   20.58  436.64   24.49  678.78   21.43 2330.74    23.1
 2423.77   25.88 2450.34   22.93 3812.51   23.76 4240.23   17.44 4434.16   18.43
 4572.92    7.78 4691.67    3.36  4911.5     7.1  4936.5     6.1  4966.5      -4
  4984.5   -14.4  5002.5     -18  5063.5     4.4 5163.87   15.45 5347.07   18.07
 6675.65    22.8 7930.42   22.71 7989.86    19.1 8022.42   22.37 9050.55   23.08
#Mann= 7 ,-1 , 0
 -674.66    .068       0 3215.42    .118       0  4911.5     .04       0
  5063.5    .118       0 6230.24    .068       0 7202.76    .118       0
 8369.78    .068       0
#Block Obstruct= 2 ,-1
 -327.55 -176.15   21.01 7843.52 9050.55   22.24
Bank Sta=4911.5,5063.5
XS Rating Curve= 0
Exp/Cntr=.3,.1

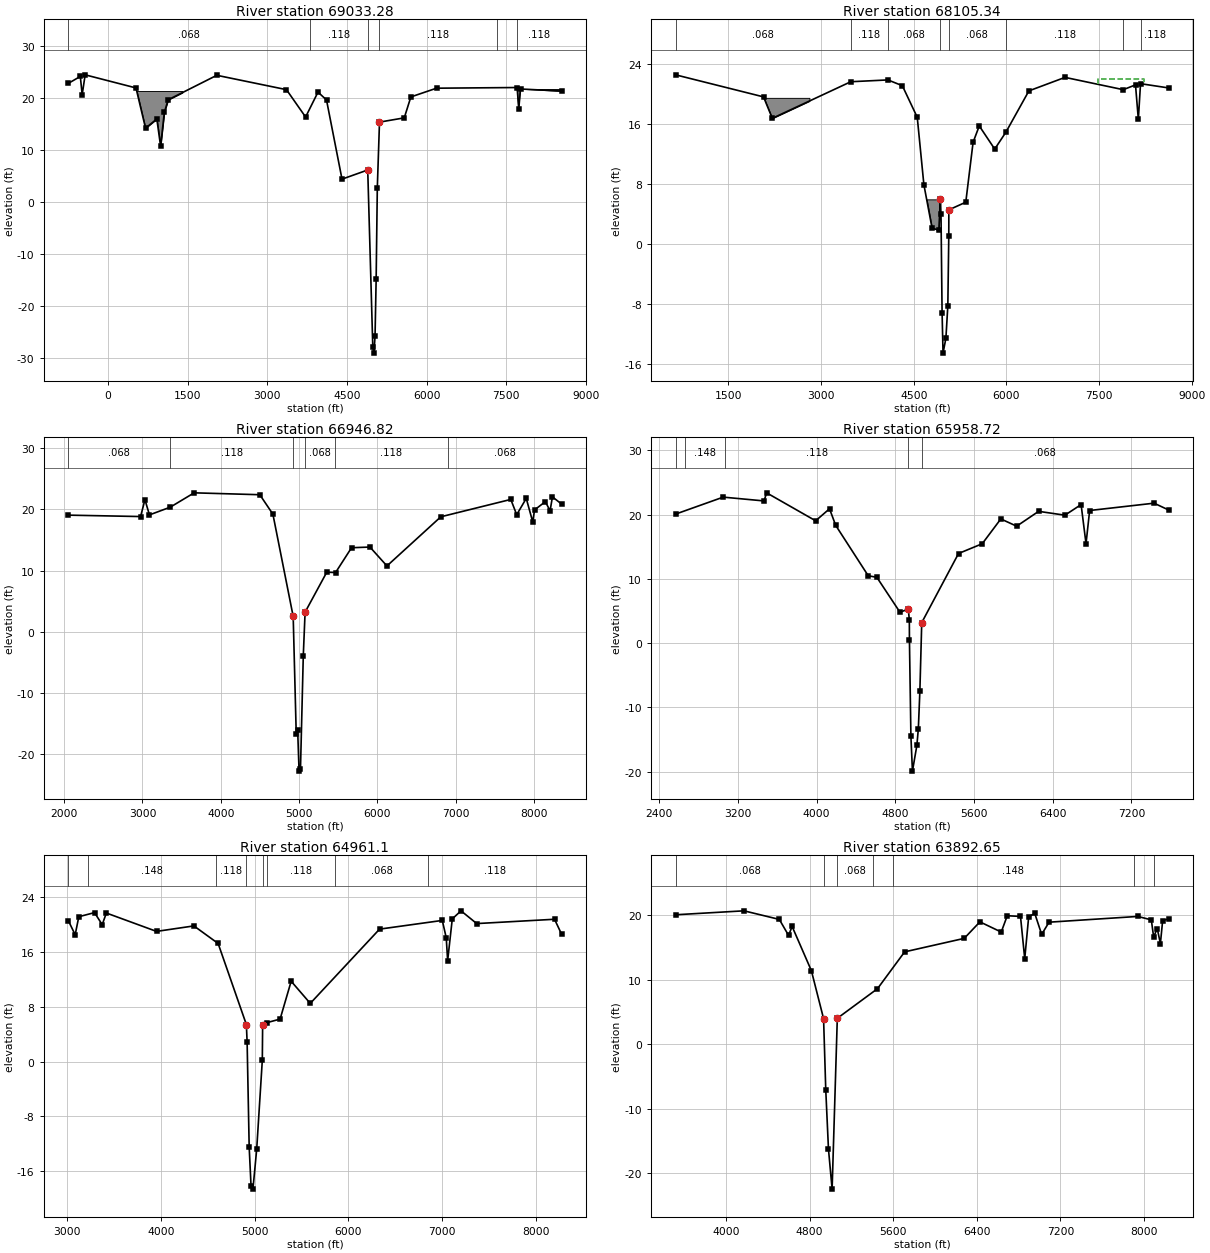
Type RM Length L Ch R = 1 ,69033.28,819.25,927.93,370.28
XS GIS Cut Line= 6
     3268509.799    13856889.012     3262984.774    13856401.128
      3262895.61     13856400.23      3262674.11     13856400.23
     3262536.912    13856407.396     3259249.322    13856236.814
#Sta/Elev= 30
  -748.4   22.85 -522.55   24.18 -487.77   20.67 -431.54   24.49  525.75   21.97
  705.34   14.24  918.19   16.01  988.97   10.78 1059.16   17.25 1131.07   19.69
 2047.54    24.4 3358.79   21.64 3719.32   16.38 3952.85   21.17 4112.97   19.66
 4404.79    4.44 4889.25     6.2 4984.75   -27.9 5005.75     -29 5026.75   -25.8
 5047.75   -14.8 5069.75     2.8 5110.75    15.4 5577.27   16.22 5701.13   20.24
 6184.14   21.92  7702.4   22.05  7732.9   17.93 7766.16   21.77 8538.19   21.37
#Mann= 6 ,-1 , 0
  -748.4    .068       0 3802.03    .118       0 4889.25     .04       0
 5110.75    .118       0 7330.93    .068       0  7702.4    .118       0
#XS Ineff= 2 , 0
         3985.61   19.41
Permanent Ineff=
       F       F
#Block Obstruct= 2 ,-1
  517.48  1398.6   21.38 7622.38 8538.19   21.73
Bank Sta=4889.25,5110.75
XS Rating Curve= 0
Exp/Cntr=.3,.1

Type RM Length L Ch R = 1 ,68105.34,959.5,1158.52,930.78
XS GIS Cut Line= 6
     3267317.787    13855182.868      3264651.42    13855075.641
     3263374.317    13855864.634     3263278.732    13855937.287
     3263088.941    13856093.836     3259652.517    13855818.111
#Sta/Elev= 30
  645.14    22.6 2068.68   19.66 2210.66    16.8 3481.46   21.68 4082.64   21.92
 4315.72   21.15 4557.06   16.94  4664.4    7.96 4796.98    2.16  4906.5     1.9
  4931.5       6  4941.5       4    4959    -9.1  4974.5   -14.5    5021   -12.5
    5052    -8.2  5067.5     1.1  5068.5     4.6 5342.58    5.62  5461.1   13.61
 5560.88   15.79 5811.02    12.7 5993.92   14.98  6364.2   20.46 6948.86   22.26
 7892.06   20.62 8089.86   21.26  8135.8   16.66 8171.28   21.42  8628.4   20.85
#Mann= 8 ,-1 , 0
  645.14    .068       0 3481.46    .118       0 4082.64    .068       0
  4931.5     .03       0  5068.5    .068       0 5993.92    .118       0
 7892.06    .068       0 8171.28    .118       0
#XS Ineff= 1 ,-1
 7481.66 8227.38   22.02
Permanent Ineff=
       F
#Block Obstruct= 2 ,-1
  645.14 2811.74   19.53 4699.15  4931.5       6
Bank Sta=4931.5,5068.5
XS Rating Curve= 0
Exp/Cntr=.3,.1

Type RM Length L Ch R = 1 ,66946.82,351.58,988.11,602.94
XS GIS Cut Line= 6
     3265782.881    13854740.107     3264439.959    13854806.651
     3263062.899    13854817.795     3262970.219    13854936.159
     3262786.858    13855161.545     3259652.517    13855151.289
#Sta/Elev= 30
 2053.02   19.07 2975.76   18.84 3031.26    21.6 3088.64   19.11 3353.78   20.37
 3659.62   22.72  4497.8   22.41 4664.94   19.23    4924     2.5    4963   -16.8
    4981     -16    4999   -22.8    5017   -22.5    5053    -3.9    5076     3.2
 5352.74    9.74  5465.2    9.68 5668.94   13.74 5903.94   13.85 6121.12   10.76
 6808.96    18.8  7702.4   21.64 7777.82   19.14 7899.72   21.81 7982.36   17.96
 8005.52   19.92 8143.32   21.28 8203.96   19.78 8233.96   22.06 8349.98   20.89
#Mann= 6 ,-1 , 0
 2053.02    .068       0 3353.78    .118       0    4924     .04       0
    5076    .068       0 5453.38    .118       0 6901.68    .068       0
#XS Ineff= 2 ,-1
  7853.3 8161.37   20.68 5799.51 6449.88    13.6
Permanent Ineff=
       F       F
Bank Sta=4924,5076
XS Rating Curve= 0
Exp/Cntr=.3,.1

Type RM Length L Ch R = 1 ,65958.72,541.76,997.62,849.19
XS GIS Cut Line= 6
     3264486.777    13854487.597     3262273.284    13854484.466
     3262132.055    13854539.895     3262002.236    13854582.076
     3261870.089    13854624.034     3259497.442    13854608.526
#Sta/Elev= 30
 2566.16   20.08 3050.27   22.72  3465.3   22.13 3491.57   23.39 3989.98   19.04
 4130.93   20.91 4193.66   18.33 4524.41   10.49 4611.97   10.25 4846.82    4.82
 4931.75     5.3 4942.25     3.6 4943.25      .5 4958.25   -14.5 4973.75   -19.9
 5018.75   -15.9 5033.75   -13.3 5049.25    -7.5 5068.25     3.2 5442.07   13.95
 5683.15   15.47 5872.12   19.33 6033.09    18.2 6256.29   20.51  6523.6   19.91
 6688.08   21.56 6738.11   15.48  6774.9   20.64 7429.75   21.78 7579.22   20.71
#Mann= 5 ,-1 , 0
 2566.16    .118       0 2666.42    .148       0 3067.47    .118       0
 4931.75     .04       0 5068.25    .068       0
#XS Ineff= 1 ,-1
 6679.71 7442.54   21.46
Permanent Ineff=
       F
Bank Sta=4931.75,5068.25
XS Rating Curve= 0
Exp/Cntr=.3,.1

Type RM Length L Ch R = 1 ,64961.1 ,1107.82,1068.45,1058.91
XS GIS Cut Line= 6
     3264543.014    13853943.974     3262729.566    13853948.003
     3262652.057    13853913.022     3262493.557    13853842.453
     3262366.329    13853802.136     3259311.352    13853802.136
#Sta/Elev= 30
 3014.19   20.56 3087.27    18.5 3125.84   21.13 3293.77   21.73 3375.58   19.97
 3419.78   21.67 3954.87   18.99  4353.5   19.79 4611.89   17.23 4913.25     5.4
 4921.25     2.8 4943.25   -12.5 4963.25   -18.2 4983.25   -18.6 5023.25   -12.8
 5083.25      .2 5086.75     5.4 5137.25     5.7 5272.98     6.2 5391.02   11.72
 5594.78    8.49 6333.91   19.32 7002.87   20.59 7045.05   18.06 7060.05   14.72
 7109.57   20.82 7202.66   21.99 7370.05   20.13 8200.23   20.76 8274.62    18.6
#Mann= 8 ,-1 , 0
 3014.19    .118       0 3224.61    .148       0 4592.32    .118       0
 4913.25     .04       0 5086.75    .068       0 5137.25    .118       0
 5854.82    .068       0  6854.3    .118       0
#XS Ineff= 1 ,-1
 7001.83 8168.11   20.54
Permanent Ineff=
       F
Bank Sta=4913.25,5086.75
XS Rating Curve= 0
Exp/Cntr=.3,.1

Type RM Length L Ch R = 1 ,63892.65,622.94,1262.78,1130.77
XS GIS Cut Line= 6
     3264074.374    13852837.983     3262781.649    13852843.836
      3262658.35     13852829.22      3262527.47     13852817.05
     3262411.858    13852755.295     3259373.382    13852747.626
#Sta/Elev= 30
 3518.58   20.04 4172.98   20.65 4511.05   19.32 4599.43   16.84 4633.39   18.23
 4817.69   11.37 4934.28    3.94 4955.36   -7.15  4981.1  -16.27 5016.02  -22.49
 5065.72    3.99 5450.08    8.58 5709.75   14.29  6279.8   16.38 6429.79   18.94
 6633.78   17.36 6691.49   19.89 6818.09   19.78 6858.59   13.22 6896.33   19.73
 6954.45   20.25 7020.59      17 7091.33   18.89 7940.28   19.78 8069.54   19.25
 8091.66   16.61 8126.33    17.9 8156.33   15.57 8178.03   19.15 8236.48    19.4
#Mann= 7 ,-1 , 0
 3518.58    .068       0 4934.28     .03       0 5065.72    .068       0
 5405.74    .118       0 5594.46    .148       0 7906.23    .068       0
 8094.95    .148       0
#XS Ineff= 1 ,-1
 6769.23 8237.76   19.38
Permanent Ineff=
       F
Bank Sta=4934.28,5065.72
XS Rating Curve= 0
Exp/Cntr=.3,.1

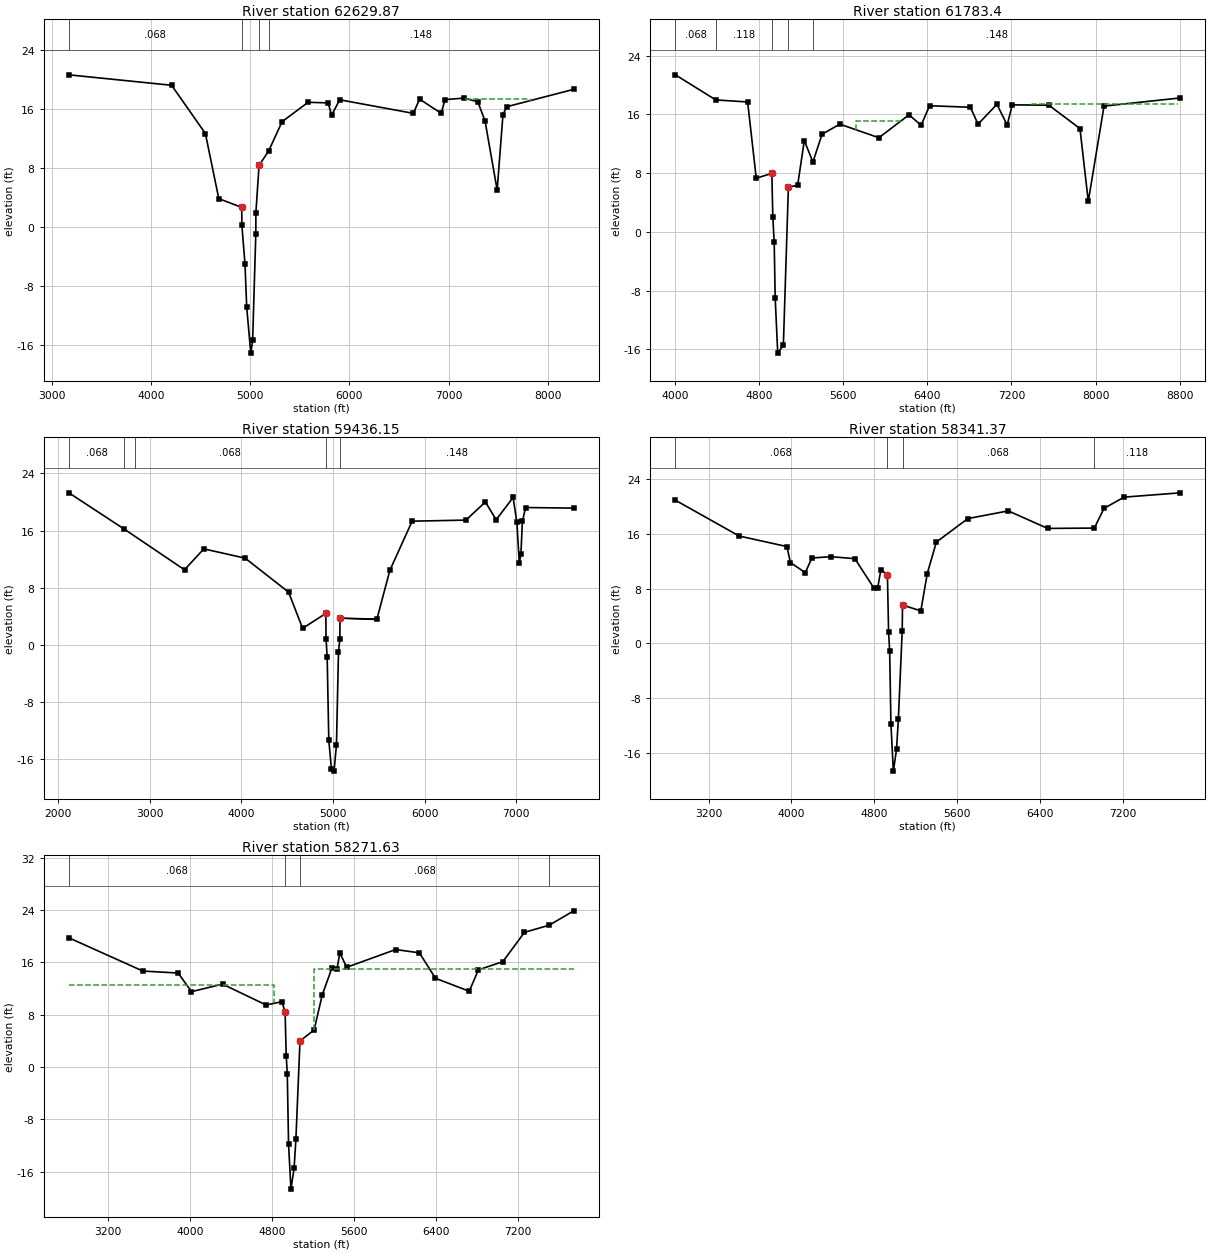
Type RM Length L Ch R = 1 ,62629.87,756.68,846.47,315.04
XS GIS Cut Line= 6
     3264476.253     13852780.22     3262949.441    13852149.156
      3262919.39     13852062.62       3262958.9     13851892.24
     3262661.063    13851693.521     3259853.816     13851461.06
#Sta/Elev= 30
 3168.88   20.67 4205.32   19.25 4546.04    12.7 4681.16    3.86 4912.55    2.67
 4914.17     .24 4945.33   -4.97 4962.95  -10.89 5004.03  -17.12 5022.71  -15.38
 5054.85    -.91 5055.67    1.97 5087.45    8.36  5184.7   10.34 5319.82   14.31
 5582.86   16.94 5785.08   16.86 5818.98   15.17 5901.08   17.28 6643.92   15.44
 6707.36   17.37 6924.88   15.45 6964.46   17.31 7157.12   17.51 7295.04      17
 7367.88   14.39 7490.02    5.02 7548.66   15.28 7587.02   16.34 8262.38    18.7
#Mann= 4 ,-1 , 0
 3168.88    .068       0 4912.55     .03       0 5087.45    .068       0
  5184.7    .148       0
#XS Ineff= 1 ,-1
 7167.83 7818.18   17.42
Permanent Ineff=
       F
Bank Sta=4912.55,5087.45
XS Rating Curve= 0
Exp/Cntr=.3,.1

Type RM Length L Ch R = 1 ,61783.4 ,519.02,2347.25,814.3
XS GIS Cut Line= 6
     3264295.949    13852320.262     3264066.782    13851830.678
        3263724.     13851672.68     3263474.264    13851565.405
     3261720.174    13851275.473     3259887.288      13851293.7
#Sta/Elev= 30
 4003.86    21.4 4387.92   17.98 4691.04    17.7 4772.94    7.31 4921.28    7.97
 4930.44    2.09 4943.61   -1.44 4953.05   -8.99 4977.31  -16.52 5030.85  -15.42
 5078.72    6.11 5166.48    6.34 5229.84   12.44    5312    9.52 5399.02   13.31
 5568.06   14.68  5939.4   12.83 6225.38   15.95 6341.06   14.53  6421.3   17.19
 6809.92   16.98 6882.02   14.68 7061.84   17.38 7159.24   14.56 7208.04   17.31
 7555.92   17.26 7851.56   14.08 7930.68    4.16 8080.46   17.14 8804.56   18.25
#Mann= 5 ,-1 , 0
 4003.86    .068       0 4387.92    .118       0 4921.28     .03       0
 5078.72    .068       0    5312    .148       0
#XS Ineff= 2 ,-1
 7397.44 8784.38   17.42 5723.72 6182.15   15.09
Permanent Ineff=
       F       F
Bank Sta=4921.28,5078.72
XS Rating Curve= 0
Exp/Cntr=.3,.1

Type RM Length L Ch R = 1 ,59436.15,51.3,1094.78,1460.53
XS GIS Cut Line= 6
     3264405.324     13852294.22      3264228.24    13851460.887
     3263769.024     13850698.08      3262706.98     13850713.79
     3262448.316    13850625.086     3260155.063    13849820.936
#Sta/Elev= 30
 2119.27   21.29 2725.16   16.19 3380.59   10.51 3591.46   13.44 4042.36   12.14
 4515.99    7.38 4669.33    2.31 4922.93     4.4 4924.87     .88 4937.32   -1.74
 4955.13   -13.4 4984.27  -17.43 5012.38  -17.69 5038.61     -14  5060.8   -1.02
 5076.03     .86 5077.07    3.76 5479.36    3.57 5620.85   10.42 5864.41   17.32
 6451.42   17.47 6663.68   20.01 6781.22   17.52  6966.5   20.64 7007.04   17.16
 7033.96   11.41 7051.44   12.76 7067.34    17.3 7102.74   19.23 7627.36   19.15
#Mann= 5 ,-1 , 0
 2119.27    .068       0 2725.16    .118       0 2835.32    .068       0
 4922.93     .03       0 5077.07    .148       0
#XS Ineff= 1 ,-1
 6923.08 7167.83   18.66
Permanent Ineff=
       F
#Block Obstruct= 1 ,-1
 5077.19 5488.29    3.76
Bank Sta=4922.93,5077.07
XS Rating Curve= 0
Exp/Cntr=.3,.1

Type RM Length L Ch R = 1 ,58341.37,157.1,69.74,205.41
XS GIS Cut Line= 6
      3264449.68    13852264.312     3264290.907     13851508.05
     3263682.972    13850501.092      3263627.34     13850421.22
     3263448.427    13850256.892     3261789.716    13848273.979
#Sta/Elev= 30
 2879.56   20.93 3495.32    15.7  3956.8   14.16 3990.18   11.83 4134.37   10.34
 4197.47   12.49 4381.15   12.68 4612.95   12.39 4793.43    8.17  4833.6    8.15
 4863.62   10.75 4927.11   10.06 4938.37    1.74 4948.78   -1.09 4961.07  -11.72
 4984.39  -18.65 5015.28  -15.46 5032.79  -11.05 5070.14    1.87 5072.89    5.62
  5249.7    4.76 5311.75    10.2 5399.77   14.82 5704.34   18.25 6094.53   19.37
 6474.24   16.81 6925.46   16.86 7018.85   19.74 7212.33   21.38 7754.14   22.01
#Mann= 4 ,-1 , 0
 2879.56    .068       0 4927.11     .03       0 5072.89    .068       0
 6925.46    .118       0
#Block Obstruct= 2 , 0
                         6058.68           18.82
Bank Sta=4927.11,5072.89
XS Rating Curve= 0
Exp/Cntr=.5,.3

Type RM Length L Ch R = 1 ,58271.63,195.55,181.95,268.89
XS GIS Cut Line= 6
     3264526.295    13852248.559      3264418.19    13851574.979
     3263970.325    13850762.187     3263645.637    13850342.604
     3263531.107      13850175.6     3261889.567     13848172.45
#Sta/Elev= 30
 2814.64   19.77 3537.56   14.69 3882.58   14.39  4012.5   11.54 4316.16   12.69
 4740.92    9.51 4894.94      10 4927.11     8.5 4938.37    1.74 4948.78   -1.09
 4961.07  -11.72 4984.39  -18.65 5015.28  -15.46 5032.79  -11.05 5072.89       4
 5211.04    5.69  5290.7   11.07 5384.76   15.15    5435   15.08 5462.52   17.46
 5529.34   15.27 6007.82   17.98  6239.4   17.48 6396.84   13.59 6726.74    11.6
 6816.38   14.87 7055.12   16.13 7266.68   20.61 7509.42   21.71 7747.74    23.9
#Mann= 4 ,-1 , 0
 2814.64    .068       0 4927.11     .03       0 5072.89    .068       0
 7509.42    .118       0
#XS Ineff= 2 , 0
       0    4817    12.6    5210       0      15
Permanent Ineff=
       F       F
Bank Sta=4927.11,5072.89
XS Rating Curve= 0
Exp/Cntr=.5,.3