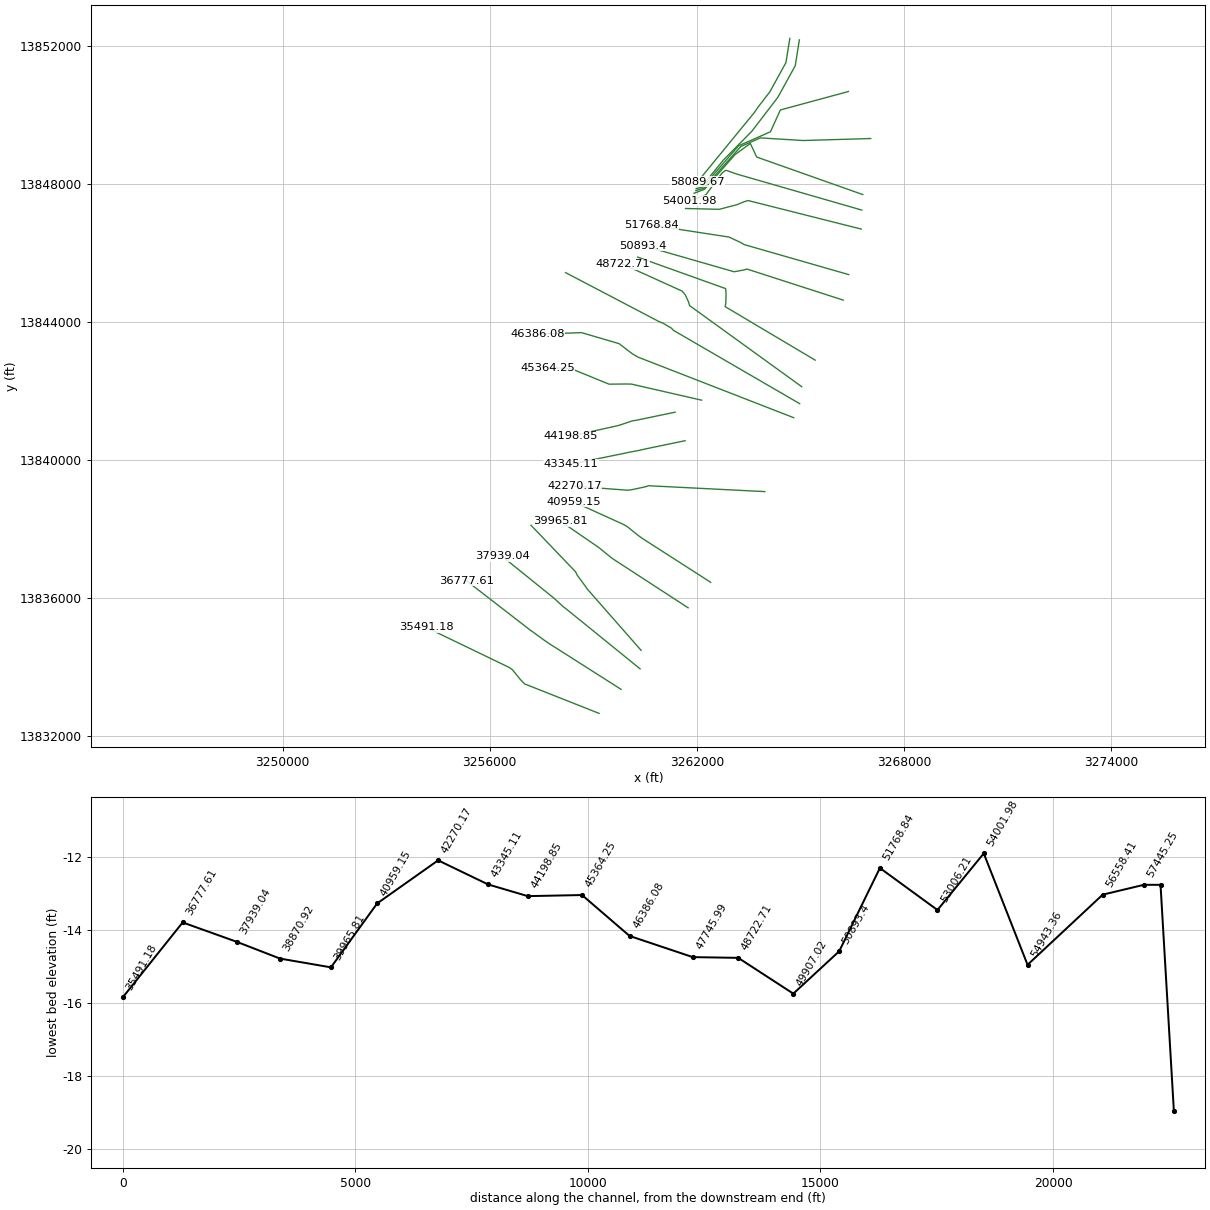
HEC-RAS study Q100-00-00.prj: Q100-00-00

--- Q100-00-00.g01 (geometry) --- (continued)

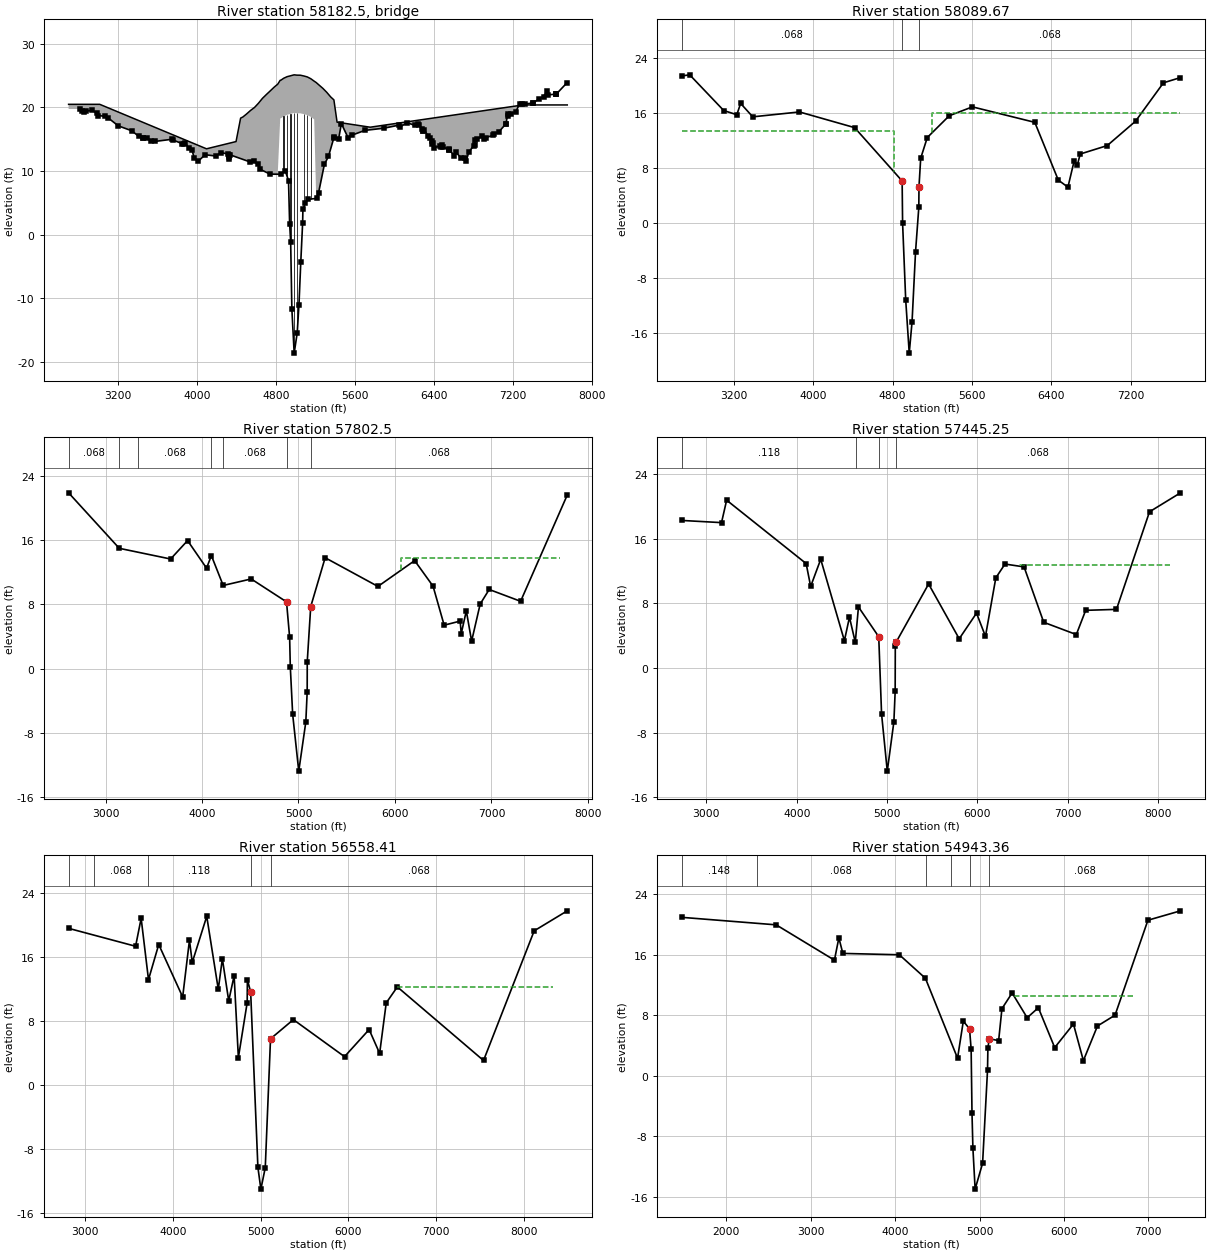
Type RM Length L Ch R = 3 ,58182.5 ,,,
BEGIN DESCRIPTION:
Highway 146
END DESCRIPTION:
Bridge Culvert--1,0,-1,-1, 0
Deck Dist Width WeirC Skew NumUp NumDn MinLoCord MaxHiCord MaxSubmerge Is_Ogee
46.1,90,2.6,0, 38, 38, , , .95, 0, 0,0,,
    2700  3015.3  4096.5 4395.71 4441.94 4465.01 4499.18 4542.11 4582.97 4622.05
 4663.07 4704.73 4743.81 4780.95 4817.87 4843.14  4849.2 4878.04 4912.78 4947.72
 4983.59 5012.54  5047.4 5082.46  5117.3 5152.27  5152.5 5187.19 5207.34  5238.7
 5275.17 5314.23 5354.32 5386.68 5418.92  5754.2  7301.8    7750
    20.5    20.5    13.5   14.64   18.33   18.51   18.94   19.53   20.01   20.66
   21.44   22.07   22.64   23.19   23.67   24.29   24.29    24.6   24.85   24.99
   25.14   25.09   25.08   24.96   24.81   24.53   24.53   24.14   23.93    23.5
   23.01   22.39   21.66    21.2   17.69    16.9    20.4    20.4
       0       0       0       0       0       0       0       0       0       0
       0       0       0       0       0   18.29   18.29    18.6   18.85   18.99
   19.14   19.09   19.08   18.96   18.81   18.53   18.53   18.14       0       0
       0       0       0       0       0       0       0       0
    2700  3015.3  4096.5 4395.71 4441.94 4465.01 4499.18 4542.11 4582.97 4622.05
 4663.07 4704.73 4743.81 4780.95 4817.87 4843.14  4849.2 4878.04 4912.78 4947.72
 4983.59 5012.54  5047.4 5082.46  5117.3 5152.27  5152.5 5187.19 5207.34  5238.7
 5275.17 5314.23 5354.32 5386.68 5418.92  5754.2  7301.8    7750
    20.5    20.5    13.5   14.64   18.33   18.51   18.94   19.53   20.01   20.66
   21.44   22.07   22.64   23.19   23.67   24.29   24.29    24.6   24.85   24.99
   25.14   25.09   25.08   24.96   24.81   24.53   24.53   24.14   23.93    23.5
   23.01   22.39   21.66    21.2   17.69    16.9    20.4    20.4
       0       0       0       0       0       0       0       0       0       0
       0       0       0       0       0   18.29   18.29    18.6   18.85   18.99
   19.14   19.09   19.08   18.96   18.81   18.53   18.53   18.14       0       0
       0       0       0       0       0       0       0       0
Pier Skew, UpSta & Num, DnSta & Num=  ,4877.2, 2 ,4877.2, 2 , 0 , 0 , 0 ,,
     2.5     2.5
       0      22
     2.5     2.5
       0      22
Pier Skew, UpSta & Num, DnSta & Num=  ,4912.2, 2 ,4912.2, 2 , 0 , 0 , 0 ,,
     2.5     2.5
       0      22
     2.5     2.5
       0      22
Pier Skew, UpSta & Num, DnSta & Num=  ,4947.2, 2 ,4947.2, 2 , 0 , 0 , 0 ,,
     2.5     2.5
       0      22
     2.5     2.5
       0      22
Pier Skew, UpSta & Num, DnSta & Num=  ,4982.2, 2 ,4982.2, 2 , 0 , 0 , 0 ,,
     2.5     2.5
       0      22
     2.5     2.5
       0      22
Pier Skew, UpSta & Num, DnSta & Num=  ,5017.2, 2 ,5017.2, 2 , 0 , 0 , 0 ,,
     1.4     1.4
       0      23
     1.4     1.4
       0      23
Pier Skew, UpSta & Num, DnSta & Num=  ,5082.2, 2 ,5082.2, 2 , 0 , 0 , 0 ,,
     1.4     1.4
       0      23
     1.4     1.4
       0      23
Pier Skew, UpSta & Num, DnSta & Num=  ,5117.2, 2 ,5117.2, 2 , 0 , 0 , 0 ,,
     2.5     2.5
       0      22
     2.5     2.5
       0      22
Pier Skew, UpSta & Num, DnSta & Num=  ,5152.2, 2 ,5152.2, 2 , 0 , 0 , 0 ,,
     2.5     2.5
       0      22
     2.5     2.5
       0      22
BR Coef=-1 , 1 , 1 ,.9, 0 ,,,.8,0,1.2,0,
WSPro=,,,, 1 ,,,, 0 ,,,, 0 ,,,,-1 ,-1 ,-1 , 0 , 0 , 0 , 0 , 0
BR U #Sta/Elev= 123
 2814.64   19.77 2832.06   19.51 2858.92   19.34  2872.4   19.43 2941.26   19.54
  2982.7   19.12 3002.24   18.73 3064.76   18.62 3099.94   18.37 3203.28   17.11
 3339.12   16.34 3412.28   15.44 3453.28   15.26 3457.86   15.23 3496.84   15.23
 3537.56   14.69 3574.38   14.66 3746.78      15    3753   14.91 3851.72    14.3
 3869.98   14.31 3882.58   14.39  3917.1   13.59  3949.8   13.37 3970.36   12.08
  4012.5   11.54 4082.44   12.57  4190.8   12.36 4242.08   12.89 4316.16   12.69
 4323.06   12.16 4325.24   11.89 4329.42   12.53 4335.32   12.55 4534.74   11.45
  4573.9    11.6 4617.08   11.06 4640.64   10.27 4740.92    9.51    4848     9.5
 4894.94      10 4927.11     8.5 4938.37    1.74 4948.78   -1.09 4961.07  -11.72
 4984.39  -18.65 5015.28  -15.46 5032.79  -11.05 5051.41   -4.29 5070.14    1.87
 5072.89       4 5098.71       5    5121    5.55 5211.04    5.69 5231.92    6.61
  5290.7   11.07 5331.56   12.29 5384.76   15.15 5392.36   15.33    5435   15.08
 5462.52   17.46 5529.34   15.27 5568.18   15.64 5701.24    16.4 5892.48   16.74
 6048.32   17.23 6059.86   16.99 6130.64   17.59 6205.18   17.19  6239.4   17.48
 6244.24   17.21 6281.16    16.6 6285.98   16.31 6291.52   16.28  6301.5   16.53
 6340.28   15.48 6359.26   15.22 6377.46   14.75  6379.4    14.3 6386.08   14.42
 6396.84   13.59 6464.24   14.01 6475.32   13.84 6476.98   14.14 6495.72   13.76
  6548.6   13.39 6549.94    13.4  6553.6   13.35 6606.82   12.41 6624.54   12.97
    6673   12.04 6714.56   11.99 6726.74    11.6 6752.56   12.97 6800.88   13.96
 6810.88   14.04 6816.38   14.87  6839.7   14.97 6882.54    15.5 6909.28      15
 6929.08   15.27 7000.74   15.64 7009.16   15.87 7055.12   16.13 7125.46   17.37
 7128.26   17.36 7146.76   18.95  7150.3   18.59 7185.14   18.99 7230.54   19.34
 7266.68   20.61 7295.56   20.55 7325.58   20.56 7402.46    20.7 7402.86    20.7
 7467.86   21.38 7509.42   21.71  7543.4    22.6 7559.52   21.99 7632.82    22.1
 7637.02   22.12 7639.04   22.11 7747.74    23.9
BR U #Mann= 4
 2814.64    .068 4927.11     .03 5072.89    .068 7509.42    .118
BR D #Sta/Elev= 114
 2676.12   21.36    2677   21.36 2755.62   21.52 2784.48   20.33  2827.6   20.49
 2847.98   20.33 2909.68   19.54 3003.96   18.65 3017.64   18.39 3042.74   17.97
 3098.86   16.32  3118.7   16.91 3152.32   16.83  3181.2   15.96 3209.86   15.92
  3230.2   15.72 3240.24   16.12 3268.76   17.36 3273.58   17.31 3331.02   15.82
  3390.9   15.41 3433.26   16.28 3448.78    16.4 3485.78   16.17    3546   15.36
  3555.7   15.07 3578.62   15.52  3619.8   15.41    3800      14    4100      13
 4359.52   13.74 4381.15      14  4417.3   13.84 4450.01   13.39 4490.46   13.25
  4528.6   12.74 4567.22   11.95 4604.24   11.75 4641.07   10.17 4713.29    9.29
 4750.13    9.12 4786.83    8.52  4825.2     7.3 4845.63     6.6 4896.15    6.08
 4900.64    -.03    4932  -11.21  4967.6  -18.96    4996  -14.41  5031.1   -4.22
  5050.7    -.06 5064.02    2.23 5065.85    5.23 5083.05    9.38 5149.46    12.4
 5170.99   12.73 5206.43   13.51 5279.71   14.09 5318.17   14.62 5356.04   15.27
 5370.99   15.57 5407.95   15.59 5447.92   16.26 5535.16   16.32 5603.92   16.86
  5634.2   16.55 5803.24    15.4 5834.36   15.48  5874.1   15.72  6097.2   15.57
 6135.14   15.15 6181.72   14.74 6232.72   14.61  6276.7   13.51 6302.16   12.22
 6331.18   11.35 6414.56    8.66 6428.92    7.84 6469.54    6.21 6490.82     5.7
 6514.26    5.49  6566.5    5.18    6614    8.18 6625.14    8.62 6628.42    8.94
 6640.82    8.36    6661    8.37  6690.3      10 6721.06   10.14 6794.14   10.02
 6833.68   10.77 6900.12   10.77 6911.38   10.85 6918.62   10.82 6962.78   11.23
    7003   11.86 7011.32   12.16 7017.86   12.24 7028.66    12.1  7118.8   13.08
  7158.6    14.1 7204.04    14.2 7247.58   14.77 7286.86   15.76 7452.86   18.21
 7483.76   19.38 7529.08   20.36  7612.2   20.69 7659.08   21.16 7660.36   21.19
 7664.86   21.07 7683.36   20.81  7688.5   20.79 7700.72   21.12
BR D #Mann= 3
 2676.12    .068 4896.15     .03 5065.85    .068
BC Design=,, 0 ,, 0 ,,,,,,
BC HTab HWMax=23.9

Type RM Length L Ch R = 1 ,58089.67,318.34,287.17,278.96
XS GIS Cut Line= 6
     3264696.122    13852221.303     3264583.275    13851518.178
     3264114.525    13850667.484      3263784.69     13850241.25
      3263669.08     13850072.67     3262022.511    13848063.317
#Sta/Elev= 30
 2676.12   21.36 2755.62   21.52 3098.86   16.32  3230.2   15.72 3268.76   17.36
  3390.9   15.41 3861.54   16.12  4417.3   13.84 4896.15    6.08 4900.64    -.03
    4932  -11.21  4967.6  -18.96    4996  -14.41  5031.1   -4.22 5064.02    2.23
 5065.85    5.23 5083.05    9.38 5149.46    12.4 5370.99   15.57 5603.92   16.86
 6232.72   14.61 6469.54    6.21  6566.5    5.18 6628.42    8.94    6661    8.37
  6690.3      10 6962.78   11.23 7247.58   14.77 7529.08   20.36 7700.72   21.12
#Mann= 3 ,-1 , 0
 2676.12    .068       0 4896.15     .03       0 5065.85    .068       0
#XS Ineff= 2 , 0
       0    4819    13.3    5200       0      16
Permanent Ineff=
       F       F
Bank Sta=4896.15,5065.85
XS Rating Curve= 0
Exp/Cntr=.5,.3

Type RM Length L Ch R = 1 ,57802.5 ,530.27,357.25,71.59
XS GIS Cut Line= 6
     3264972.584    13852176.933     3264852.018    13851425.712
     3264349.269    13850513.316     3263592.704    13849525.514
     3262764.879    13848688.631     3262168.207    13847956.764
#Sta/Elev= 30
 2617.28   21.85 3142.42   14.95 3674.58   13.62 3850.56   15.91 4047.28   12.48
 4097.04   14.05 4219.54   10.33 4509.92   11.14    4876    8.29 4908.31    3.88
 4915.18     .23 4939.69   -5.69 5002.81  -12.76 5075.96   -6.65 5090.22   -2.88
 5090.85     .86 5126.85     7.7 5276.38   13.78  5823.6   10.21  6204.1   13.42
 6394.86   10.24 6509.86    5.39  6675.9     5.9  6686.7    4.33 6739.54    7.17
 6794.52    3.41  6883.3    8.02 6976.64    9.83 7302.18    8.36 7785.86   21.58
#Mann= 7 ,-1 , 0
 2617.28    .068       0 3142.42    .118       0 3340.88    .068       0
 4097.04    .118       0 4219.54    .068       0    4876     .03       0
 5126.85    .068       0
#XS Ineff= 1 ,-1
 6063.57  7706.6    13.7
Permanent Ineff=
       F
Bank Sta=4876,5126.85
XS Rating Curve= 0
Exp/Cntr=.3,.1

Type RM Length L Ch R = 1 ,57445.25,1108.68,886.84,76.91
XS GIS Cut Line= 6
     3266391.996    13850680.049     3264422.274     13850145.92
     3264133.907    13849513.701     3263212.032    13849107.451
     3262169.696    13847913.383     3261982.866    13847867.868
#Sta/Elev= 30
 2728.27   18.28 3167.77   18.01 3224.47   20.79 4104.71   12.94 4154.64   10.11
 4266.04   13.47 4528.14    3.39 4584.26     6.3 4648.67    3.19 4683.83    7.57
 4908.31    3.88 4939.69   -5.69 5002.81  -12.76 5075.96   -6.65 5090.22   -2.88
 5091.69    2.76 5101.85    3.23 5460.37   10.41 5799.16    3.63 5990.84     6.8
 6089.84    3.93 6204.45   11.17 6305.78   12.88 6517.15   12.53 6734.77    5.67
 7095.72    4.15 7199.18    7.15 7540.35    7.27 7905.89   19.35 8248.87    21.7
#Mann= 4 ,-1 , 0
 2728.27    .118       0 4660.48    .068       0 4908.31     .03       0
 5102.13    .068       0
#XS Ineff= 1 ,-1
 6468.84 8137.55    12.8
Permanent Ineff=
       F
Bank Sta=4908.31,5101.85
XS Rating Curve= 0
Exp/Cntr=.3,.1

Type RM Length L Ch R = 1 ,56558.41,1002.72,1615.06,51.77
XS GIS Cut Line= 6
     3267040.431     13849318.43     3265083.388    13849260.444
     3263842.241    13849336.618     3263274.532    13849086.618
     3262201.616    13847878.284     3261972.449    13847810.576
#Sta/Elev= 30
 2814.41   19.57 3577.03   17.33 3640.34   20.82  3723.9   13.16  3840.5   17.55
 4112.96   10.99 4190.29   18.08 4221.93   15.31    4387   21.07 4518.39   11.96
 4564.79   15.76 4637.16   10.51 4698.77   13.65 4747.16    3.41 4847.54    10.3
 4849.65   13.15 4886.93   11.62 4969.38   -10.3 5003.28  -13.03 5053.23  -10.35
 5113.07    5.76 5373.16    8.16 5955.58    3.53 6235.63    6.92 6355.31    3.94
 6430.28   10.25  6556.8   12.25 7538.02    3.05 8114.73   19.26 8491.27   21.76
#Mann= 5 ,-1 , 0
 2814.41    .118       0 3098.25    .068       0 3722.71    .118       0
 4886.93     .03       0 5113.07    .068       0
#XS Ineff= 1 ,-1
 6552.57 8323.96    12.2
Permanent Ineff=
       F
Bank Sta=4886.93,5113.07
XS Rating Curve= 0
Exp/Cntr=.3,.1

Type RM Length L Ch R = 1 ,54943.36,591.47,941.38,153.71
XS GIS Cut Line= 6
     3266808.485     13847694.81     3263735.203    13848782.056
     3263551.669     13849174.86     3263107.866    13848852.243
     3262222.449    13847847.034     3261920.366    13847732.451
#Sta/Elev= 30
 1473.88   20.92  2591.8   19.93 3281.52   15.27 3333.96   18.21  3381.1   16.16
  4050.5   15.98 4359.02   12.88 4739.74    2.33 4808.05    7.22 4881.79     6.2
 4900.71    3.53 4910.88   -4.88 4921.56   -9.52 4947.92  -14.95 5036.29  -11.54
 5094.71     .72 5099.29    3.71 5115.76     4.9 5226.46    4.65 5265.56    8.87
 5386.23   10.94 5564.39    7.67 5696.69    8.99 5890.61    3.73 6112.48    6.84
 6230.17    2.01 6396.83    6.58 6605.18    8.01 6994.59   20.54 7380.28   21.78
#Mann= 6 ,-1 , 0
 1473.88    .148       0 2359.84    .068       0 4368.01    .118       0
 4663.33    .068       0 4881.79     .03       0 5115.76    .068       0
#XS Ineff= 1 ,-1
 5415.65 6819.07   10.59
Permanent Ineff=
       F
#Block Obstruct= 2 , 0
         3334.96   17.42
Bank Sta=4881.79,5115.76
XS Rating Curve= 0
Exp/Cntr=.3,.1

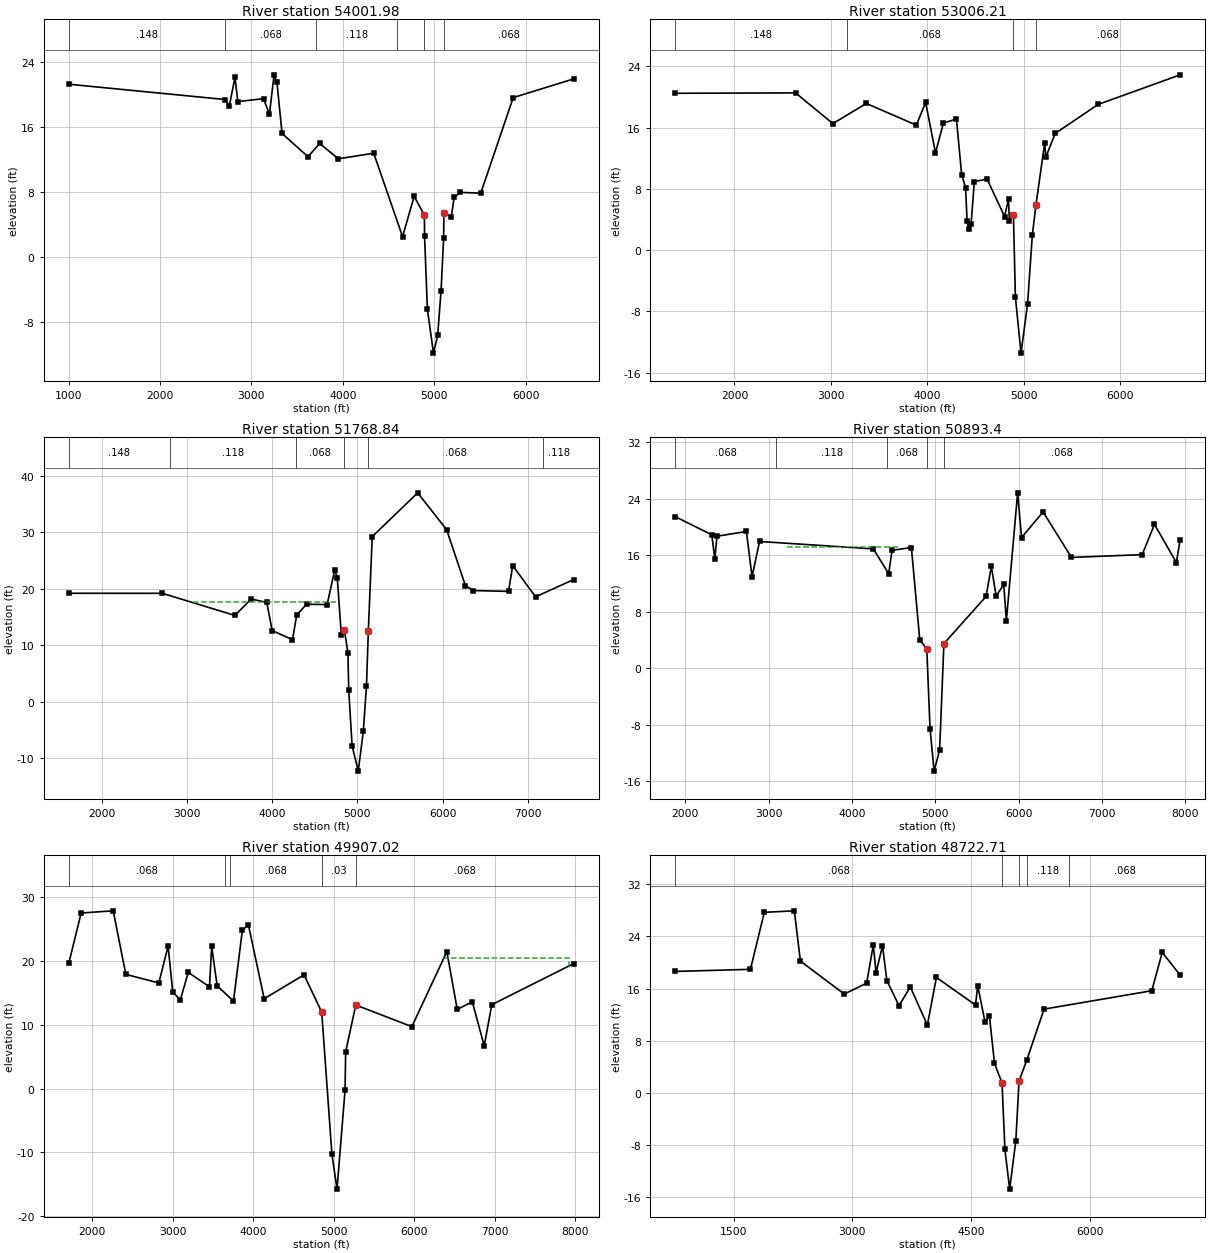
Type RM Length L Ch R = 1 ,54001.98,645.43,995.76,742.12
XS GIS Cut Line= 6
     3266779.492    13847245.415     3263155.339    13848289.171
      3262843.98     13848399.26     3262736.598    13848324.225
     3262262.367    13847687.042     3261796.817    13847516.442
#Sta/Elev= 30
 1004.06   21.27 2716.21   19.38 2758.55   18.56 2820.98   22.11  2852.2   19.13
 3133.18   19.49  3198.2   17.58 3248.88   22.43 3279.84   21.54  3336.1    15.2
 3619.68   12.33 3747.44   13.96 3952.01   12.07  4338.9   12.76 4654.73    2.47
 4781.37    7.43 4893.36    5.13 4895.36    2.52 4926.34   -6.51 4992.94   -11.9
 5038.71    -9.7  5075.6   -4.22 5104.07    2.26 5106.64    5.37  5187.8    4.92
 5219.41    7.32 5284.83    7.93 5510.13    7.83 5865.04   19.62 6527.12   21.93
#Mann= 6 ,-1 , 0
 1004.06    .148       0 2716.21    .068       0 3710.36    .118       0
 4594.05    .068       0 4893.36     .03       0 5106.64    .068       0
Bank Sta=4893.36,5106.64
XS Rating Curve= 0
Exp/Cntr=.3,.1

Type RM Length L Ch R = 1 ,53006.21,1289.74,1237.38,731.22
XS GIS Cut Line= 6
     3266764.995    13846694.543     3263488.761     13847520.85
      3263369.21     13847486.32      3263168.18     13847402.81
     3262651.285    13847267.117     3261675.289    13847290.748
#Sta/Elev= 30
 1387.55   20.48 2633.73   20.53 3019.81   16.52 3366.54   19.15 3884.84   16.32
 3981.15   19.29 4083.34    12.7 4165.44    16.6 4300.51   17.11 4354.36    9.87
 4395.34    8.14 4410.81    3.77 4426.28    2.79  4452.5    3.46  4486.1    8.95
 4618.28    9.27 4799.48    4.39 4840.05    6.67 4848.78    3.83 4891.16    4.55
 4911.52   -6.15 4969.68  -13.45 5037.42   -7.04 5087.12       2 5124.98    5.92
 5215.39   14.05 5227.04   12.15    5324   15.24 5768.31   19.02 6619.19   22.89
#Mann= 4 ,-1 , 0
 1387.55    .148       0 3166.31    .068       0 4891.16     .03       0
 5124.98    .068       0
#Block Obstruct= 2 , 0
         4185.82   16.49
Bank Sta=4891.16,5124.98
XS Rating Curve= 0
Exp/Cntr=.3,.1

Type RM Length L Ch R = 1 ,51768.84,687.47,875.43,941.63
XS GIS Cut Line= 6
      3266402.58    13845375.352     3263372.788    13846245.148
      3263267.54     13846308.19      3263065.74     13846401.58
     3262937.889    13846462.598     3260676.418    13846810.516
#Sta/Elev= 30
 1612.74   19.17 2709.36   19.16  3561.1   15.25 3753.21   18.15  3935.8   17.54
 3999.34   12.57 4237.87   10.95 4287.44   15.31 4403.23   17.23 4644.49   17.17
  4733.7   23.29  4763.3   21.95 4810.96   11.86 4847.76   12.63 4888.82    8.63
 4898.08    2.04 4937.99   -7.82 5009.84   -12.3 5069.43   -5.26 5106.65    2.73
 5128.25   12.53 5174.28   29.19 5707.86   36.94 6047.41   30.42 6268.44   20.52
 6361.62   19.65 6774.37    19.5 6823.49   24.06 7092.17   18.54  7539.7    21.6
#Mann= 6 ,-1 , 0
 1612.74    .148       0 2798.13    .118       0 4279.87    .068       0
 4847.76     .03       0 5128.25    .068       0 7184.08    .118       0
#XS Ineff= 1 ,-1
 3078.24 4743.28   17.58
Permanent Ineff=
       F
Bank Sta=4847.76,5128.25
XS Rating Curve= 0
Exp/Cntr=.3,.1

Type RM Length L Ch R = 1 ,50893.4 ,1427.44,986.38,595.15
XS GIS Cut Line= 6
     3266243.117    13844636.025     3263453.524    13845536.545
      3263374.28     13845512.48      3263172.86     13845473.44
     3263078.524     13845458.42     3260444.472    13846216.155
#Sta/Elev= 30
  1881.3   21.45 2318.54   18.88 2354.46   15.44    2380   18.68 2733.39   19.36
 2801.08   12.94 2890.97   17.94 4256.73   16.89 4440.01   13.38 4480.53   16.69
  4712.8   17.08 4812.86    4.03 4897.42     2.7 4936.34   -8.55 4985.33  -14.58
 5051.45  -11.58 5102.58    3.47 5607.71   10.15 5672.01   14.41 5729.17   10.21
 5820.42   11.85  5852.2    6.73 5986.96   24.83 6033.79    18.5 6292.96   22.12
 6632.78   15.68  7481.2   16.08 7628.84   20.36 7891.18   14.96 7937.03   18.22
#Mann= 5 ,-1 , 0
  1881.3    .068       0 3092.45    .118       0 4424.71    .068       0
 4897.42     .03       0 5102.58    .068       0
#XS Ineff= 2 ,-1
  3217.6 4567.24   17.11 5665.58 5899.04   12.15
Permanent Ineff=
       F       F
#Block Obstruct= 2 , 0
          2902.2   17.42
Bank Sta=4897.42,5102.58
XS Rating Curve= 0
Exp/Cntr=.3,.1

Type RM Length L Ch R = 1 ,49907.02,698.9,1184.31,515.72
XS GIS Cut Line= 6
     3265431.307    13842896.431     3262821.917    13844447.569
      3262842.07     13844548.44      3262847.15     13844845.61
     3262836.413    13844969.447     3260285.009    13845882.733
#Sta/Elev= 30
 1711.43    19.7  1863.7   27.47 2261.43   27.81 2418.48   17.87 2827.98   16.52
 2943.67   22.28 3000.99   15.15 3094.03   13.83 3194.38   18.17 3457.23   15.93
 3484.88   22.23 3552.74   16.06 3755.67    13.7  3865.6   24.75 3940.09   25.66
 4137.01   14.06 4631.85   17.79 4851.39   11.97 4978.33  -10.31 5041.66  -15.74
 5141.28    -.25 5148.61    5.72 5274.33   13.07 5971.24    9.69 6405.78   21.43
 6534.68   12.38 6721.77   13.58 6869.69    6.68 6963.81   13.12 7981.36   19.56
#Mann= 5 ,-1 , 0
 1711.43    .068       0 3655.11    .118       0 3717.81    .068       0
 4851.39     .03       0 5274.33    .068       0
#XS Ineff= 1 ,-1
  6364.3 7919.32   20.37
Permanent Ineff=
       F
#Block Obstruct= 2 , 0
          4391.2   17.55
Bank Sta=4851.39,5274.33
XS Rating Curve= 0
Exp/Cntr=.3,.1

Type RM Length L Ch R = 1 ,48722.71,886.14,976.72,1126.45
XS GIS Cut Line= 6
     3265039.898    13842128.111     3261792.657    13844476.562
      3261756.97     13844591.57       3261667.5     13844786.94
     3261575.208    13844896.964     3259850.111    13845679.781
#Sta/Elev= 30
  763.17   18.62 1712.06   18.94 1887.61   27.68 2266.86   27.91 2343.65    20.2
 2897.95   15.15 3180.41   16.82 3265.12   22.66 3300.24   18.41 3381.18   22.57
 3436.71    17.2 3590.29   13.37  3732.9   16.24 3948.56   10.38 4062.82    17.7
 4557.12   13.46 4584.44   16.46 4678.29   10.82 4732.53   11.84 4796.68    4.53
 4892.56    1.51 4928.44   -8.68 4988.85  -14.76    5066   -7.41 5107.44    1.82
 5204.43       5 5423.56   12.84 6785.29   15.66 6916.91   21.54 7143.95   18.05
#Mann= 5 ,-1 , 0
  763.17    .068       0 4892.56     .03       0 5107.44    .068       0
 5204.43    .118       0 5740.17    .068       0
#Block Obstruct= 2 , 0
         4112.47   17.11
Bank Sta=4892.56,5107.44
XS Rating Curve= 0
Exp/Cntr=.3,.1

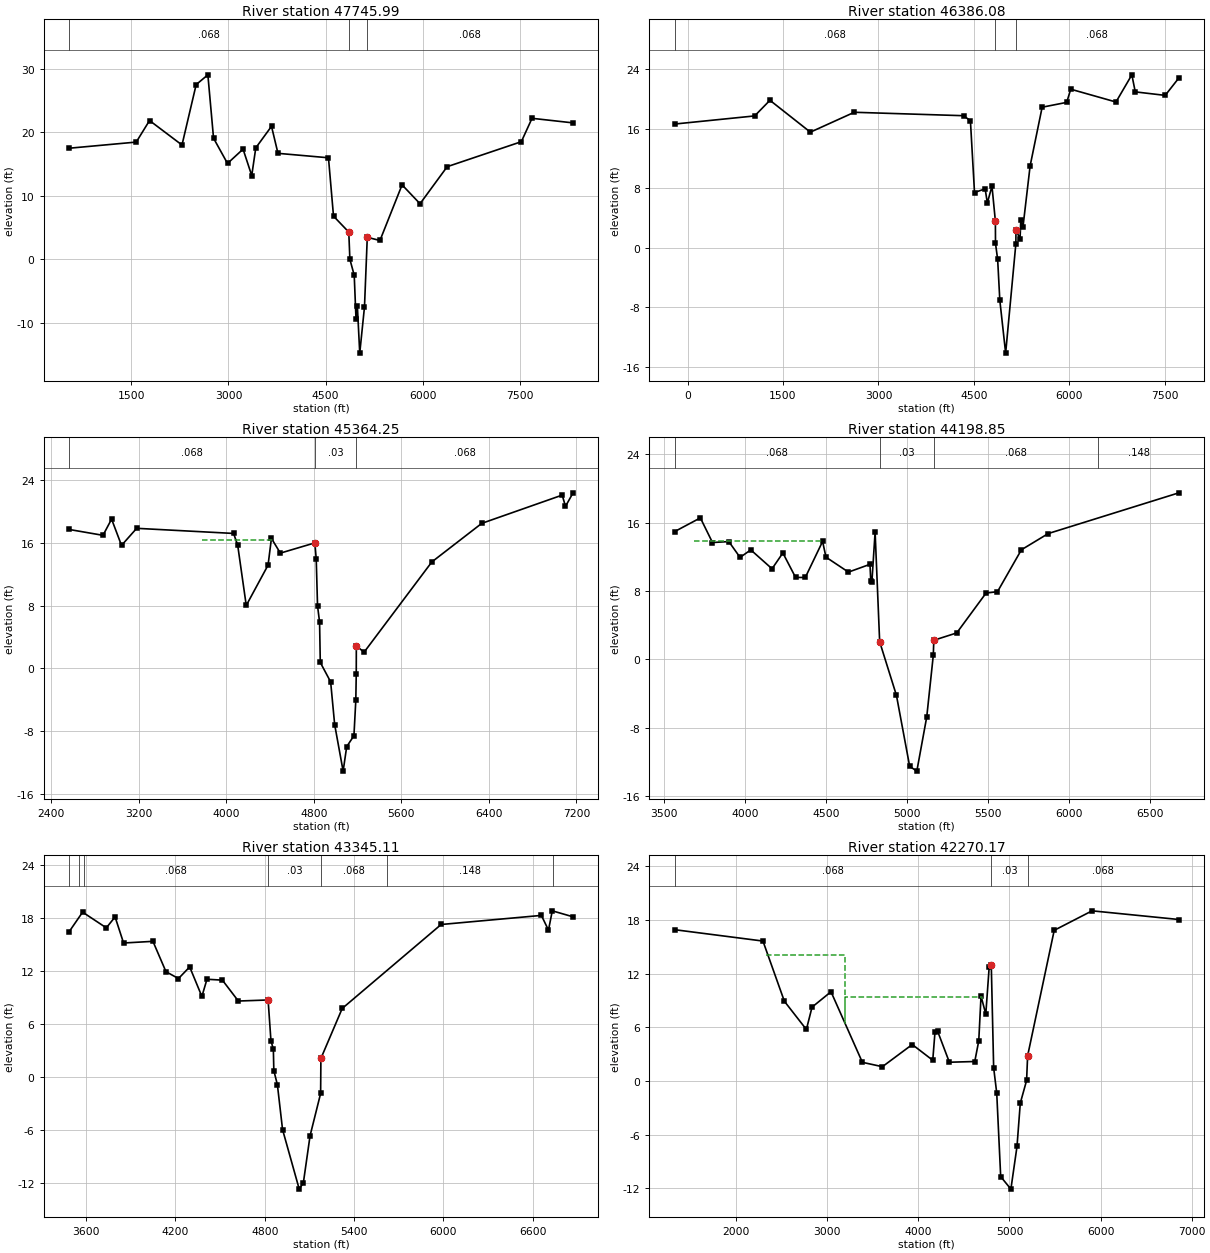
Type RM Length L Ch R = 1 ,47745.99,1146.59,1359.91,1245.32
XS GIS Cut Line= 6
     3264981.912    13841635.226     3261323.316    13843760.503
      3261264.45     13843824.77      3261018.33     13843969.26
     3260908.364     13844012.67     3258197.497    13845433.338
#Sta/Elev= 30
  536.78   17.49 1576.53   18.46 1781.82   21.85  2282.7      18 2501.39    27.5
 2682.18   29.04 2769.84   19.07 2985.29    15.1  3225.4   17.35 3359.28   13.19
 3421.73   17.55 3664.45   20.94  3764.2   16.69 4543.72   15.99 4621.51    6.81
  4857.3     4.3 4874.07     .03 4941.26   -2.49 4969.01   -9.42 4989.98    -7.4
  5026.4  -14.74 5099.62   -7.47  5142.7    3.48 5338.52    2.98  5679.8   11.73
 5957.03    8.76 6376.17   14.59  7520.5   18.52 7685.77    22.2 8319.22   21.48
#Mann= 3 ,-1 , 0
  536.78    .068       0  4857.3     .03       0  5142.7    .068       0
#Block Obstruct= 2 , 0
         4464.55   16.06
Bank Sta=4857.3,5142.7
XS Rating Curve= 0
Exp/Cntr=.3,.1

Type RM Length L Ch R = 1 ,46386.08,750.13,1021.82,1180.08
XS GIS Cut Line= 6
     3264807.952    13841229.321     3260297.274    13842984.461
      3260126.89     13843084.67     3259748.635    13843374.819
     3258661.389    13843693.745     3257385.687    13843650.255
#Sta/Elev= 30
 -202.21   16.61 1054.95    17.7 1294.92    19.8 1930.67   15.52 2620.76   18.19
 4338.01   17.73 4445.93   17.05 4510.17    7.41 4677.06    7.91 4711.86    6.01
  4784.7    8.27 4838.36    3.55 4839.99     .58 4873.89   -1.57 4907.71   -7.04
 4999.45  -14.16 5160.16     .54 5161.64    2.33 5225.98     1.2 5237.49    3.69
 5271.56    2.77 5383.99   10.98 5573.08   18.87 5959.24   19.52 6022.31   21.29
 6733.52   19.57 6982.97   23.22 7036.57   20.93 7507.02   20.46 7721.94    22.8
#Mann= 3 ,-1 , 0
 -202.21    .068       0 4838.36     .03       0 5161.64    .068       0
Bank Sta=4838.36,5161.64
XS Rating Curve= 0
Exp/Cntr=.3,.1

Type RM Length L Ch R = 1 ,45364.25,908.62,1165.4,1533.97
XS GIS Cut Line= 6
     3262140.576    13841736.702     3260104.566    13842203.211
      3259944.95     13842205.64     3259458.703    13842200.594
      3258356.96    13842649.989     3257675.619    13842678.982
#Sta/Elev= 30
 2563.16   17.67 2874.84   16.92 2953.42   18.98 3044.12   15.64 3182.61   17.81
 4068.31   17.16 4105.77   15.64 4183.69    8.01 4382.93   13.13 4413.71   16.53
 4495.47   14.66  4810.5   15.96 4822.99   13.93 4835.04    7.95 4853.68    5.89
 4860.09     .77 4954.72    -1.7 4991.52   -7.13 5068.87  -13.04 5101.47   -9.93
 5167.54   -8.54 5184.66   -4.05 5188.75    -.67  5189.5    2.89 5259.68    2.06
 5879.35   13.54 6335.29   18.44 7070.24   22.03 7100.45    20.6 7169.67   22.32
#Mann= 3 ,-1 , 0
 2563.16    .068       0  4810.5     .03       0  5189.5    .068       0
#XS Ineff= 1 ,-1
  3782.4 4427.87    16.3
Permanent Ineff=
       F
Bank Sta=4810.5,5189.5
XS Rating Curve= 0
Exp/Cntr=.3,.1

Type RM Length L Ch R = 1 ,44198.85,867.81,853.74,815.64
XS GIS Cut Line= 6
     3261372.255    13841388.783     3260256.016    13841156.838
      3260129.44     13841136.85      3259817.65     13841030.59
     3259705.145    13840997.375     3258342.463    13840692.946
#Sta/Elev= 30
 3565.74   14.94 3724.28   16.54 3799.09   13.66 3899.85   13.77  3969.3   11.92
 4035.34    12.8 4166.54   10.59 4233.37   12.44 4311.78    9.58  4371.7    9.57
 4478.58   13.79 4499.26   11.95 4638.06    10.2 4770.78   11.11 4775.91    9.14
 4782.86     9.1 4802.59   14.89 4830.61    2.06 4934.18   -4.21 5015.81  -12.51
    5060  -13.07 5121.25   -6.72 5161.66     .48  5164.7    2.23 5306.28    3.09
 5487.14    7.75 5557.66    7.91 5705.23   12.81 5871.15   14.71 6676.95   19.47
#Mann= 4 ,-1 , 0
 3565.74    .068       0 4830.61     .03       0  5164.7    .068       0
 6179.15    .148       0
#XS Ineff= 1 ,-1
 3683.99 4475.55    13.8
Permanent Ineff=
       F
Bank Sta=4830.61,5164.7
XS Rating Curve= 0
Exp/Cntr=.3,.1

Type RM Length L Ch R = 1 ,43345.11,1172.44,1074.95,965.67
XS GIS Cut Line= 6
     3261662.188    13840562.477     3260473.465    13840316.034
      3260351.31     13840286.44      3260002.54      13840220.9
     3259880.608    13840192.795     3258342.463    13839881.136
#Sta/Elev= 30
 3483.38    16.4 3575.73   18.66 3735.12   16.88    3794   18.12 3851.06   15.16
 4048.43   15.35    4136   11.91 4220.02   11.13 4295.42   12.45 4377.41     9.1
 4411.63   11.05 4515.28   10.95 4622.52    8.58 4822.56     8.7 4841.55     4.1
 4857.88     3.1 4861.03      .7 4885.04    -.92 4919.64   -5.99 5031.72  -12.75
 5059.54  -12.03 5104.56    -6.7 5175.55    -1.9 5177.44    2.07 5320.71    7.74
 5985.58   17.26 6659.48   18.29 6707.18   16.62 6732.75   18.81 6872.47   18.13
#Mann= 7 ,-1 , 0
 3483.38    .068       0 3551.16    .118       0 3585.05    .068       0
 4822.56     .03       0 5177.44    .068       0 5618.51    .148       0
 6736.91    .068       0
Bank Sta=4822.56,5177.44
XS Rating Curve= 0
Exp/Cntr=.3,.1

Type RM Length L Ch R = 1 ,42270.17,1812.09,1311.02,838.8
XS GIS Cut Line= 6
     3263970.861     13839087.61     3260603.935    13839257.782
      3260504.33     13839225.36       3260114.1     13839142.28
     3259995.077    13839127.312     3258459.153    13839243.812
#Sta/Elev= 30
  1324.6   16.92 2293.75   15.65 2528.86    8.92 2770.54    5.76 2832.61    8.26
 3040.88    9.98 3385.28    2.09 3605.01     1.6 3932.75    4.08 4157.98    2.32
 4182.68    5.51 4212.37    5.54 4340.32     2.1 4619.17    2.18 4662.95    4.49
 4687.82    9.49 4740.17    7.48 4777.47   12.75 4800.51   12.94 4826.51    1.48
 4860.17   -1.33 4903.78  -10.69 5015.72  -12.09 5082.79   -7.32 5118.79   -2.48
 5188.06     .06 5199.49    2.82 5491.33   16.85 5907.05   19.03 6859.85   18.06
#Mann= 3 , 0 , 0
  1324.6    .068       0 4800.51     .03       0 5199.49    .068       0
#XS Ineff= 2 ,-1
 2327.87 3199.06   14.06 3199.06 4696.61    9.35
Permanent Ineff=
       F       F
Bank Sta=4800.51,5199.49
XS Rating Curve= 0
Exp/Cntr=.3,.1

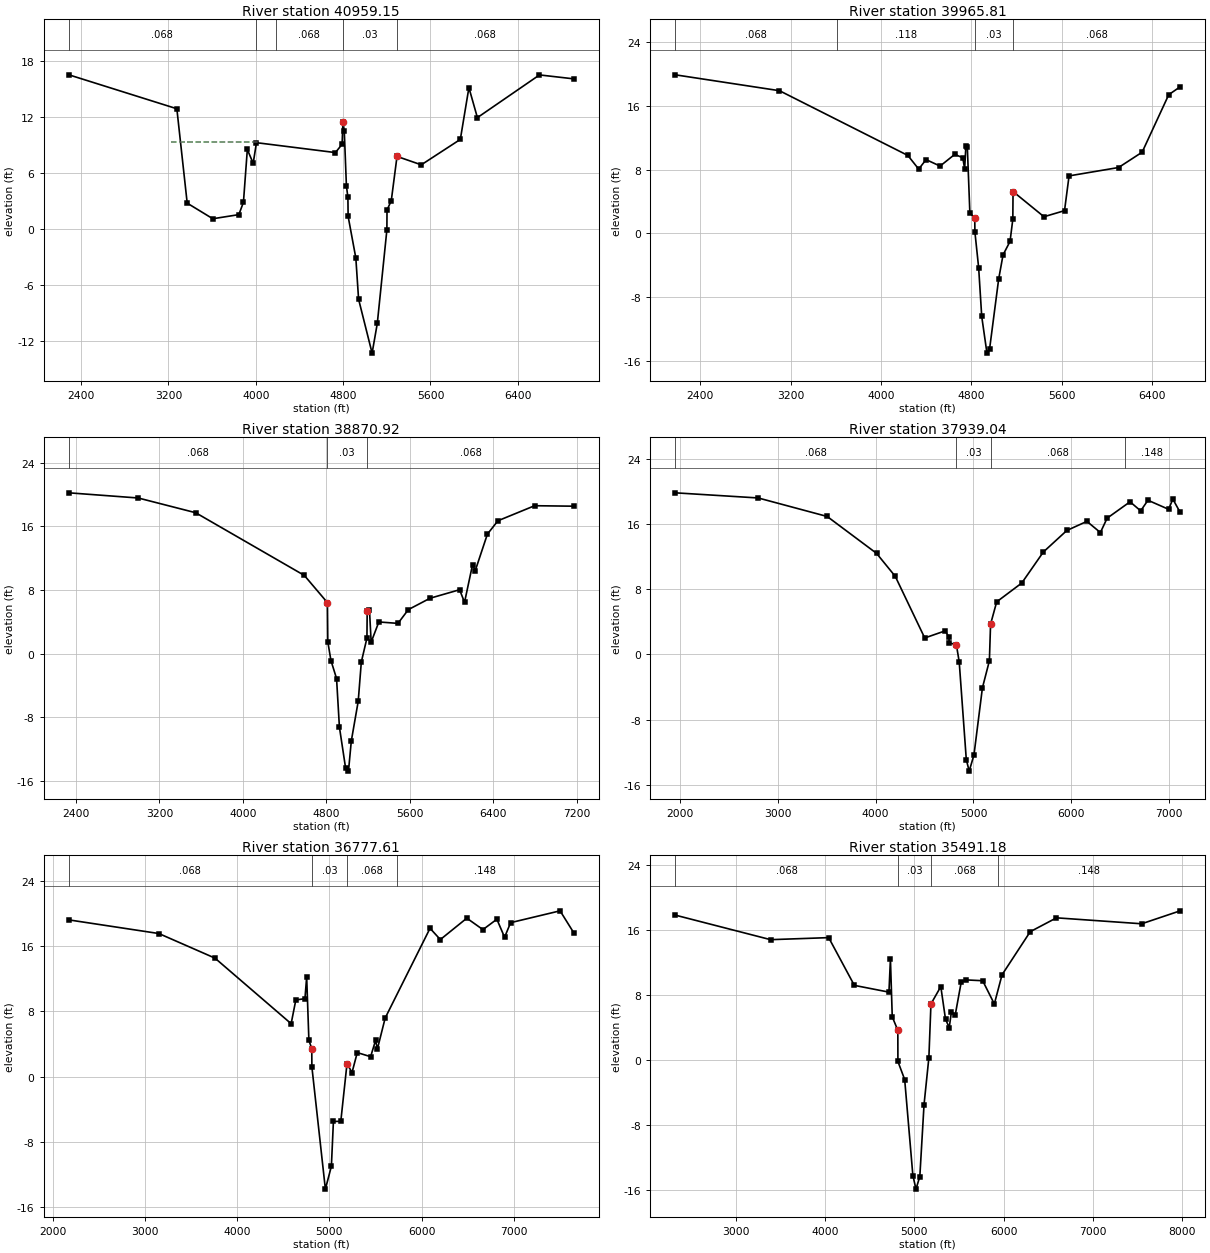
Type RM Length L Ch R = 1 ,40959.15,976.29,993.34,862.38
XS GIS Cut Line= 6
     3262401.515    13836459.935     3260415.479    13837735.637
      3260295.91      13837822.4      3259982.12     13838076.35
     3259864.608    13838141.542     3258429.443     13838793.89
#Sta/Elev= 30
 2288.78   16.51  3277.3   12.88    3372    2.78  3606.6    1.11 3845.01    1.55
 3887.05    2.87  3922.7    8.52 3976.19    7.05 4006.35    9.25 4729.29    8.19
 4790.52    9.08 4798.16   11.48 4810.31   10.54 4829.99    4.63  4843.7     3.4
 4845.69    1.37  4916.3   -3.09 4941.51    -7.5 5065.28  -13.27 5112.85  -10.09
 5200.63    -.08 5201.84    2.04 5240.85    3.04 5293.44    7.78 5515.62    6.88
 5873.24     9.6 5951.85   15.14 6029.51   11.93 6598.21    16.5  6911.5   16.08
#Mann= 5 ,-1 , 0
 2288.78    .068       0 3999.19    .118       0 4184.09    .068       0
 4798.16     .03       0 5293.44    .068       0
#XS Ineff= 1 ,-1
 3226.16 4039.12    9.28
Permanent Ineff=
       F
#Block Obstruct= 2 , 0
                         5946.21           14.69
Bank Sta=4798.16,5293.44
XS Rating Curve= 0
Exp/Cntr=.3,.1

Type RM Length L Ch R = 1 ,39965.81,1297.84,1094.89,874.92
XS GIS Cut Line= 6
     3261749.167    13835720.608     3259632.662    13837097.786
      3259529.79     13837167.18       3259266.7     13837380.91
     3259163.184    13837466.156     3258052.531    13838228.522
#Sta/Elev= 30
 2179.81   19.87  3101.4   17.88 4238.39    9.76  4334.1    8.05 4399.43    9.24
 4523.59    8.43 4653.64     9.9  4724.1    9.47    4741    8.11 4752.03   10.95
 4764.79   10.79  4787.1    2.59 4830.52    1.86 4831.74     .17    4865   -4.31
 4892.13  -10.42 4938.45  -15.02 4961.77   -14.5 5042.11   -5.74 5081.03    -2.7
 5142.95   -1.01 5167.51    1.77 5169.48    5.24 5443.28    2.08 5625.22    2.84
 5665.44     7.2 6103.73    8.25 6312.34   10.17    6548   17.38 6649.21   18.37
#Mann= 4 ,-1 , 0
 2179.81    .068       0 3610.02    .118       0 4830.52     .03       0
 5169.48    .068       0
Bank Sta=4830.52,5169.48
XS Rating Curve= 0
Exp/Cntr=.3,.1

Type RM Length L Ch R = 1 ,38870.92,749.21,931.88,1054.18
XS GIS Cut Line= 6
     3260386.486    13834488.396     3258820.852    13836271.479
      3258763.19     13836356.97      3258537.37      13836663.7
      3258487.43    13836764.364     3257197.231    13838112.549
#Sta/Elev= 30
 2333.32    20.2 2997.54   19.55 3547.37    17.7 4588.26    9.82 4809.55     6.4
 4813.18    1.48 4843.36    -.88 4897.02   -3.14 4924.36   -9.24 4983.12  -14.35
 5011.27  -14.78 5038.36  -10.99  5104.5      -6 5134.24   -1.07    5188    1.94
 5190.45     5.3 5212.27    5.51 5228.44    1.43 5302.03    3.97 5485.31    3.79
 5584.58    5.52 5792.62    6.95 6075.71    8.02 6122.95    6.44 6199.87   11.19
 6225.42   10.41    6342   15.01 6443.11   16.69 6794.46   18.58 7168.66   18.52
#Mann= 3 ,-1 , 0
 2333.32    .068       0 4809.55     .03       0 5190.45    .068       0
Bank Sta=4809.55,5190.45
XS Rating Curve= 0
Exp/Cntr=.3,.1

Type RM Length L Ch R = 1 ,37939.04,1054.5,1161.42,1166.44
XS GIS Cut Line= 6
     3260357.493    13833952.022     3258211.994    13835691.615
      3258123.58     13835758.96       3257866.1     13835995.97
     3257777.096    13836068.527     3256356.428    13837213.759
#Sta/Elev= 30
 1951.34   19.81 2798.44   19.18 3503.94   16.91 4008.65   12.39 4200.18    9.57
 4501.68    2.01 4710.06    2.88 4749.88    2.12 4751.18    1.41 4825.02    1.19
 4854.31    -.92 4926.81  -12.91 4956.48  -14.32 5005.31  -12.32 5091.55   -4.11
 5162.93    -.79 5174.98     3.7 5237.55    6.44 5494.13    8.75 5714.64   12.55
 5954.69   15.19 6160.34   16.31 6298.17   14.94 6367.06    16.7 6601.47   18.71
 6710.08    17.6 6784.67    18.9 6995.72   17.79 7039.09   19.04 7114.19   17.41
#Mann= 4 ,-1 , 0
 1951.34    .068       0 4825.02     .03       0 5174.98    .068       0
 6546.27    .148       0
Bank Sta=4825.02,5174.98
XS Rating Curve= 0
Exp/Cntr=.3,.1

Type RM Length L Ch R = 1 ,36777.61,1308.19,1286.44,1378.61
XS GIS Cut Line= 6
     3259806.621     13833357.66     3257733.606    13834676.852
      3257584.76     13834777.37      3257276.39     13835003.65
     3257182.735    13835068.261     3255327.168    13836503.425
#Sta/Elev= 30
 2172.91   19.18 3149.03   17.51 3757.98    14.5 4584.84    6.47 4635.89    9.38
 4734.73    9.53 4753.51    12.2 4777.56    4.44 4808.76    3.41 4810.02    1.18
  4956.5  -13.79 5021.62  -10.99 5043.72    -5.5 5123.91   -5.49 5191.24    1.58
 5245.64     .49 5302.61    2.93 5447.43    2.43 5501.56    4.43 5521.11    3.37
 5605.44    7.16 6092.35   18.15  6204.1   16.77 6491.64   19.39 6666.41   17.99
 6817.75   19.26 6901.51   17.05 6966.78   18.84 7503.85   20.29 7651.76   17.61
#Mann= 4 ,-1 , 0
 2172.91    .068       0 4808.76     .03       0 5191.24    .068       0
 5734.16    .148       0
Bank Sta=4808.76,5191.24
XS Rating Curve= 0
Exp/Cntr=.3,.1

Type RM Length L Ch R = 1 ,35491.18,628.19,1164.89,1565.62
XS GIS Cut Line= 6
      3259168.77    13832661.823     3257010.816    13833515.711
      3256891.68     13833638.31      3256657.49     13833926.05
      3256559.38    13833995.511     3254152.943     13835155.24
#Sta/Elev= 30
 2322.73   17.79 3389.48   14.78    4040   15.03 4327.46    9.17 4714.94    8.34
 4731.59    12.4 4751.97    5.31  4814.5    3.65 4815.28    -.17  4891.2   -2.39
 4982.97  -14.17 5017.73  -15.84 5060.79  -14.29 5108.02   -5.46 5162.15     .29
  5185.5    6.89 5295.78    9.02 5348.44    5.02 5390.27    3.99 5414.26     5.9
 5456.69     5.5 5524.38    9.57 5581.56    9.84 5764.72    9.74 5895.43    6.89
 5981.68   10.47 6297.55   15.76 6591.58   17.46 7545.57   16.73 7976.95   18.32
#Mann= 4 ,-1 , 0
 2322.73    .068       0  4814.5     .03       0  5185.5    .068       0
 5941.43    .148       0
#XS Ineff= 2 ,-1
  5590.1 5985.62    9.47 5288.47  5550.2    8.83
Permanent Ineff=
       F       F
Bank Sta=4814.5,5185.5
XS Rating Curve= 0
Exp/Cntr=.3,.1