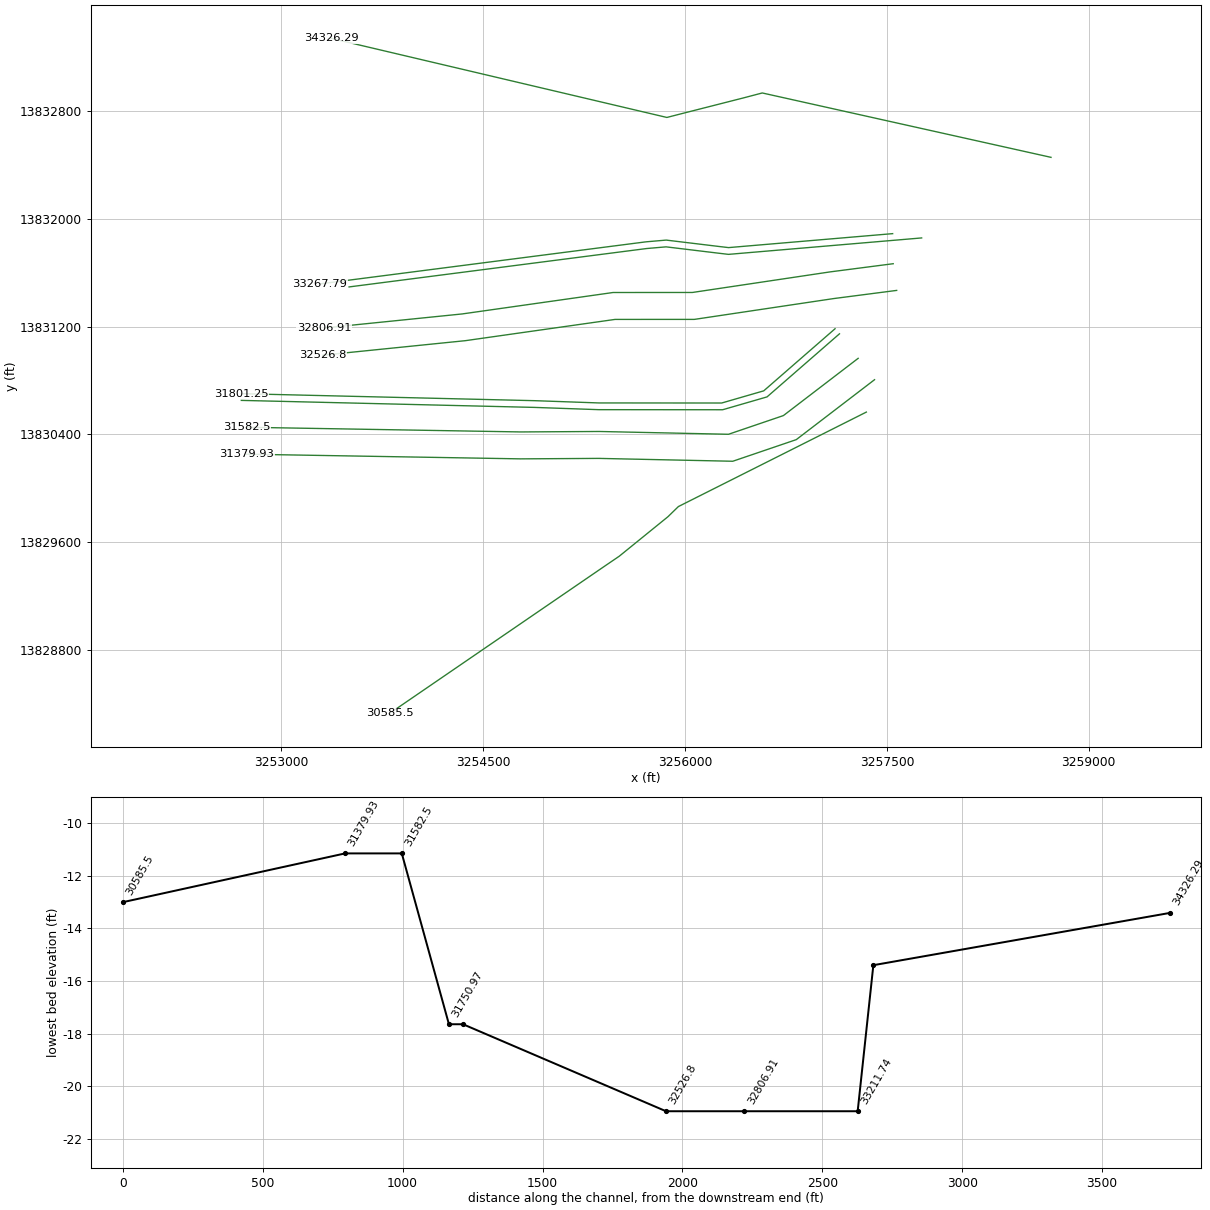
HEC-RAS study Q100-00-00.prj: Q100-00-00

--- Q100-00-00.g01 (geometry) --- (continued)

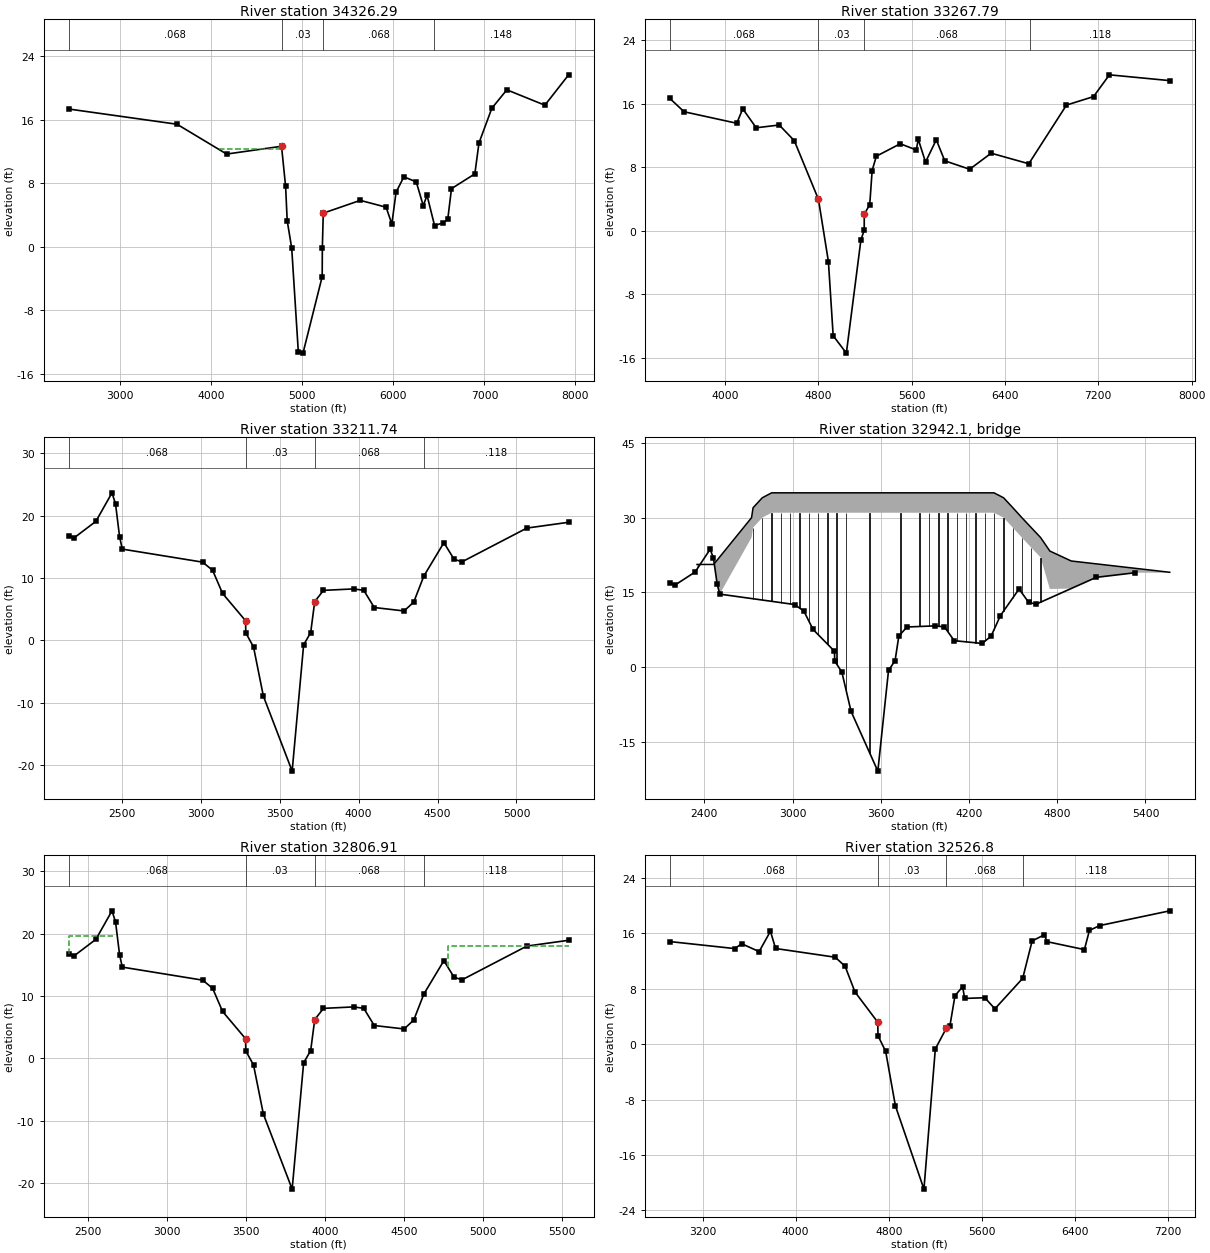
Type RM Length L Ch R = 1 ,34326.29,1081.76,1058.5,1286.53
XS GIS Cut Line= 6
     3258719.375    13832458.871     3256573.877    13832937.259
      3256438.97     13832901.75      3255994.61     13832788.59
     3255864.983    13832755.295     3253370.126    13833343.164
#Sta/Elev= 30
 2431.91   17.36 3622.31   15.44 4167.58   11.68 4770.73   12.66 4815.52    7.59
  4832.9    3.28 4882.56    -.18 4954.96  -13.22 5006.57  -13.42 5217.55   -3.77
 5219.05    -.19 5229.27    4.23 5635.84    5.84 5919.65    4.98 5982.68    2.86
 6028.91    6.86 6114.88    8.81 6251.05    8.17 6327.64    5.18 6369.57    6.47
 6451.98    2.67  6547.5    3.01 6596.71    3.43 6638.05    7.32 6894.51    9.18
 6939.94   13.07 7081.59   17.46 7246.36   19.78 7664.04   17.84 7925.15   21.67
#Mann= 4 ,-1 , 0
 2431.91    .068       0 4770.73     .03       0 5229.27    .068       0
 6441.98    .148       0
#XS Ineff= 2 ,-1
 4083.92 4755.24   12.33 6264.03 6746.97    6.99
Permanent Ineff=
       F       F
Bank Sta=4770.73,5229.27
XS Rating Curve= 0
Exp/Cntr=.3,.1

Type RM Length L Ch R = 1 ,33267.79,53.37,56.04,59.56
XS GIS Cut Line= 6
     3257542.587    13831891.955     3256323.675    13831788.218
     3256251.859    13831796.659     3255860.107    13831844.019
     3255709.885    13831831.097     3253286.956    13831518.461
#Sta/Elev= 30
 3528.44   16.68 3650.64      15 4102.26   13.55  4153.3   15.37 4268.82   12.98
 4465.94   13.33 4594.96   11.36    4802    3.97 4887.44   -3.87 4928.26  -13.21
 5041.16   -15.4 5166.41   -1.09 5194.06     .05 5194.76     2.1 5241.49     3.3
 5262.22     7.6 5298.11     9.4 5503.34   10.97 5640.74   10.18 5657.18   11.54
 5719.38    8.66 5811.82   11.47 5884.28    8.82 6097.76    7.76 6282.02    9.78
 6604.32    8.45  6927.4   15.84 7159.34   16.91 7295.16   19.65 7812.46   18.92
#Mann= 4 ,-1 , 0
 3528.44    .068       0    4802     .03       0 5194.76    .068       0
 6612.94    .118       0
#XS Ineff= 1 ,-1
 5662.04 6921.21   10.96
Permanent Ineff=
       F
Bank Sta=4802,5194.76
XS Rating Curve= 0
Exp/Cntr=.5,.3

Type RM Length L Ch R = 1 ,33211.74,239.93,404.84,357.39
XS GIS Cut Line= 6
 3257758.063386813831860.1124547     3256322.869    13831737.969
      3256245.94     13831747.01      3255859.24     13831793.76
      3255715.23    13831781.372 3253503.611907713831496.0019236
#Sta/Elev= 30
 2164.82    16.8 2199.59   16.45  2337.2   19.09 2439.09   23.66 2461.57   21.89
 2487.04   16.64  2504.4   14.64 3013.09   12.55 3076.29   11.24 3139.05    7.54
 3284.87    3.16 3286.27    1.21 3335.14   -1.04 3397.53   -8.92 3579.73  -20.94
 3652.39     -.7 3696.99    1.26 3722.58    6.23 3778.06    8.03 3968.64    8.26
 4032.86    8.04 4099.56    5.28 4288.42    4.73 4349.47    6.15  4413.6   10.33
  4540.3   15.67 4604.94   13.01 4655.66   12.61 5065.54   18.01 5330.07   18.94
#Mann= 4 ,-1 , 0
 2164.82    .068       0 3284.87     .03       0 3722.58    .068       0
  4413.6    .118       0
#XS Ineff= 1 ,-1
 4008.05 4428.59    7.08
Permanent Ineff=
       F
Bank Sta=3284.87,3722.58
XS Rating Curve= 0
Skew Angle= 42
Exp/Cntr=.5,.3

Type RM Length L Ch R = 3 ,32942.1 ,,,
BEGIN DESCRIPTION:
Spur 55
END DESCRIPTION:
Bridge Culvert--1,0,-1,-1, 0
Deck Dist Width WeirC Skew NumUp NumDn MinLoCord MaxHiCord MaxSubmerge Is_Ogee
235,68,2.6,42, 17, 17, , , .95, 0, 0,0,,
    2350 2462.78 2720.65 2731.06 2793.33 2857.24 2920.56 4309.35 4369.84 4435.39
 4498.18 4559.71 4623.33 4687.16 4749.59  4895.1 5565.41
    20.6    20.6      30      32      34      35      35      35      35      34
      32      30      28      26    23.3    21.3   19.03
       0       0      26      28      30      31      31      31      31      30
      28      26      24      22   15.67       0       0
    2350 2462.78 2720.65 2731.06 2793.33 2857.24 2920.56 4309.35 4369.84 4435.39
 4498.18 4559.71 4623.33 4687.16 4749.59  4895.1 5565.41
    20.6    20.6      30      32      34      35      35      35      35      34
      32      30      28      26    23.3    21.3   19.03
       0       0      26      28      30      31      31      31      31      30
      28      26      24      22   15.67       0       0
Pier Skew, UpSta & Num, DnSta & Num=  ,2731.057, 2 ,2731.057, 2 , 0 , 0 , 0 ,,
       3       3
     -10      35
       3       3
     -10      35
Pier Skew, UpSta & Num, DnSta & Num=  ,2793.333, 2 ,2793.333, 2 , 0 , 0 , 0 ,,
       3       3
     -10      35
       3       3
     -10      35
Pier Skew, UpSta & Num, DnSta & Num=  ,2857.243, 2 ,2857.243, 2 , 0 , 0 , 0 ,,
       3       3
     -10      35
       3       3
     -10      35
Pier Skew, UpSta & Num, DnSta & Num=  ,2920.559, 2 ,2920.559, 2 , 0 , 0 , 0 ,,
       3       3
     -10      35
       3       3
     -10      35
Pier Skew, UpSta & Num, DnSta & Num=  ,2984.024, 2 ,2984.024, 2 , 0 , 0 , 0 ,,
       3       3
     -10      35
       3       3
     -10      35
Pier Skew, UpSta & Num, DnSta & Num=  ,3046.819, 2 ,3046.819, 2 , 0 , 0 , 0 ,,
       3       3
     -10      35
       3       3
     -10      35
Pier Skew, UpSta & Num, DnSta & Num=  ,3110.507, 2 ,3110.507, 2 , 0 , 0 , 0 ,,
       3       3
     -10      35
       3       3
     -10      35
Pier Skew, UpSta & Num, DnSta & Num=  ,3173.526, 2 ,3173.526, 2 , 0 , 0 , 0 ,,
       3       3
     -10      35
       3       3
     -10      35
Pier Skew, UpSta & Num, DnSta & Num=  ,3237.288, 2 ,3237.288, 2 , 0 , 0 , 0 ,,
       3       3
     -10      35
       3       3
     -10      35
Pier Skew, UpSta & Num, DnSta & Num=  ,3299.34, 2 ,3299.34, 2 , 0 , 0 , 0 ,,
       3       3
     -10      35
       3       3
     -10      35
Pier Skew, UpSta & Num, DnSta & Num=  ,3363.548, 2 ,3363.548, 2 , 0 , 0 , 0 ,,
       3       3
     -10      35
       3       3
     -10      35
Pier Skew, UpSta & Num, DnSta & Num=  ,3524.067, 2 ,3524.067, 2 , 0 , 0 , 0 ,,
     5.5     5.5
     -20      32
     5.5     5.5
     -20      32
Pier Skew, UpSta & Num, DnSta & Num=  ,3732.891, 2 ,3732.891, 2 , 0 , 0 , 0 ,,
     5.5     5.5
     -20      32
     5.5     5.5
     -20      32
Pier Skew, UpSta & Num, DnSta & Num=  ,3862.867, 2 ,3862.867, 2 , 0 , 0 , 0 ,,
       3       3
     -10      35
       3       3
     -10      35
Pier Skew, UpSta & Num, DnSta & Num=  ,3928.041, 2 ,3928.041, 2 , 0 , 0 , 0 ,,
       3       3
     -10      35
       3       3
     -10      35
Pier Skew, UpSta & Num, DnSta & Num=  ,3991.951, 2 ,3991.951, 2 , 0 , 0 , 0 ,,
       3       3
     -10      35
       3       3
     -10      35
Pier Skew, UpSta & Num, DnSta & Num=  ,4054.375, 2 ,4054.375, 2 , 0 , 0 , 0 ,,
       3       3
     -10      35
       3       3
     -10      35
Pier Skew, UpSta & Num, DnSta & Num=  ,4116.799, 2 ,4116.799, 2 , 0 , 0 , 0 ,,
       3       3
     -10      35
       3       3
     -10      35
Pier Skew, UpSta & Num, DnSta & Num=  ,4179.967, 2 ,4179.967, 2 , 0 , 0 , 0 ,,
       3       3
     -10      35
       3       3
     -10      35
Pier Skew, UpSta & Num, DnSta & Num=  ,4243.134, 2 ,4243.134, 2 , 0 , 0 , 0 ,,
       3       3
     -10      35
       3       3
     -10      35
Pier Skew, UpSta & Num, DnSta & Num=  ,4309.348, 2 ,4309.348, 2 , 0 , 0 , 0 ,,
       3       3
     -10      35
       3       3
     -10      35
Pier Skew, UpSta & Num, DnSta & Num=  ,4369.84, 2 ,4369.84, 2 , 0 , 0 , 0 ,,
       3       3
     -10      35
       3       3
     -10      35
Pier Skew, UpSta & Num, DnSta & Num=  ,4435.385, 2 ,4435.385, 2 , 0 , 0 , 0 ,,
       3       3
     -10      35
       3       3
     -10      35
Pier Skew, UpSta & Num, DnSta & Num=  ,4498.181, 2 ,4498.181, 2 , 0 , 0 , 0 ,,
       3       3
     -10      35
       3       3
     -10      35
Pier Skew, UpSta & Num, DnSta & Num=  ,4559.714, 2 ,4559.714, 2 , 0 , 0 , 0 ,,
       3       3
     -10      35
       3       3
     -10      35
Pier Skew, UpSta & Num, DnSta & Num=  ,4623.327, 2 ,4623.327, 2 , 0 , 0 , 0 ,,
       3       3
     -10      35
       3       3
     -10      35
Pier Skew, UpSta & Num, DnSta & Num=  ,4687.163, 2 ,4687.163, 2 , 0 , 0 , 0 ,,
       3       3
     -10      35
       3       3
     -10      35
BR Coef=-1 , 1 , 1 ,1.25, 0 ,,,.8,0,1.2,0,
WSPro=,,,, 1 ,,,, 0 ,,,, 0 ,,,,-1 ,-1 ,-1 , 0 , 0 , 0 , 0 , 0
BC Design=,, 0 ,, 0 ,,,,,,
BC HTab HWMax=23.66

Type RM Length L Ch R = 1 ,32806.91,219.1,280.11,202.01
XS GIS Cut Line= 6
     3257546.827    13831668.524     3257078.077     13831607.76
      3256054.57     13831454.81      3255465.58     13831454.62
     3254343.702     13831295.26     3253319.396    13831191.094
#Sta/Elev= 30
2376.823    16.82411.587   16.452549.202   19.092651.095   23.662673.575   21.89
2699.042   16.642716.402   14.643225.093   12.55 3288.29   11.243351.055    7.54
3496.868    3.163498.272    1.213547.142   -1.043609.529   -8.923791.733  -20.94
 3864.39     -.73908.994    1.26 3934.58    6.233990.063    8.034180.636    8.26
4244.858    8.044311.562    5.284500.418    4.734561.467    6.154625.601   10.33
  4752.3   15.674816.938   13.014867.658   12.61 5277.54   18.015542.069   18.94
#Mann= 4 ,-1 , 0
2376.823    .068       03496.868     .03       0 3934.58    .068       0
4625.601    .118       0
#XS Ineff= 3 ,-1
2376.8232656.743    19.64778.4215542.069    18.1 4171.15 4689.49    7.08
Permanent Ineff=
       F       F       F
Bank Sta=3496.868,3934.58
XS Rating Curve= 0
Skew Angle= 42
Exp/Cntr=.5,.3

Type RM Length L Ch R = 1 ,32526.8 ,598.76,725.55,473.27
XS GIS Cut Line= 6
     3257572.538    13831470.184     3257105.715     13831409.67
     3256069.463    13831254.815     3255479.746    13831254.625
     3254367.892    13831096.689     3253307.783    13830988.881
#Sta/Elev= 30
  2918.2   14.81 3474.94    13.8 3536.94   14.49 3685.78   13.36    3783    16.3
 3827.42   13.81 4339.79   12.55 4424.83   11.24 4509.29    7.54  4705.5    3.16
 4707.39    1.21 4773.15   -1.04  4857.1   -8.92 5102.28  -20.94 5200.05     -.7
  5294.5     2.3    5325     2.6 5369.16       7    5435     8.3    5452     6.6
  5625.6     6.7 5712.02     5.1    5951     9.5    6032    14.9 6138.06    15.8
    6159    14.8 6481.34   13.65  6524.5   16.42 6612.62   17.12    7215   19.25
#Mann= 4 ,-1 , 0
  2918.2    .068       0  4705.5     .03       0  5294.5    .068       0
    5951    .118       0
#XS Ineff= 1 ,-1
 5425.43 6004.89    6.96
Permanent Ineff=
       F
Bank Sta=4705.5,5294.5
XS Rating Curve= 0
Exp/Cntr=.3,.1

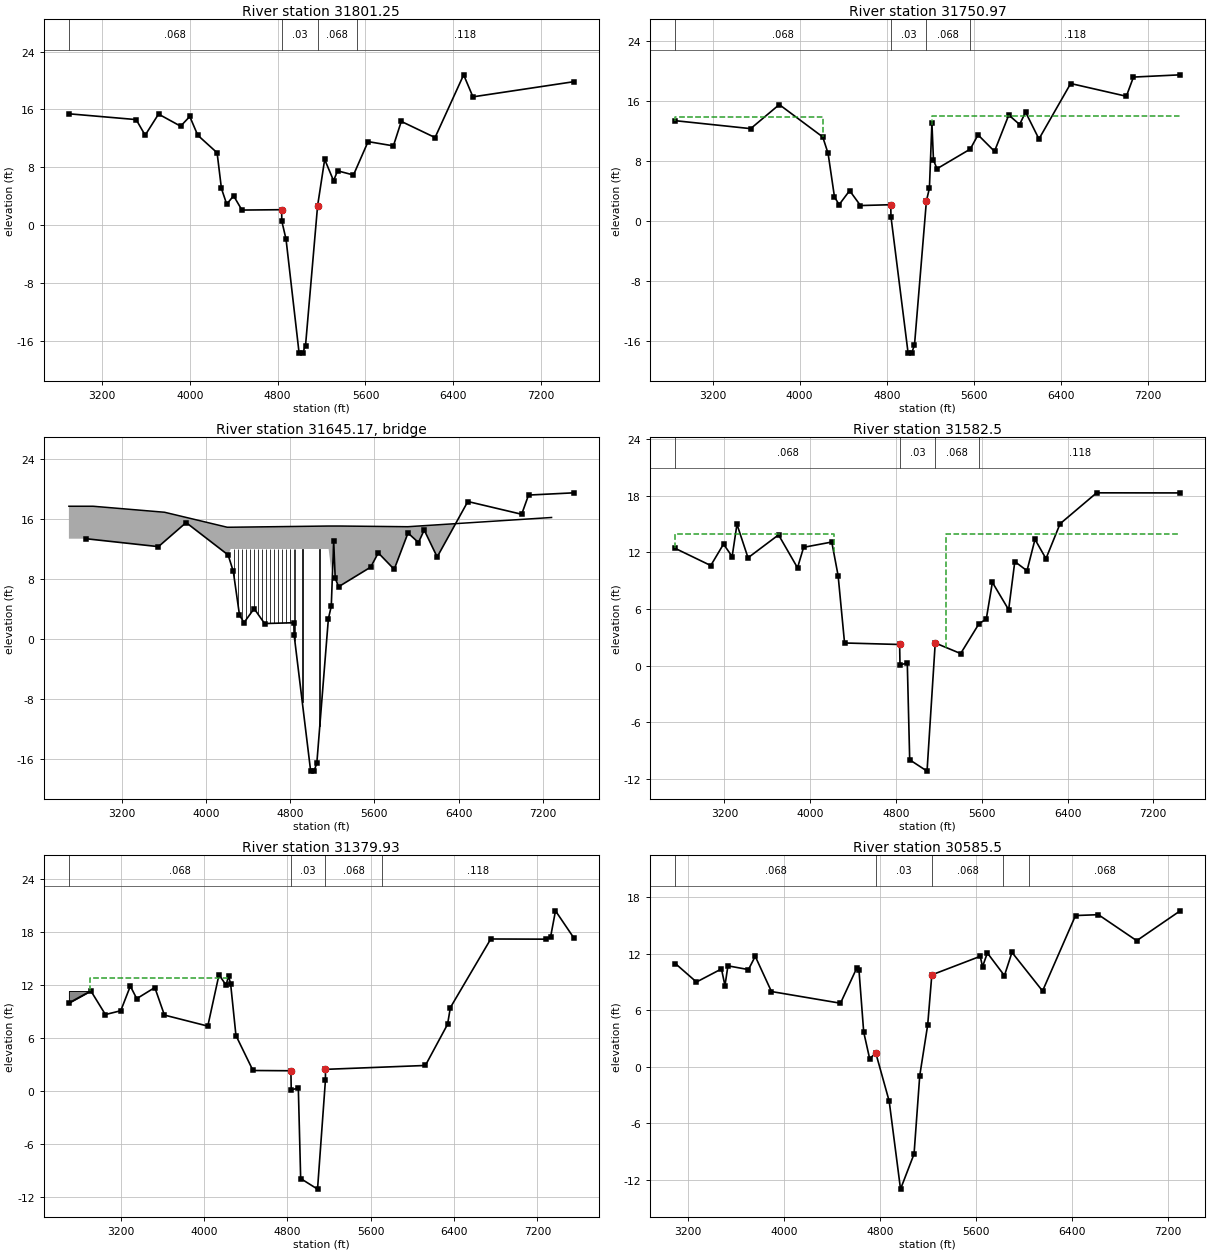
Type RM Length L Ch R = 1 ,31801.25,50.01,50.28,50.01
XS GIS Cut Line= 6
     3257114.682    13831185.395     3256584.816    13830723.898
     3256272.375    13830633.455     3255359.683    13830634.004
     3254883.341    13830650.796     3252704.272    13830702.885
#Sta/Elev= 30
 2899.19    15.4 3511.49    14.6 3593.57   12.44 3715.32   15.36 3916.46   13.69
 3999.89   15.03 4072.46   12.44 4248.68   10.02 4288.07     5.1 4336.25    2.92
 4398.82    4.08 4474.81    2.11 4836.28    2.16 4838.19     .57 4876.38   -1.91
 4994.87  -17.56    5027  -17.64    5054  -16.59 5163.72    2.68 5228.49     9.1
 5309.34    6.16 5345.65    7.53  5490.5    6.95 5623.65   11.56 5854.13   10.97
    5926   14.35 6233.53   12.12 6493.87   20.78 6578.35   17.74 7496.15   19.83
#Mann= 4 ,-1 , 0
 2899.19    .068       0 4836.28     .03       0 5163.72    .068       0
 5519.45    .118       0
Bank Sta=4836.28,5163.72
XS Rating Curve= 0
Exp/Cntr=.5,.3

Type RM Length L Ch R = 1 ,31750.97,195.2,168.47,185.94
XS GIS Cut Line= 6
     3257147.521    13831147.691     3256609.327    13830678.941
     3256279.466    13830583.455      3255358.61     13830584.01
     3254881.896    13830600.816     3252703.077    13830652.899
#Sta/Elev= 30
  2858.9   13.37 3550.18   12.31 3812.96   15.52 4211.94    11.2 4261.02       9
 4319.66    3.19 4362.46    2.17 4458.74    4.04 4558.28    2.05 4836.28    2.16
 4838.19     .57 4994.87  -17.56    5027  -17.64    5054  -16.59 5163.72    2.68
  5191.2    4.36 5214.11   13.06 5228.49     8.1 5260.75    6.96 5565.96    9.58
 5637.56   11.48  5788.7    9.28  5919.8   14.13  6019.2   12.86 6073.78   14.52
 6196.78   10.93 6488.02   18.33 6999.18   16.63 7064.36   19.19 7493.32   19.49
#Mann= 4 ,-1 , 0
  2858.9    .068       0 4836.28     .03       0 5163.72    .068       0
 5565.96    .118       0
#XS Ineff= 2 , 0
       0    4212    13.9    5215       0      14
Permanent Ineff=
       F       F
#Block Obstruct= 2 , 0
                         6085.57           13.29
Bank Sta=4836.28,5163.72
XS Rating Curve= 0
Exp/Cntr=.5,.3

Type RM Length L Ch R = 3 ,31645.17,,,
BEGIN DESCRIPTION:
Missouri Pacific RR
END DESCRIPTION:
Bridge Culvert--1,0,-1,-1, 0
Deck Dist Width WeirC Skew NumUp NumDn MinLoCord MaxHiCord MaxSubmerge Is_Ogee
97.8,16,2.6,0, 9, 9, , , .95, 0, 0,0,,
    2700    2930    3608    4203    4237    5166    5271    5919    7283
    17.7    17.7    16.9    14.9    14.9   15.06   15.06   14.97    16.2
       0       0       0       0      12      12       0       0       0
    2700    2930    3608    4203    4237    5166    5271    5919    7283
    17.7    17.7    16.9    14.9    14.9   15.06   15.06   14.97    16.2
       0       0       0       0      12      12       0       0       0
Pier Skew, UpSta & Num, DnSta & Num=  ,4269, 2 ,4269, 2 , 0 , 0 , 0 ,,
     1.5     1.5
     -20      20
     1.5     1.5
     -20      20
Pier Skew, UpSta & Num, DnSta & Num=  ,4307, 2 ,4307, 2 , 0 , 0 , 0 ,,
     1.5     1.5
     -20      20
     1.5     1.5
     -20      20
Pier Skew, UpSta & Num, DnSta & Num=  ,4345, 2 ,4345, 2 , 0 , 0 , 0 ,,
     1.5     1.5
     -20      20
     1.5     1.5
     -20      20
Pier Skew, UpSta & Num, DnSta & Num=  ,4383, 2 ,4383, 2 , 0 , 0 , 0 ,,
     1.5     1.5
     -20      20
     1.5     1.5
     -20      20
Pier Skew, UpSta & Num, DnSta & Num=  ,4421, 2 ,4421, 2 , 0 , 0 , 0 ,,
     1.5     1.5
     -20      20
     1.5     1.5
     -20      20
Pier Skew, UpSta & Num, DnSta & Num=  ,4459, 2 ,4459, 2 , 0 , 0 , 0 ,,
     1.5     1.5
     -20      20
     1.5     1.5
     -20      20
Pier Skew, UpSta & Num, DnSta & Num=  ,4497, 2 ,4497, 2 , 0 , 0 , 0 ,,
     1.5     1.5
     -20      20
     1.5     1.5
     -20      20
Pier Skew, UpSta & Num, DnSta & Num=  ,4535, 2 ,4535, 2 , 0 , 0 , 0 ,,
     1.5     1.5
     -20      20
     1.5     1.5
     -20      20
Pier Skew, UpSta & Num, DnSta & Num=  ,4573, 2 ,4573, 2 , 0 , 0 , 0 ,,
     1.5     1.5
     -20      20
     1.5     1.5
     -20      20
Pier Skew, UpSta & Num, DnSta & Num=  ,4611, 2 ,4611, 2 , 0 , 0 , 0 ,,
     1.5     1.5
     -20      20
     1.5     1.5
     -20      20
Pier Skew, UpSta & Num, DnSta & Num=  ,4649, 2 ,4649, 2 , 0 , 0 , 0 ,,
     1.5     1.5
     -20      20
     1.5     1.5
     -20      20
Pier Skew, UpSta & Num, DnSta & Num=  ,4687, 2 ,4687, 2 , 0 , 0 , 0 ,,
     1.5     1.5
     -20      20
     1.5     1.5
     -20      20
Pier Skew, UpSta & Num, DnSta & Num=  ,4725, 2 ,4725, 2 , 0 , 0 , 0 ,,
     1.5     1.5
     -20      20
     1.5     1.5
     -20      20
Pier Skew, UpSta & Num, DnSta & Num=  ,4763, 2 ,4763, 2 , 0 , 0 , 0 ,,
     1.5     1.5
     -20      20
     1.5     1.5
     -20      20
Pier Skew, UpSta & Num, DnSta & Num=  ,4803, 2 ,4803, 2 , 0 , 0 , 0 ,,
     1.5     1.5
     -20      20
     1.5     1.5
     -20      20
Pier Skew, UpSta & Num, DnSta & Num=  ,4840, 2 ,4840, 2 , 0 , 0 , 0 ,,
       2       2
     -20      20
       2       2
     -20      20
Pier Skew, UpSta & Num, DnSta & Num=  ,4845, 2 ,4845, 2 , 0 , 0 , 0 ,,
       2       2
     -20      20
       2       2
     -20      20
Pier Skew, UpSta & Num, DnSta & Num=  ,4916, 2 ,4916, 2 , 0 , 0 , 0 ,,
     9.7     9.7
     -20      35
     9.7     9.7
     -20      35
Pier Skew, UpSta & Num, DnSta & Num=  ,5082, 2 ,5082, 2 , 0 , 0 , 0 ,,
     9.7     9.7
     -20      35
     9.7     9.7
     -20      35
BR Coef=-1 , 1 , 1 ,1.25, 0 ,,,.8,0,1.2,0,
WSPro=,,,, 1 ,,,, 0 ,,,, 0 ,,,,-1 ,-1 ,-1 , 0 , 0 , 0 , 0 , 0
BC Design=,, 0 ,, 0 ,,,,,,
BC HTab HWMax=19.65

Type RM Length L Ch R = 1 ,31582.5 ,200.66,202.57,200.03
XS GIS Cut Line= 6
      3257286.41    13830965.399     3256730.855    13830540.052
     3256322.869    13830401.163      3255362.74     13830421.96
      3254777.73    13830418.524      3252746.48    13830453.247
#Sta/Elev= 30
 2742.66   12.42 3072.62   10.61 3191.66   12.88 3272.06   11.56 3317.04   14.98
 3420.22   11.43 3704.86   13.86 3881.84   10.37 3938.58   12.54 4201.24    13.1
 4260.42    9.54 4320.42    2.41 4834.03    2.25 4837.49     .08 4905.41      .3
 4927.91   -9.96 5089.68  -11.16 5165.97    2.41 5403.17    1.29 5575.28    4.47
 5641.94    4.93    5699    8.83 5850.78    5.93 5908.14   11.03  6021.8   10.06
  6096.4   13.38 6198.78   11.34 6330.12   15.03 6671.12   18.31 7450.34    18.3
#Mann= 4 ,-1 , 0
 2742.66    .068       0 4834.03     .03       0 5165.97    .068       0
 5575.28    .118       0
#XS Ineff= 2 , 0
       0    4219      14    5270       0      14
Permanent Ineff=
       F       F
#Block Obstruct= 2 , 0
         4193.15   12.83 5960.88            11.3
Bank Sta=4834.03,5165.97
XS Rating Curve= 0
Exp/Cntr=.5,.3

Type RM Length L Ch R = 1 ,31379.93,94.88,794.43,1176.48
XS GIS Cut Line= 6
     3257407.992    13830806.598     3256826.377    13830361.299
     3256354.644    13830200.709     3255358.623    13830221.975
     3254777.911    13830218.492     3252743.061    13830253.276
#Sta/Elev= 30
  2704.4    9.93 2914.94    11.3  3054.5    8.62 3201.86    9.05 3293.68   11.84
 3355.24   10.42 3528.74   11.68 3620.66    8.56 4036.85    7.31 4144.07   13.12
 4212.01   11.96 4235.74   12.96 4255.65   12.13 4307.08    6.24 4470.37    2.28
 4834.03    2.25 4837.49     .08 4905.41      .3 4927.91   -9.96 5089.68  -11.16
 5165.67    1.21 5165.97    2.41 6124.47    2.85  6337.1    7.51 6364.21    9.41
 6751.59   17.18 7280.95   17.16  7326.1   17.44 7372.67   20.37 7547.44   17.32
#Mann= 4 ,-1 , 0
  2704.4    .068       0 4834.03     .03       0 5165.97    .068       0
 5707.09    .118       0
#XS Ineff= 1 ,-1
 2904.41 4235.35   12.73
Permanent Ineff=
       F
#Block Obstruct= 2 ,-1
  2704.4 2897.63   11.29 5166.05 5944.66    2.41
Bank Sta=4834.03,5165.97
XS Rating Curve= 0
Exp/Cntr=.3,.1

Type RM Length L Ch R = 1 ,30585.5 ,151.97,1115.99,1949.63
XS GIS Cut Line= 6
     3257347.174    13830566.094     3255950.523    13829863.977
      3255873.41     13829788.92      3255510.78     13829494.81
     3255414.148    13829429.079     3253805.024    13828327.336
#Sta/Elev= 30
 3097.36   10.94 3273.02    8.98 3481.22   10.37  3510.4     8.6 3535.14    10.7
  3705.9    10.3 3762.59   11.71 3897.64    7.97 4472.57    6.73 4609.86   10.51
 4626.65   10.25 4666.04    3.67 4715.75     .83 4766.55    1.45 4878.26   -3.67
 4972.78  -13.01  5085.4   -9.28 5132.91    -.95 5198.99    4.42 5233.45    9.74
 5636.78   11.71 5655.95    10.6 5695.81   12.07 5838.31    9.66 5900.96   12.13
 6155.86    8.03 6430.36   16.04 6620.87   16.13 6940.06   13.37 7302.11   16.54
#Mann= 5 ,-1 , 0
 3097.36    .068       0 4766.55     .03       0 5233.45    .068       0
 5830.44    .118       0 6040.68    .068       0
#XS Ineff= 1 ,-1
  3466.2 4590.91    9.74
Permanent Ineff=
       F
#Block Obstruct= 2 , 0
                         5622.25            11.3
Bank Sta=4766.55,5233.45
XS Rating Curve= 0
Exp/Cntr=.3,.1