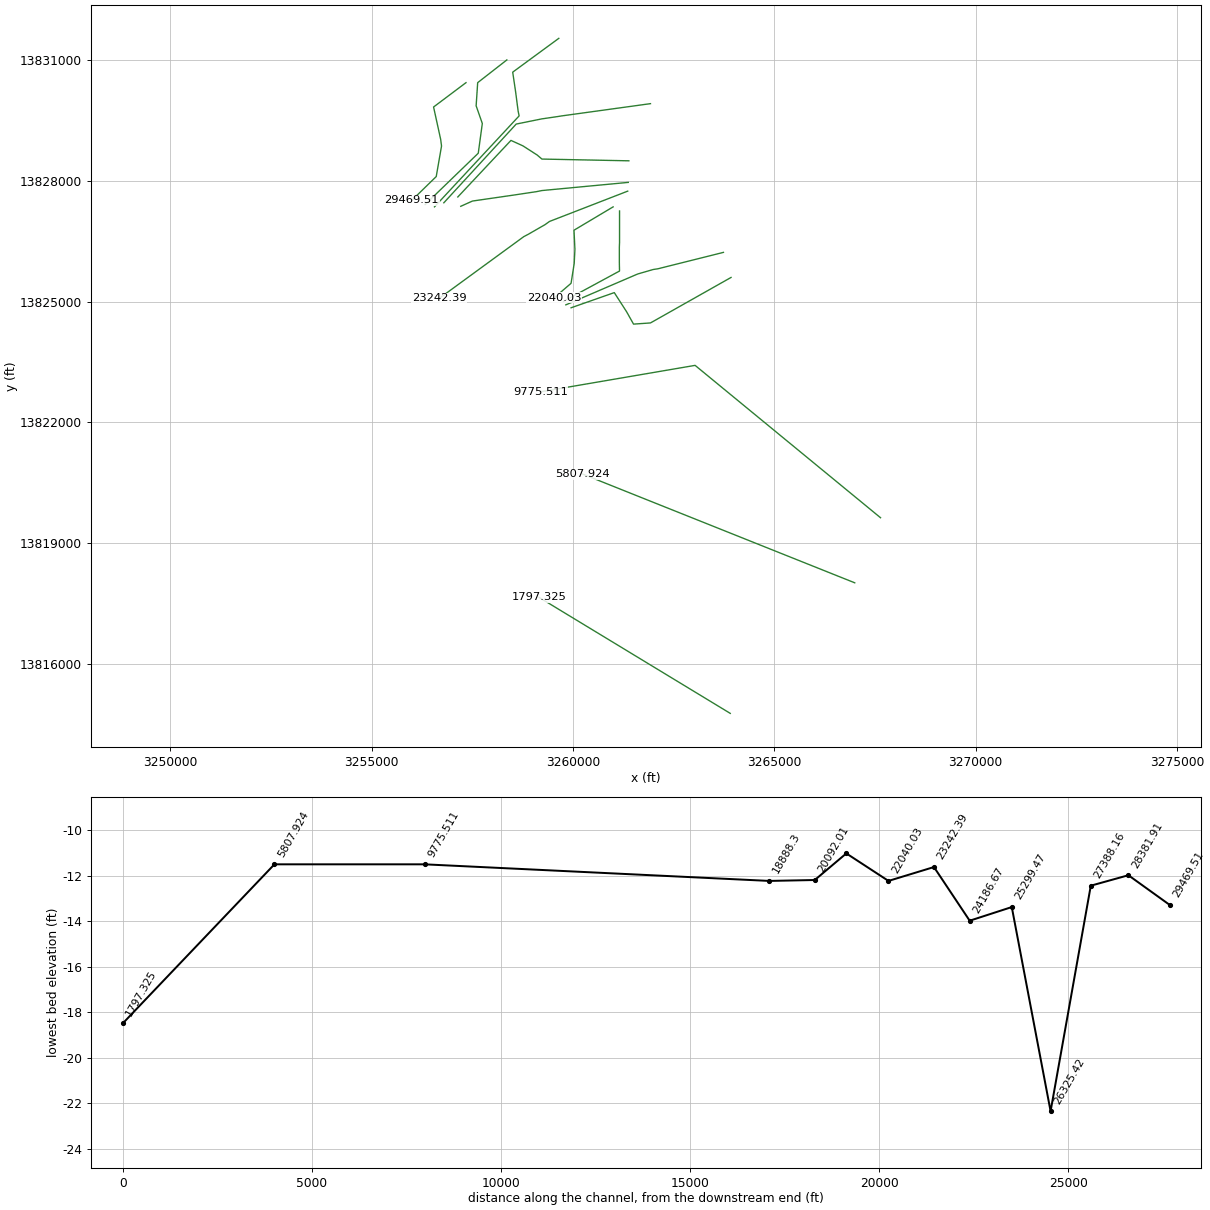
HEC-RAS study Q100-00-00.prj: Q100-00-00

--- Q100-00-00.g01 (geometry) --- (continued)

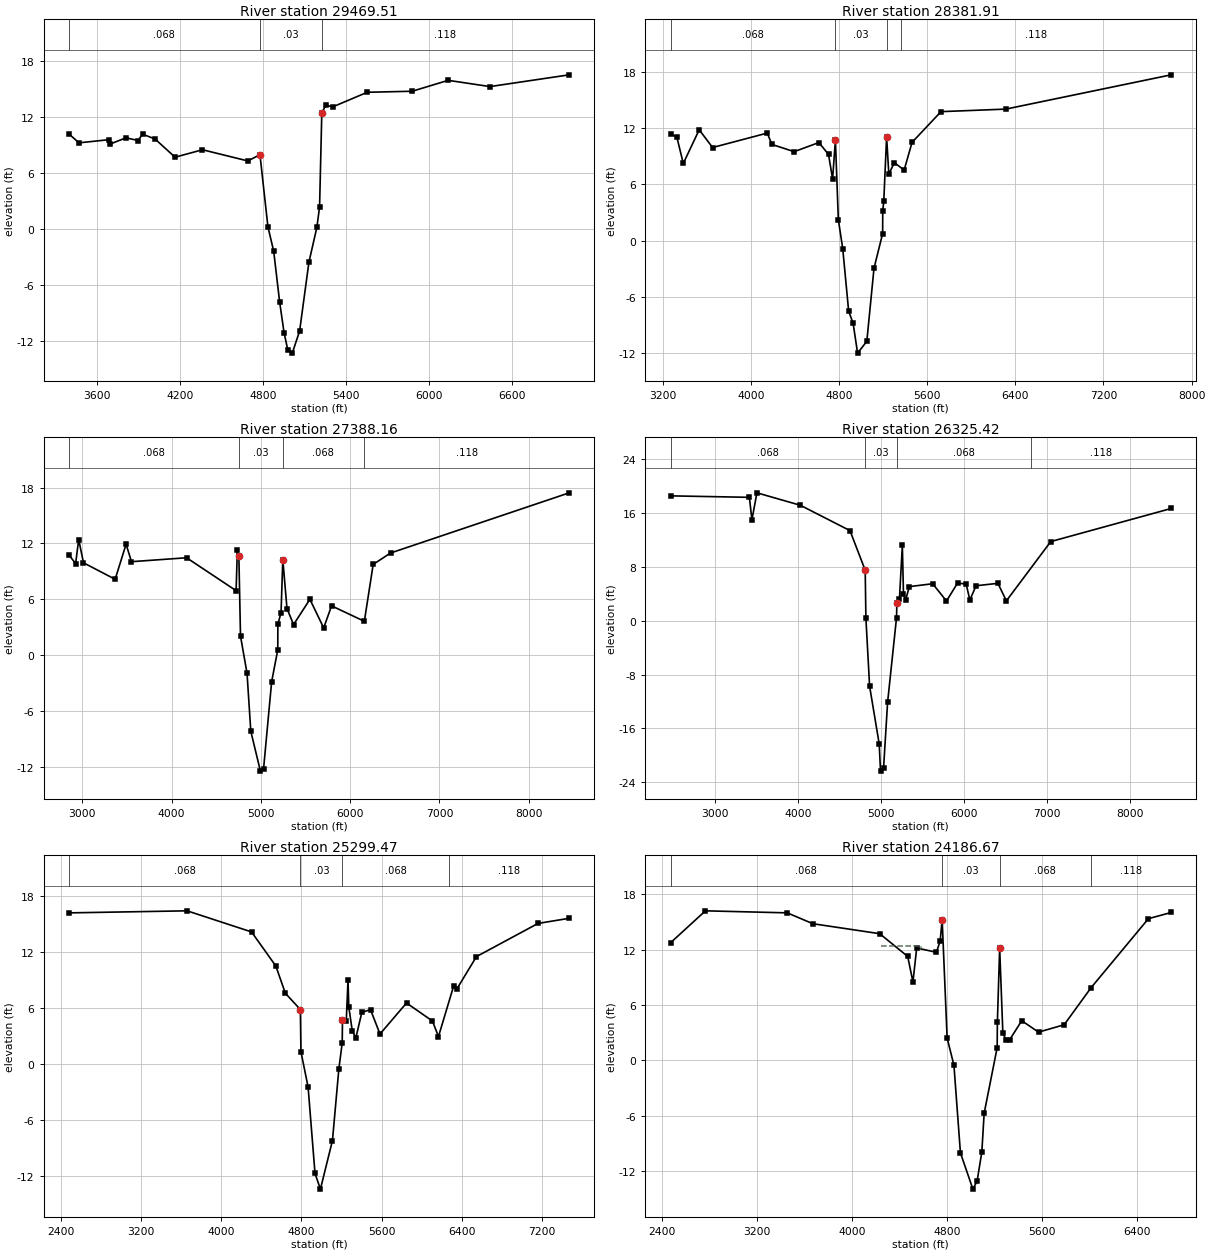
Type RM Length L Ch R = 1 ,29469.51,519.81,1087.6,539.46
XS GIS Cut Line= 6
     3257342.197    13830443.841     3256536.858    13829838.628
      3256712.99     13829034.94     3256734.774    13828869.878
      3256602.87    13828109.887     3255994.012    13827515.526
#Sta/Elev= 30
 3393.12   10.25    3468    9.26 3686.64     9.6 3693.46    9.13 3808.17     9.8
  3895.2    9.51 3927.94   10.19 4018.32    9.67 4162.75    7.72 4361.13    8.52
 4688.79    7.32 4776.56    7.99 4833.98     .27 4875.84   -2.36 4918.41   -7.75
 4950.59  -11.08 4978.06  -12.96 5010.11  -13.28 5063.05  -10.92 5130.48   -3.53
 5187.73     .19 5207.45    2.38 5223.44   12.43 5252.01   13.31 5302.01   13.11
 5552.16   14.68 5877.08   14.79 6137.06   15.96 6439.04   15.29 7012.22   16.55
#Mann= 3 ,-1 , 0
 3393.12    .068       0 4776.56     .03       0 5223.44    .118       0
Bank Sta=4776.56,5223.44
XS Rating Curve= 0
Exp/Cntr=.3,.1

Type RM Length L Ch R = 1 ,28381.91,934.87,993.75,163.74
XS GIS Cut Line= 6
      3258356.96    13831009.209      3257632.13    13830443.841
      3257593.95     13829867.94      3257747.39     13829429.45
     3257646.626    13828689.751     3256327.434     13827414.05
#Sta/Elev= 30
 3271.53   11.33 3328.84   11.04  3387.5    8.21  3531.9    11.8  3653.4    9.91
 4149.94   11.45 4190.78   10.24 4393.49    9.47 4618.08   10.44 4705.46    9.17
 4742.11    6.56 4767.72   10.69 4794.28    2.24 4834.32    -.87 4887.67   -7.49
 4928.63   -8.82 4968.99  -11.98  5052.8  -10.72 5117.78   -2.95  5196.2     .75
 5197.26    3.18 5206.66    4.22 5232.28   11.04 5252.38    7.08 5302.47     8.3
 5391.36    7.51 5463.18   10.46 5725.62   13.73 6313.49      14 7814.16   17.65
#Mann= 4 ,-1 , 0
 3271.53    .068       0 4767.72     .03       0 5232.28    .068       0
 5361.14    .118       0
Bank Sta=4767.72,5232.28
XS Rating Curve= 0
Exp/Cntr=.3,.1

Type RM Length L Ch R = 1 ,27388.16,2238.21,1062.74,105.96
XS GIS Cut Line= 6
     3259647.159    13831545.584     3258501.926     13830704.78
      3258573.16     13830223.91      3258636.86     13829735.76
     3258661.389    13829617.535      3256559.38    13827356.063
#Sta/Elev= 30
 2846.76   10.81 2925.85    9.84 2960.02   12.42 3013.85    9.92 3368.39    8.15
 3490.74   11.92 3551.23   10.04 4168.45   10.46    4723    6.93 4736.89   11.28
 4753.86   10.69 4772.26    2.06  4845.5   -1.94  4887.6   -8.16 4995.39  -12.44
 5029.98  -12.25 5121.19   -2.84 5189.62     .58 5190.69     3.3 5226.36    4.58
 5246.14   10.27 5292.83    5.01 5366.65    3.29  5549.7       6 5703.93    2.93
 5792.06     5.3  6159.3    3.64 6258.34    9.75  6452.7   10.97 8454.16   17.43
#Mann= 4 ,-1 , 0
 2846.76    .068       0 4753.86     .03       0 5246.14    .068       0
 6155.13    .118       0
Bank Sta=4753.86,5246.14
XS Rating Curve= 0
Exp/Cntr=.3,.1

Type RM Length L Ch R = 1 ,26325.42,1163.72,1025.94,183.28
XS GIS Cut Line= 6
     3261923.127    13829921.963     3259719.642    13829617.535
      3259600.08     13829598.54      3259222.68     13829543.15
     3258588.906    13829414.582     3256791.326    13827457.539
#Sta/Elev= 30
    2464   18.58  3414.3   18.36 3444.58   15.02 3505.15   19.03  4028.3   17.18
 4625.99   13.41 4809.28    7.51 4817.69     .39 4862.39   -9.74 4978.33  -18.35
 4993.68  -22.36  5030.6  -21.88 5078.95  -12.13 5186.68     .47 5190.72    2.61
 5221.56    3.18 5256.63   11.23  5270.5    3.93  5297.2    3.14  5340.7    5.08
 5622.22    5.51 5788.17    2.94 5921.94    5.61 6025.55    5.46 6069.89    3.09
 6144.84    5.21 6408.01    5.57 6509.63    2.96 7044.36   11.78 8494.92    16.7
#Mann= 4 ,-1 , 0
    2464    .068       0 4809.28     .03       0 5190.72    .068       0
 6806.26    .118       0
Bank Sta=4809.28,5190.72
XS Rating Curve= 0
Exp/Cntr=.3,.1

Type RM Length L Ch R = 1 ,25299.47,677.96,1112.8,719.01
XS GIS Cut Line= 6
     3261386.752    13828501.295     3259226.757    13828544.785
      3259111.46     13828643.75      3258758.64     13828871.27
     3258458.436    13829008.677     3257139.245    13827602.506
#Sta/Elev= 30
 2479.82    16.2 3661.07   16.42 4303.62   14.16 4545.64   10.51 4640.25     7.6
 4790.09    5.85 4795.97    1.33 4867.12   -2.44 4936.09   -11.7 4990.07  -13.38
 5110.01   -8.18 5173.57    -.53 5207.34    2.28 5209.91    4.73 5247.65    4.62
 5265.02    8.99 5273.08    6.11 5307.83    3.55 5343.41    2.82  5403.3    5.57
  5489.5    5.83 5583.85    3.23 5848.31    6.55 6106.94    4.62 6166.56    2.95
 6317.42    8.35 6348.56    8.03 6545.38   11.52 7159.07   15.07 7470.28   15.62
#Mann= 4 ,-1 , 0
 2479.82    .068       0 4790.09     .03       0 5209.91    .068       0
 6272.57    .118       0
Bank Sta=4790.09,5209.91
XS Rating Curve= 0
Exp/Cntr=.3,.1

Type RM Length L Ch R = 1 ,24186.67,551.07,944.28,1285.18
XS GIS Cut Line= 6
     3261372.255    13827964.921     3259226.757    13827761.968
      3259096.07     13827735.46     3258501.926    13827645.995
      3257501.66    13827501.029     3257211.728     13827370.56
#Sta/Elev= 30
 2469.23   12.74  2763.5   16.21 3452.74   15.99 3669.07   14.81 4231.63   13.73
 4467.74   11.26 4511.56    8.49 4543.34   12.18 4709.92   11.71 4741.46   12.97
 4757.73   15.26 4799.71     2.4 4856.96    -.53 4911.66  -10.04 5016.61  -13.98
 5052.25  -13.11    5092   -9.95 5111.48   -5.76 5221.14    1.36 5223.08    4.16
 5242.27   12.17 5269.14    2.95 5294.83    2.23 5325.19     2.2 5428.35    4.29
 5569.46    3.05 5785.59    3.85 6012.32    7.87 6495.56   15.36 6687.19   16.03
#Mann= 4 ,-1 , 0
 2469.23    .068       0 4757.73     .03       0 5242.27    .068       0
 6012.32    .118       0
#XS Ineff= 1 ,-1
 4243.28 4579.46   12.39
Permanent Ineff=
       F
Bank Sta=4757.73,5242.27
XS Rating Curve= 0
Exp/Cntr=.3,.1

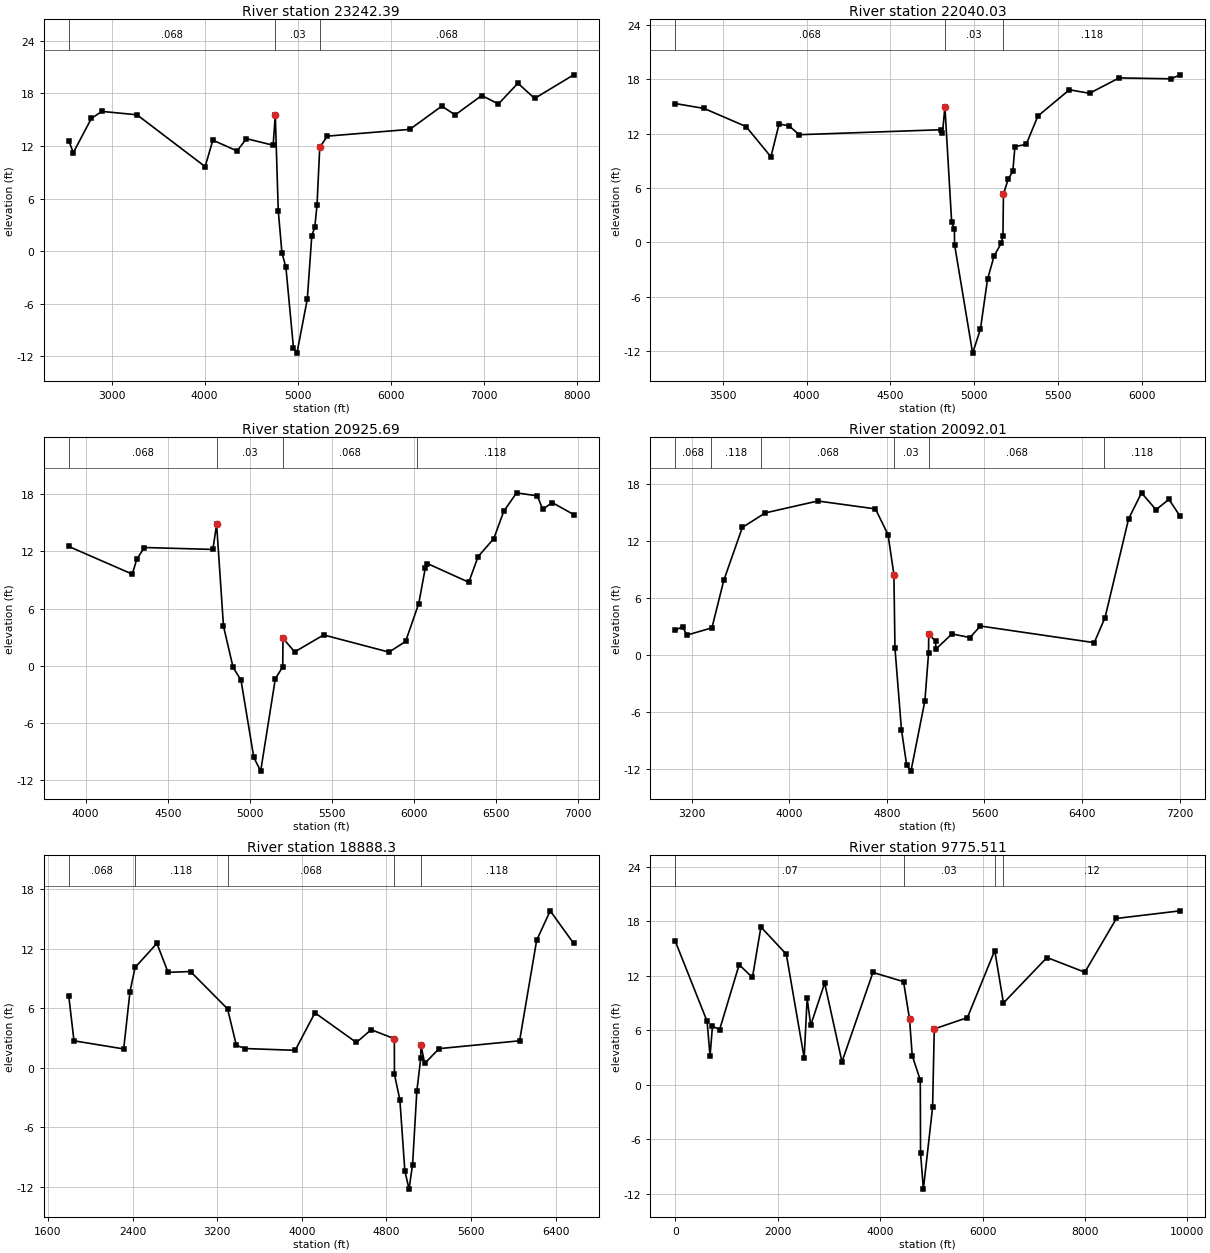
Type RM Length L Ch R = 1 ,23242.39,329.1,1202.36,1856.91
XS GIS Cut Line= 6
     3261357.759    13827747.472     3259415.213    13826993.648
      3259302.16     13826912.87      3258887.77     13826674.58
     3258777.362    13826616.736     3256675.353    13825080.095
#Sta/Elev= 30
 2540.63   12.61 2588.91   11.24  2783.6   15.15 2896.25   15.95 3274.26   15.56
 4006.79    9.65 4089.72   12.67 4349.64   11.44 4451.26   12.84 4738.11   12.09
 4760.99   15.56 4792.95    4.63 4832.54    -.18 4875.15   -1.83 4956.55  -11.04
 4993.75  -11.62  5105.2   -5.46 5153.51    1.78 5185.55    2.72 5209.82    5.29
 5239.01   11.84 5320.22   13.13 6207.35    13.9 6551.34   16.55 6695.45   15.55
 6980.89   17.76  7160.3    16.8 7369.86   19.16 7549.43   17.43 7969.71   20.12
#Mann= 3 ,-1 , 0
 2540.63    .068       0 4760.99     .03       0 5239.01    .068       0
Bank Sta=4760.99,5239.01
XS Rating Curve= 0
Exp/Cntr=.3,.1

Type RM Length L Ch R = 1 ,22040.03,749.61,1114.34,286.35
XS GIS Cut Line= 6
     3260995.343    13827356.063      3260024.07    13826776.199
      3260047.12     13826299.41      3260029.38     13825950.65
     3259951.587    13825457.007     3259531.186    13825094.592
#Sta/Elev= 30
 3216.58   15.32 3388.59   14.78 3638.98   12.78  3787.3    9.44 3835.98   13.06
 3895.58   12.86 3955.79   11.88 4803.28   12.43    4811   12.04 4825.39   14.97
 4865.66    2.26  4881.8    1.46 4883.33    -.28 4990.87  -12.23 5037.34   -9.59
 5079.59    -4.1 5118.85   -1.51 5162.41    -.06 5171.78     .74 5174.61    5.33
 5203.57       7 5230.56    7.82 5243.26   10.57 5310.54   10.81 5380.14   13.94
 5568.17   16.84 5688.23   16.45  5864.8   18.15 6175.36   18.05 6229.12   18.49
#Mann= 3 ,-1 , 0
 3216.58    .068       0 4825.39     .03       0 5174.61    .118       0
Bank Sta=4825.39,5174.61
XS Rating Curve= 0
Exp/Cntr=.3,.1

Type RM Length L Ch R = 1 ,20925.69,1524.12,833.68,127.53
XS GIS Cut Line= 6
     3261154.806    13827254.587     3261154.806    13826457.273
      3261150.11     13826354.37      3261150.75     13825950.08
     3261154.806    13825761.436     3259763.131    13825007.612
#Sta/Elev= 30
 3897.25   12.52 4283.96    9.62 4311.18   11.16 4357.11   12.41    4775   12.21
 4797.85   14.83 4839.68    4.17 4897.92    -.13  4946.6   -1.51 5024.31   -9.58
 5066.21  -11.02 5155.63   -1.33 5200.79    -.09 5202.15    2.91 5273.07    1.47
 5449.98    3.25 5848.12    1.45  5949.3    2.57 6029.23    6.54 6069.54   10.29
 6082.13   10.73 6334.08    8.77 6390.92   11.46 6486.49   13.34  6546.9   16.19
 6625.14   18.14 6752.05   17.82 6784.47   16.41 6842.39   17.12 6973.28   15.86
#Mann= 4 ,-1 , 0
 3897.25    .068       0 4797.85     .03       0 5202.15    .068       0
 6019.71    .118       0
Bank Sta=4797.85,5202.15
XS Rating Curve= 0
Exp/Cntr=.3,.1

Type RM Length L Ch R = 1 ,20092.01,1084.45,1203.71,129.83
XS GIS Cut Line= 6
     3263735.203    13826225.327     3262109.774    13825817.795
      3261994.85     13825800.57      3261720.86     13825721.47
     3261604.566    13825687.586     3259821.118    13824920.632
#Sta/Elev= 30
 3064.73    2.63 3125.59    3.01  3158.9    2.11 3365.41    2.88  3462.3    7.86
 3614.67   13.44 3802.87   14.97 4233.25   16.22 4705.97   15.39 4809.19   12.68
 4857.41    8.48 4865.99     .74 4919.33   -7.83  4962.3  -11.59  4997.2  -12.19
 5111.44   -4.79 5141.43     .22 5142.59     2.2  5199.2    1.48 5201.99     .65
  5333.9    2.24 5480.66    1.86  5566.2    3.07 6499.66    1.32 6588.37    3.96
 6781.47   14.34  6887.4   17.08 7006.26    15.3 7112.19    16.4 7204.35    14.6
#Mann= 6 ,-1 , 0
 3064.73    .068       0  3354.5    .118       0 3768.47    .068       0
 4857.41     .03       0 5142.59    .068       0 6583.41    .118       0
#Block Obstruct= 2 , 0
         3575.54   10.27
Bank Sta=4857.41,5142.59
XS Rating Curve= 0
Exp/Cntr=.3,.1

Type RM Length L Ch R = 1 ,18888.3 ,6053.746,9112.795,2368.056
XS GIS Cut Line= 6
     3263923.659    13825601.973     3261923.127    13824471.237
     3261502.725    13824442.244      3261328.47     13824752.17
     3261024.337    13825225.061     3259951.587    13824848.149
#Sta/Elev= 30
  1796.5    7.21 1845.53    2.72 2315.58     1.9 2375.24    7.68 2423.35   10.11
 2629.58   12.54 2735.46    9.62  2947.6     9.7  3297.7    5.94 3381.05    2.26
 3464.64    1.94 3937.28    1.76 4123.94    5.54 4515.88    2.55 4655.44    3.84
 4874.69    2.93 4875.66    -.65 4927.11   -3.24 4974.06  -10.38 5013.58  -12.23
 5047.28   -9.75 5087.36   -2.36 5124.36     .96 5125.31    2.33 5161.86     .44
 5297.74    1.93 6059.13    2.72 6220.46   12.85  6348.5   15.82 6570.72   12.53
#Mann= 5 ,-1 , 0
  1796.5    .068       0 2423.35    .118       0  3297.7    .068       0
 4874.69     .03       0 5125.31    .118       0
#Block Obstruct= 2 , 0
         2532.37    8.96
Bank Sta=4874.69,5125.31
XS Rating Curve= 0
Exp/Cntr=.3,.1

Type RM Length L Ch R = 1 ,9775.511,2528.87,3967.59,2983.64
XS GIS Cut Line= 3
     3267635.823    13819629.744      3263031.17    13823416.582
     3259190.997    13822758.774
#Sta/Elev= 30
       0    15.8  621.81    6.97  679.37    3.15   726.6    6.45  866.04    6.06
 1247.42   13.21 1507.13    11.8 1672.44   17.36 2168.15   14.36 2517.03    2.95
 2575.29    9.51 2644.57    6.54 2917.01   11.18 3255.03    2.52 3859.57   12.36
 4456.96   11.34 4574.06    7.23 4626.57     3.2    4784      .5    4789    -7.5
    4844   -11.5    5024    -2.5  5057.1    6.14 5703.68    7.38  6237.8   14.77
 6407.63    8.99 7257.39      14 7996.76   12.38 8613.05    18.3  9857.9   19.14
#Mann= 4 ,-1 , 0
       0     .07       0 4456.96     .03       0  6237.8     .07       0
 6407.63     .12       0
#Block Obstruct= 2 , 0
         4143.05   11.72  6288.8           14.66
Bank Sta=4574.06,5057.1
XS Rating Curve= 0
Exp/Cntr=.3,.1

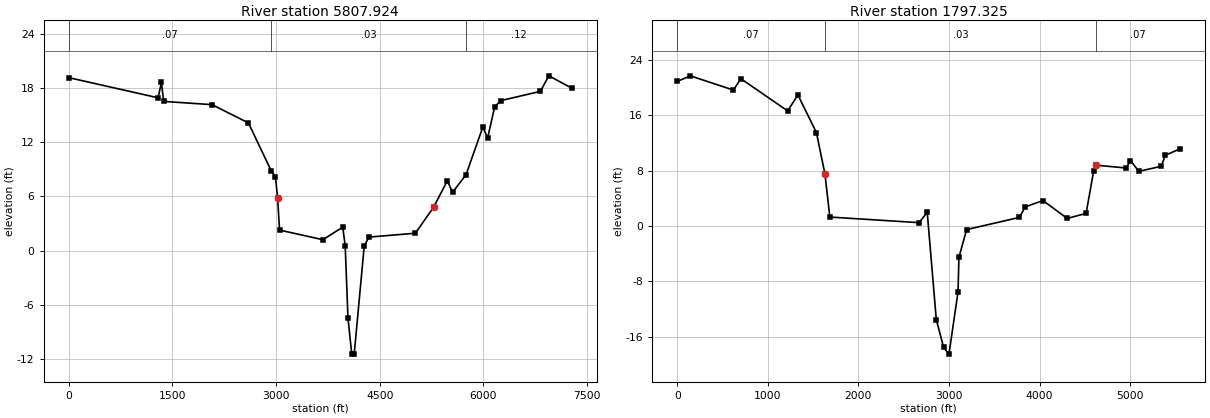
Type RM Length L Ch R = 1 ,5807.924,4088.85,4010.6,3416.42
XS GIS Cut Line= 2
     3266995.794    13818011.893     3260239.933    13820714.237
#Sta/Elev= 30
       0   19.19 1293.04   16.95 1341.51   18.65 1373.82   16.55 2074.45   16.19
 2600.28   14.16 2932.34     8.8  2990.3    8.21 3022.52    5.81 3050.11    2.27
 3677.49     1.2 3964.47     2.6    4000      .5    4040    -7.5    4095   -11.5
    4130   -11.5    4275      .5 4343.05    1.49 5015.32    1.92 5277.89     4.8
 5476.36    7.73  5554.2    6.47 5748.26    8.42 5992.64   13.74 6059.36   12.46
 6162.65   15.97 6255.12   16.65 6822.37   17.66 6945.81   19.39 7276.28   18.03
#Mann= 3 ,-1 , 0
       0     .07       0 2932.34     .03       0 5748.26     .12       0
Bank Sta=3022.52,5277.89
XS Rating Curve= 0
Exp/Cntr=.3,.1

Type RM Length L Ch R = 1 ,1797.325,1823.92,1797.32,1923.63
XS GIS Cut Line= 2
     3263904.284    13814766.496 3259157.179076313817649.2405781
#Sta/Elev= 30
       0   20.91  144.05   21.72  620.58   19.66  701.92   21.31 1218.75   16.65
    1332   18.96 1536.62   13.51 1630.67    7.53 1684.59    1.31    2670      .5
    2760       2    2860   -13.5    2940   -17.5    3000   -18.5    3100    -9.5
    3110    -4.5    3195     -.5  3778.4    1.26 3841.52    2.77 4037.57     3.7
 4305.47    1.11  4514.2    1.84 4596.85    7.91 4627.04     8.8 4956.85     8.4
 5003.18    9.48 5096.74    7.92 5343.03    8.64 5389.46   10.24 5553.85   11.19
#Mann= 3 ,-1 , 0
       0     .07       0 1630.67     .03       0 4627.04     .07       0
Bank Sta=1630.67,4627.04
XS Rating Curve= 0
Exp/Cntr=.3,.1

Chan Stop Cuts=-1